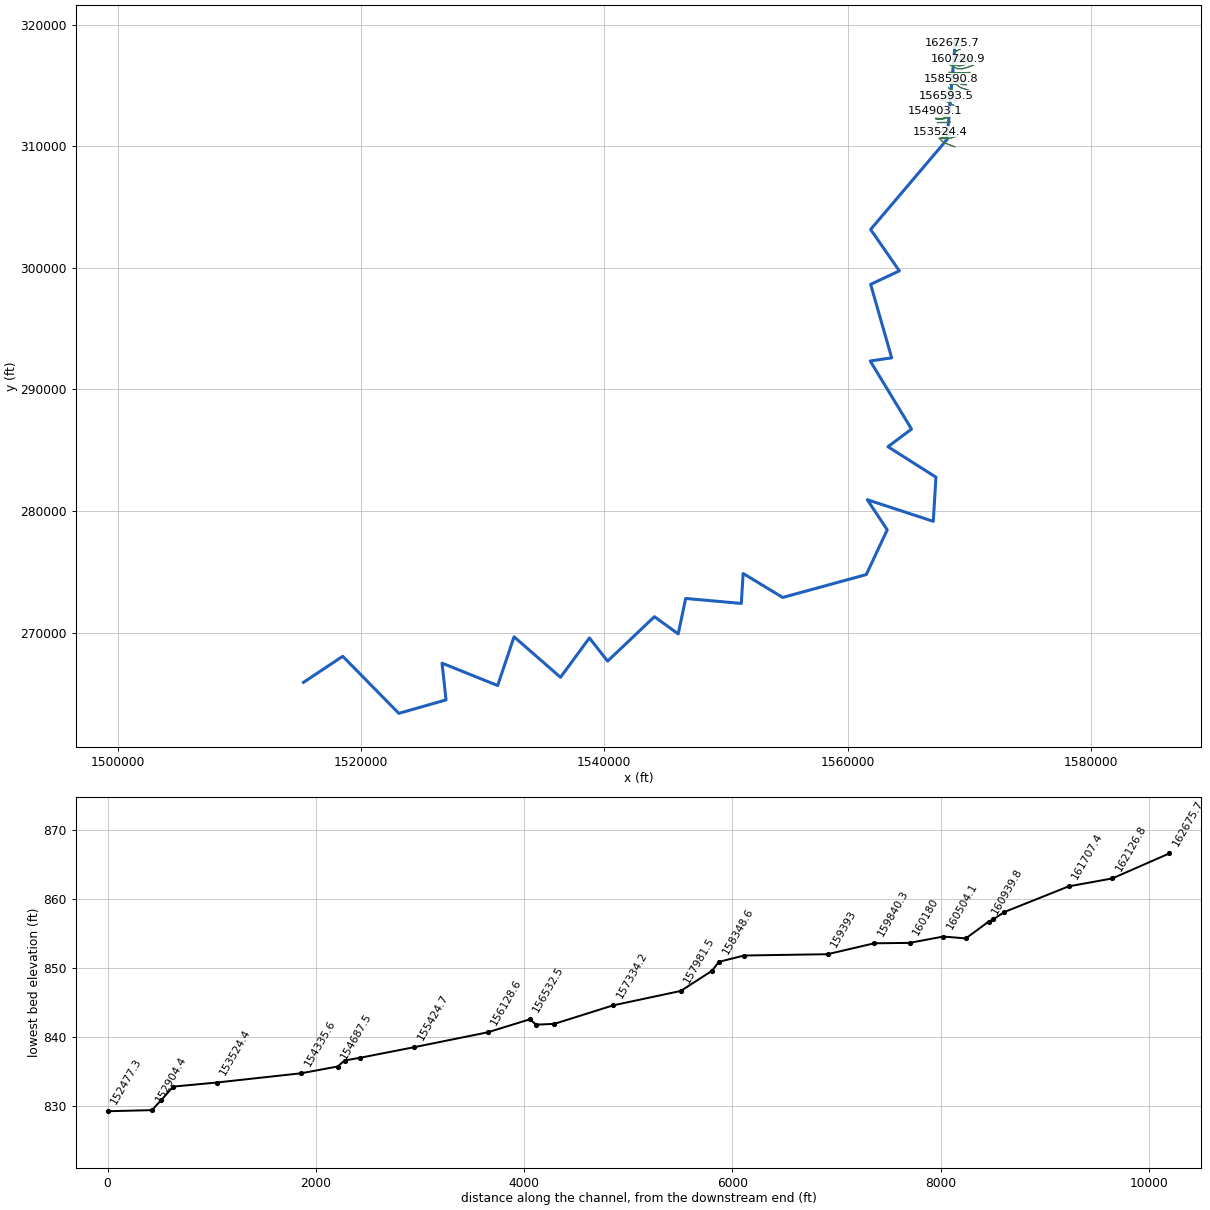
--- NFHGHSRV1.prj (project) ---

Proj Title=NFHGHSRV1
Current Plan=p01
Default Exp/Contr=0,0
English Units
Geom File=g01
Flow File=f01
Plan File=p01
BEGIN DESCRIPTION:
END DESCRIPTION:
DSS Export Rating Curves= 0
DSS Export Rating Curve Sorted= 0
DSS Export Volume Flow Curves= 0
DXF OffsetX= 0
DXF OffsetY= 0
DXF ScaleX= 0
DXF ScaleY= 0

--- NFHGHSRV1.p01 (plan) ---

Plan Title=Floodplain
Program Version=4.00
Geom File=g01
Flow File=f01
K Sum by GR=0
Std Step Tol=0.01
Critical Tol=0.01
Num of Std Step Trials=20
Max Error Tol=0.3
Flow Tol Ratio=0.001
Split Flow NTrial=30
Split Flow Tol=0.02
Split Flow Ratio=0.02
Log Output Level=0
Friction Slope Method=1
Unsteady Friction Slope Method=2
Unsteady Bridges Friction Slope Method=1
Global Log Level=0
CheckData=False
Run HTab=0
Run UNet=0
Run PostProcess=0
UNET Theta=0
UNET Theta Warmup=0
UNET ZTol=0
UNET ZSATol=0
UNET MxIter=0
UNET MaxInSteps=0
UNET DtIC=0
UNET DtMin=0
UNET MaxCRTS=0
UNET WFStab=0
UNET SFStab=0
UNET WFX=0
UNET SFX=0
UNET DSS MLevel=0
UNET DZMax Abort=0
UNET Convert EG Bridges=0
UNET Use Existing IB Tables=0
UNET Froude Limit=0
UNET Froude Power=0
Write IC File=0
Echo Input=False
Echo Output=False
Write Detailed=0

--- NFHGHSRV1.f01 (steady flow) ---

Flow Title=NFF Regression Equation
Program Version=4.10
Number of Profiles= 1
Profile Names=P100yr
River Rch & RM=NFHGHSRV1,Main            ,162675.7
1016.542
River Rch & RM=NFHGHSRV1,Main            ,160180
1114.234
River Rch & RM=NFHGHSRV1,Main            ,159840.3
1406.522
River Rch & RM=NFHGHSRV1,Main            ,159393
1481.202
River Rch & RM=NFHGHSRV1,Main            ,158590.8
1488.445
River Rch & RM=NFHGHSRV1,Main            ,157981.5
1632.904
River Rch & RM=NFHGHSRV1,Main            ,154903.1
 1720.65
River Rch & RM=NFHGHSRV1,Main            ,154335.6
1976.998
River Rch & RM=NFHGHSRV1,Main            ,153108.5
1988.034
River Rch & RM=NFHGHSRV1,Main            ,152477.3
2356.573
River Rch & RM=NFHGHSRV1,Main            ,149885.9
2405.649
River Rch & RM=NFHGHSRV1,Main            ,149004.3
2754.549
River Rch & RM=NFHGHSRV1,Main            ,143782.1
2864.864
River Rch & RM=NFHGHSRV1,Main            ,143206.2
3079.292
River Rch & RM=NFHGHSRV1,Main            ,141165.3
  3097.3
River Rch & RM=NFHGHSRV1,Main            ,140470.4
3485.083
River Rch & RM=NFHGHSRV1,Main            ,134618
3632.881
River Rch & RM=NFHGHSRV1,Main            ,130046.2
3829.951
River Rch & RM=NFHGHSRV1,Main            ,129495.5
4239.242
River Rch & RM=NFHGHSRV1,Main            ,117871.4
4430.986
River Rch & RM=NFHGHSRV1,Main            ,105739.3
4764.632
River Rch & RM=NFHGHSRV1,Main            ,105235.8
 5437.15
River Rch & RM=NFHGHSRV1,Main            ,100856.8
5465.026
River Rch & RM=NFHGHSRV1,Main            ,100233.1
6632.784
River Rch & RM=NFHGHSRV1,Main            ,82186.6
6875.045
River Rch & RM=NFHGHSRV1,Main            ,81597.5
 7400.68
River Rch & RM=NFHGHSRV1,Main            ,63597.5
7946.295
River Rch & RM=NFHGHSRV1,Main            ,62876.1
8394.459
River Rch & RM=NFHGHSRV1,Main            ,47523.4
8713.536
River Rch & RM=NFHGHSRV1,Main            ,47030.5
9601.027
River Rch & RM=NFHGHSRV1,Main            ,33608.2
10116.46
River Rch & RM=NFHGHSRV1,Main            ,32433.3
10538.39
River Rch & RM=NFHGHSRV1,Main            ,14500.6
10720.53
River Rch & RM=NFHGHSRV1,Main            ,13951
 11396.3
Boundary for River Rch & Prof#=NFHGHSRV1,Main            , 1
Up Type= 0
Dn Type= 1
Dn Known WS=733.46
DSS Import GetInterval= 0
DSS Import GetPeak= 0
DSS Import FillOption= 0

--- NFHGHSRV1.g01 (geometry) ---

Geom Title=USGS 10m DEM
Program Version=4.10

River Reach=NFHGHSRV1       ,Main
Reach XY= 30
     1568876.495      318773.889     1568182.742      310559.556
     1561900.263      303161.258     1564260.907      299755.987
     1561900.862      298643.251     1563631.036      292605.833
     1561868.993      292343.109     1565264.078      286742.866
     1563327.787      285292.964     1567272.286      282788.063
     1567053.335      279158.483     1561628.261      280935.222
     1563266.159      278457.973     1561542.256        274777.9
     1554670.324      272897.427     1551414.768      274869.649
     1551264.074      272404.372     1546689.768      272814.788
     1546075.879      269898.122     1544118.935      271314.094
     1540267.951      267659.762     1538773.543      269567.644
     1536394.231      266330.168     1532577.091      269662.066
     1531224.878      265653.819     1526652.525      267492.856
     1526980.185      264471.699      1523099.89       263363.54
     1518485.593      268057.711     1515254.439      265912.385

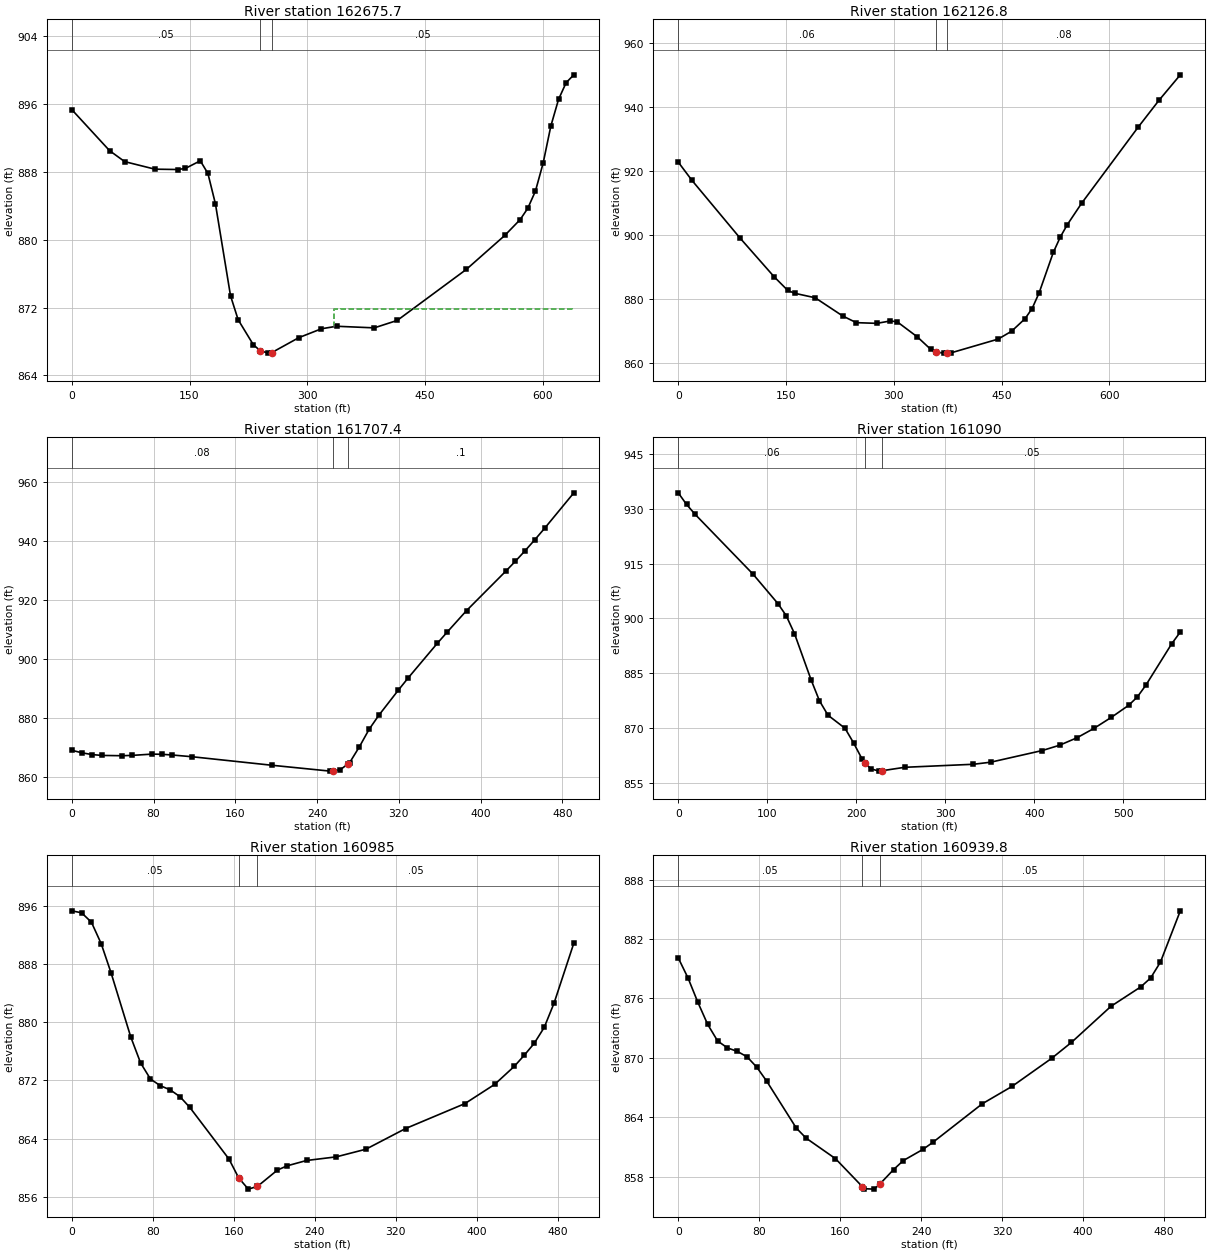
Type RM Length L Ch R = 1 ,162675.7,551.4,548.9,543.6
XS GIS Cut Line= 5
     1569092.462      318879.886     1568928.186      318761.929
     1568851.142      318721.899     1568776.489      318661.136
     1568592.462      318485.788
#Sta/Elev= 30
       0  895.35    48.2   890.5    67.4  889.21   105.9  888.32   134.8  888.28
   144.5   888.4   163.7  889.31   173.4  887.82     183  884.22   202.2  873.39
   211.9  870.56   231.2  867.62   239.9  866.91   250.5  866.62   254.9  866.69
   289.1  868.44   317.9  869.49   337.2  869.79   385.3   869.6   414.6  870.48
   502.6   876.5   551.5   880.5   571.1  882.37   580.8   883.7   590.6  885.74
   600.4  889.04   610.2  893.41     620  896.55   629.7  898.53   639.5  899.45
#Mann= 3 , 0 , 0
       0     .05       0   239.9    .045       0   254.9     .05       0
#XS Ineff= 2 , 0
                          333.61          871.83
Permanent Ineff=
       F       F
Bank Sta=239.9,254.9
XS Rating Curve= 0 ,0
Exp/Cntr=0.3,0.1

Type RM Length L Ch R = 1 ,162126.8,411.7,419.4,417.7
XS GIS Cut Line= 4
     1569390.766      318294.403     1569097.363      318259.681
     1568918.544      318204.125      1568710.21      318146.833
#Sta/Elev= 30
       0  922.79    19.1  917.07    85.8  899.07   133.4  886.91   152.5  882.61
     162  881.73   190.6  880.32   228.7  874.65   247.8  872.53   276.4  872.31
   295.4  873.07   304.8  872.79   332.9  868.05   351.6  864.14   358.6   863.3
   370.4  862.99   373.6  863.02   379.7  863.08   445.2  867.38     464  869.85
   482.7  873.77   492.5  876.94   502.3  881.87     522   894.5   531.8  899.35
   541.6  903.23   561.3  909.86   639.8  933.63   669.3  942.19   698.8  950.11
#Mann= 3 , 0 , 0
       0     .06       0   358.6    .045       0   373.6     .08       0
Bank Sta=358.6,373.6
XS Rating Curve= 0 ,0
Exp/Cntr=0.3,0.1

Type RM Length L Ch R = 1 ,161707.4,626.2,617.4,606.6
XS GIS Cut Line= 4
     1569268.677      317989.261     1569114.724      317924.611
     1568956.738       317836.07     1568840.419      317752.736
#Sta/Elev= 30
       0  868.92     9.8  868.07    19.6  867.47    29.5  867.17    49.1  867.07
    58.9  867.18    78.6  867.62    88.4  867.55    98.2  867.32   117.9  866.72
   195.6  863.84   252.8  861.84   255.1  861.93   262.3  862.23   270.1  864.24
   271.8  864.68   281.4  870.11   290.9  876.04   300.4   880.8   319.5  889.34
     329  893.44   357.6  905.23   367.2  909.02   386.2  916.34   424.4  929.66
   433.9  933.07   443.5  936.68     453   940.4   462.6  944.29   491.2  956.34
#Mann= 3 , 0 , 0
       0     .08       0   255.1    .045       0   270.1      .1       0
Bank Sta=255.1,270.1
XS Rating Curve= 0 ,0
Exp/Cntr=0.3,0.1

Type RM Length L Ch R = 1 ,161090  ,117.4,105,92.2
XS GIS Cut Line= 4
     1569679.336      317523.186     1569521.281      317510.094
     1569406.698      317501.413     1569116.767      317484.052
#Sta/Elev= 30
       0  934.41     9.3  931.24    18.7  928.58      84  912.12     112  904.04
   121.3  900.73   130.6  895.81   149.3  883.11   158.6  877.42   168.2  873.45
   187.3  869.88   196.9  865.89   206.5  861.44   210.3  860.38     216  858.78
   225.6  858.12  229.29 858.243   254.4  859.17   331.6     860     351  860.57
     409  863.77   428.4  865.22   447.8  867.25   467.1  869.85   486.5  872.86
   505.9  876.15   515.6  878.42   525.2  881.64   554.3  893.02     564  896.26
#Mann= 3 , 0 , 0
       0     .06       0   210.3    .045       0  229.29     .05       0
Bank Sta=210.3,229.29
XS Rating Curve= 0 ,0
Exp/Cntr=0.3,0.1

Type RM Length L Ch R = 1 ,160985  ,45.3,45.1,45.3
XS GIS Cut Line= 4
     1569616.767      317350.372     1569476.142      317388.566
     1569399.753      317428.497     1569135.864      317438.913
#Sta/Elev= 30
       0  895.27     9.7     895    19.4  893.71    29.1  890.75    38.9  886.72
    58.3  877.95      68  874.39    77.7  872.19    87.4  871.27    97.2   870.7
   106.9  869.76   116.6  868.29   155.3   861.2   164.9  858.61   174.4  857.07
   183.4  857.44   203.2  859.69   212.8  860.27   231.9     861   261.3   861.5
   290.6  862.55   329.7  865.38   388.4  868.81   417.8  871.45   437.3  873.94
   447.1  875.46   456.9  877.09   466.7  879.26   476.4  882.58     496  890.84
#Mann= 3 , 0 , 0
       0     .05       0   164.9    .045       0   183.4     .05       0
Bank Sta=164.9,183.4
XS Rating Curve= 0 ,0
Exp/Cntr=0.3,0.1

Type RM Length L Ch R = 1 ,160939.8,206.7,218.9,231.2
XS GIS Cut Line= 4
     1569613.295      317301.761      1569472.67      317339.955
     1569396.281      317379.886     1569132.392      317390.302
#Sta/Elev= 30
       0  880.09     9.7  878.05    19.4   875.6    29.1  873.37    38.9   871.7
    48.6     871    58.3  870.65      68   870.1    77.7  869.04    87.4  867.64
   116.6  862.91   126.3  861.89   155.3  859.82   181.8     857     184  856.78
   193.6  856.74   199.6857.2981   212.8  858.72   222.3  859.62   241.7  860.75
   251.5  861.46   300.4  865.36   329.7  867.11   368.8  869.94   388.4  871.55
   427.5   875.2   456.9  877.16   466.7  878.06   476.4  879.67     496  884.84
#Mann= 3 , 0 , 0
       0     .05       0   181.8    .045       0   199.6     .05       0
Bank Sta=181.8,199.6
XS Rating Curve= 0 ,0
Exp/Cntr=0.3,0.1

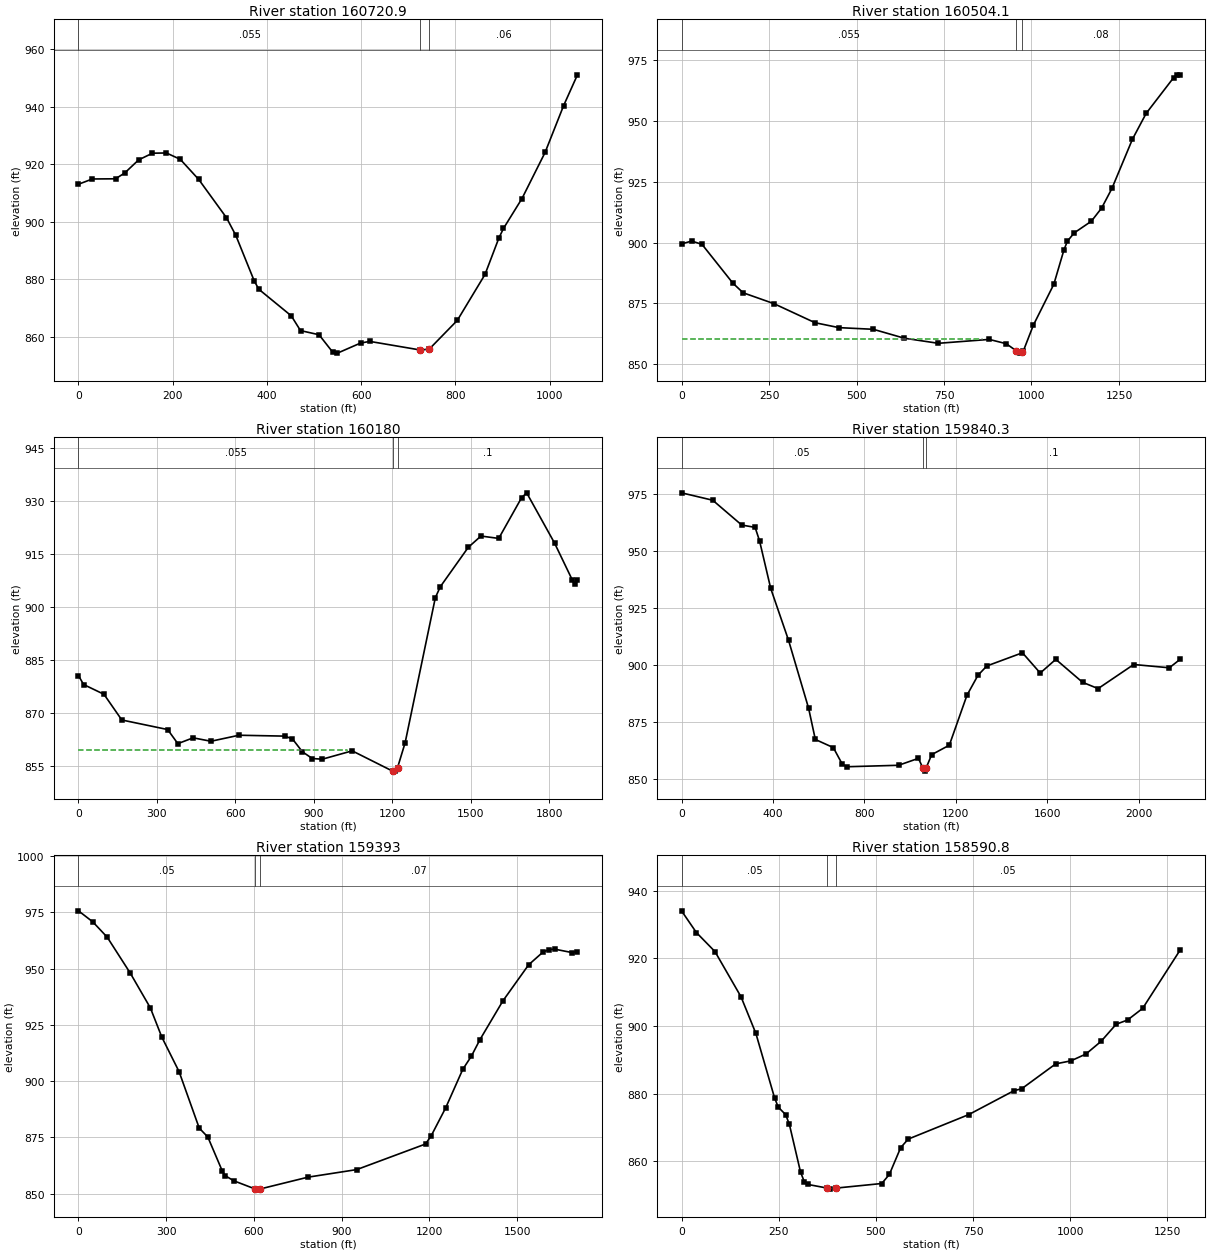
Type RM Length L Ch R = 1 ,160720.9,217.6,216.8,213.8
XS GIS Cut Line= 4
     1570090.725      317365.997     1569611.559      317162.872
     1569299.059      317143.774     1569073.364      317143.774
#Sta/Elev= 30
       0  913.07    29.5   914.9    78.6  914.96    98.2  916.99   127.7  921.55
   157.1  923.87   186.6  923.95     216  921.75   255.3  914.72   314.2  901.41
   333.9   895.3   373.2  879.37     383   876.5   451.7  867.28   471.3  862.14
   510.6   860.7     540  854.57   549.8   854.3   598.7   857.8   618.3  858.38
   725.9  855.38   744.7  855.71   804.2   865.7     863  881.68   892.4  894.34
   902.2  897.69   941.5   908.1   990.5  924.13  1029.8   940.4  1059.2  951.14
#Mann= 3 , 0 , 0
       0    .055       0   725.9    .045       0   744.7     .06       0
Bank Sta=725.9,744.7
XS Rating Curve= 0 ,0
Exp/Cntr=0.3,0.1

Type RM Length L Ch R = 1 ,160504.1,318.6,324.1,328.8
XS GIS Cut Line= 5
     1570159.863      317372.528     1569800.488      317040.931
     1569675.488      316945.445     1569199.794      316950.653
      1568897.71      316981.903
#Sta/Elev= 30
       0  899.48    29.3  900.66    58.7  899.27   146.7  883.35     176  879.39
     264  874.92   381.4  867.08   449.9  865.05     548  864.37   636.4  860.71
   733.7  858.61   879.3  860.21   927.8  858.45   956.6  855.52   966.7  854.57
   971.6  854.96   976.4  855.35  1005.5  866.11  1063.8  882.88  1092.9  897.08
  1102.6  900.59    1122  904.01    1171   908.8  1200.4  914.22  1229.8  922.27
  1288.6  942.58  1327.7  953.16  1406.1  967.84  1415.9  969.01  1425.7  968.81
#Mann= 3 , 0 , 0
       0    .055       0   956.6    .045       0   971.6     .08       0
#XS Ineff= 2 , 0
          859.71   860.5
Permanent Ineff=
       F       F
Bank Sta=956.6,971.6
XS Rating Curve= 0 ,0
Exp/Cntr=0.3,0.1

Type RM Length L Ch R = 1 ,160180  ,343.4,339.6,327.6
XS GIS Cut Line= 5
     1570263.468      317388.277     1569729.614      316768.485
     1569559.613      316684.086      1569163.78      316600.753
     1568692.426      316751.794
#Sta/Elev= 30
       0  880.64    19.5  878.12    97.4  875.36   165.6   868.1   340.8   865.4
   379.8  861.41   438.2  863.06   506.4  862.09   613.5  863.79   788.8  863.54
     818  862.74     856  859.11   893.9  857.21   931.9  857.02  1046.3  859.38
  1200.4  853.67  1210.1  853.65  1219.7  854.65  1248.6  861.66  1364.2  902.69
  1383.4  905.78    1490  916.88  1538.5  920.07  1606.4   919.4  1693.8   930.9
  1713.2  932.28  1819.9  918.07  1887.9  907.62  1897.6  906.49  1907.3  907.68
#Mann= 3 , 0 , 0
       0    .055       0  1200.4    .045       0  1219.7      .1       0
#XS Ineff= 2 , 0
         1026.95  859.58
Permanent Ineff=
       F       F
Bank Sta=1200.4,1219.7
XS Rating Curve= 0 ,0
Exp/Cntr=0.3,0.1

Type RM Length L Ch R = 1 ,159840.3,446,447.3,445.9
XS GIS Cut Line= 5
     1570358.224      316679.312     1569826.974      316484.867
     1569448.502      316377.228     1569052.669      316380.701
     1568316.558      316759.173
#Sta/Elev= 30
       0  975.56   136.6  972.31   263.4  961.44   321.9  960.42   341.4  954.51
   390.2  933.67   468.2  910.94     556  881.14   585.4  867.47   664.1   863.9
   703.4  856.62   723.1  855.51   949.4  856.15  1036.4  859.19  1055.1  855.12
  1065.4  853.59  1070.1  854.99  1094.4  860.81  1171.6  864.96  1248.8  886.85
  1297.1  895.62  1335.7  899.68  1491.4  905.46  1569.3  896.58  1637.4  902.58
  1754.3  892.53  1822.5  889.76  1978.3  900.32  2134.1  898.88  2182.8   902.7
#Mann= 3 , 0 , 0
       0     .05       0  1055.1    .045       0  1070.1      .1       0
Bank Sta=1055.1,1070.1
XS Rating Curve= 0 ,0
Exp/Cntr=0.3,0.1

Type RM Length L Ch R = 1 ,159393  ,801.8,802.2,794.2
XS GIS Cut Line= 4
     1570063.085      316071.673     1569611.697      316043.895
      1569288.78      316043.895     1568358.224       316082.09
#Sta/Elev= 30
       0  975.72    49.2  970.78    98.3  963.99     177  948.05   245.8  932.58
   285.1  919.56   344.1  904.22   412.9  879.15   442.4  875.16   491.4  860.19
   501.2  858.04   530.5  855.75   605.1  852.03   608.8  852.01   620.1  852.04
     785  857.33   951.6  860.69  1186.9  872.06  1206.5  875.77  1255.5  888.04
  1314.4  905.27  1343.8  911.12  1373.2   918.5  1451.6   935.7  1539.8  951.76
  1588.9  957.41  1608.5  958.45  1628.1   958.7  1686.9  957.19  1706.5  957.64
#Mann= 3 , 0 , 0
       0     .05       0   605.1    .045       0   620.1     .07       0
Bank Sta=605.1,620.1
XS Rating Curve= 0 ,0
Exp/Cntr=0.3,0.1

Type RM Length L Ch R = 1 ,158590.8,244.9,242.2,239.6
XS GIS Cut Line= 4
     1569786.906      315359.631     1569482.218      315390.881
     1569284.302      315414.318     1568521.281      315567.964
#Sta/Elev= 30
       0  934.04    38.3  927.62    86.1     922   153.1  908.64   191.4   897.8
   239.3  878.83   248.9  876.04     268  873.82   277.6  870.92   306.3  856.84
   315.8  854.06   325.3   853.2  375.26852.1203   382.2  851.82  397.77852.1285
   515.3  853.48   534.8  856.16     564  864.09   583.4   866.6   739.1  873.84
   855.8  880.92   875.3  881.47   962.9  888.83  1001.8  889.71  1040.7  891.74
  1079.6  895.48  1118.5  900.54  1147.7  901.78  1186.6  905.22  1283.9  922.61
#Mann= 3 , 0 , 0
       0     .05       0  375.26    .045       0  397.77     .05       0
Bank Sta=375.26,397.77
XS Rating Curve= 0 ,0
Exp/Cntr=0.3,0.1

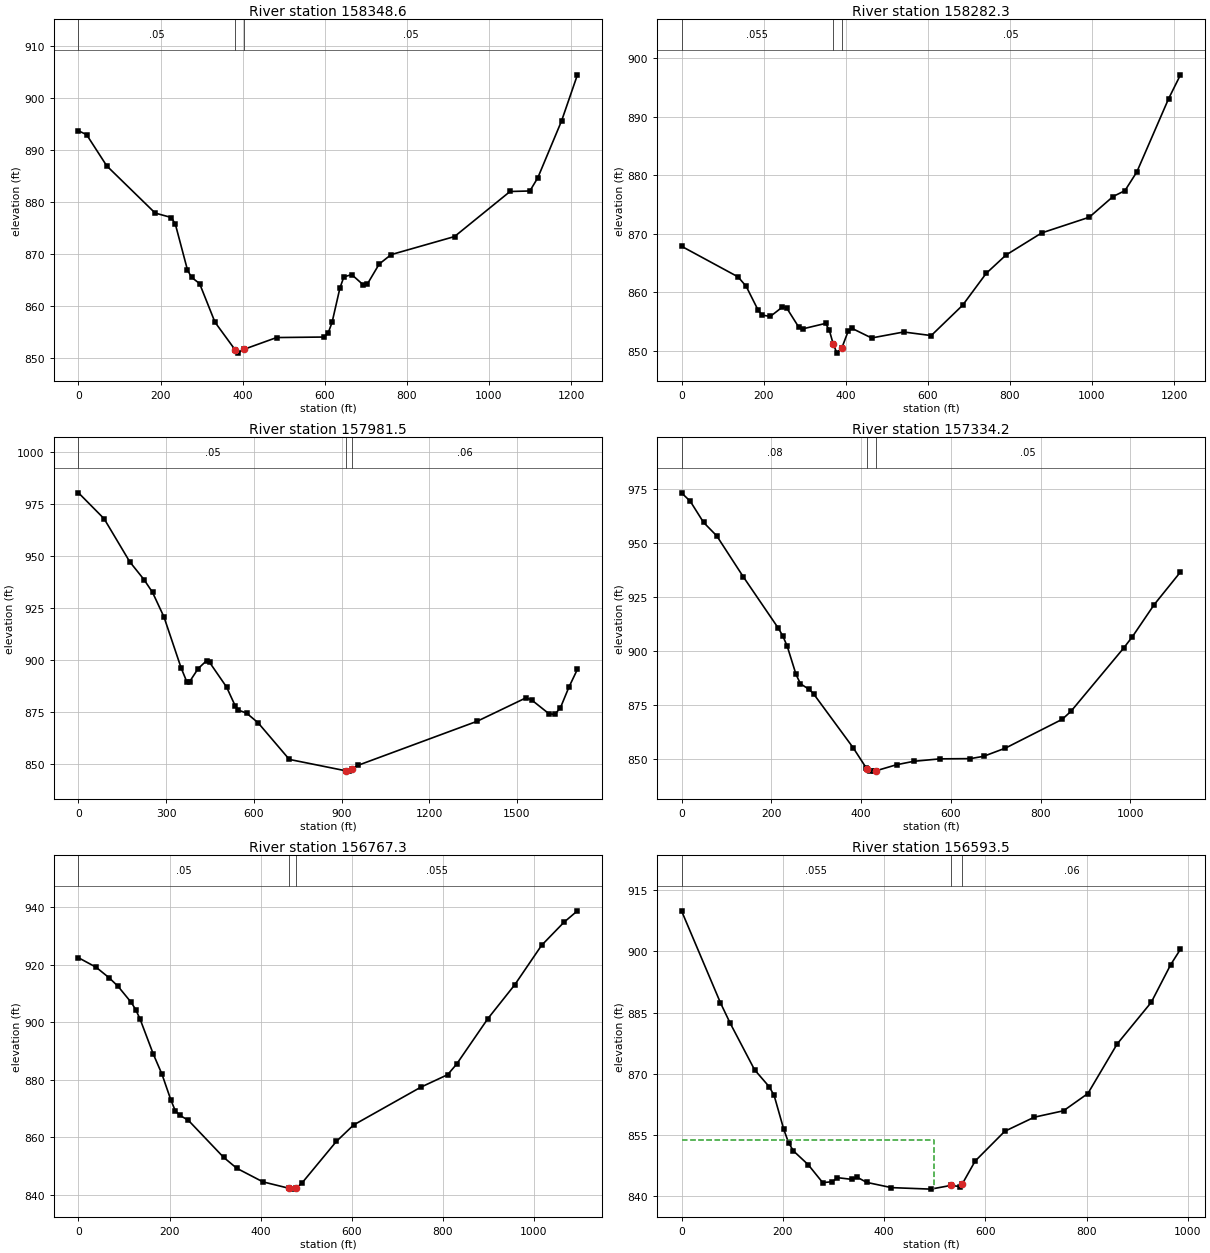
Type RM Length L Ch R = 1 ,158348.6,65.9,66.3,66.7
XS GIS Cut Line= 6
     1569776.489       315127.86     1569471.802      315140.881
     1569345.934      315168.225     1569260.864      315234.197
     1569085.517      315310.586     1568607.218       315377.86
#Sta/Elev= 30
       0  893.72    19.7  892.98    68.9  886.96   186.9  877.87   226.3  877.02
   236.1  875.71   265.6   866.9   275.4  865.51   295.1  864.29   332.6  856.85
   382.2851.4765   387.8   850.9  404.14851.6609   482.7   853.9   598.8     854
   608.4  854.79   617.9  856.84     637  863.45   646.6  865.57   665.7  866.03
   694.4  864.01     704  864.23   732.7  868.06   761.7  869.87   916.2  873.35
  1051.5  882.03  1099.8  882.13  1119.1  884.67    1177  895.62  1215.7   904.5
#Mann= 3 , 0 , 0
       0     .05       0   382.2    .045       0  404.14     .05       0
Bank Sta=382.2,404.14
XS Rating Curve= 0 ,0
Exp/Cntr=0.3,0.1

Type RM Length L Ch R = 1 ,158282.3,308.3,300.8,292.4
XS GIS Cut Line= 6
     1569770.413      315064.926     1569465.725      315077.947
     1569339.857      315105.291     1569254.788      315171.263
     1569079.441      315247.652     1568601.142      315314.926
#Sta/Elev= 30
       0  867.86   137.7  862.63   157.4  861.03   186.9  856.91   196.8  856.09
   216.4  855.87   245.9  857.48   255.8  857.36   285.3  854.08   295.1  853.74
     351  854.68   360.2   853.5   369.4   851.2   378.6   849.6  390.92850.5482
   406.2  853.37   415.4  853.83   463.1  852.19   541.4  853.21   608.4   852.6
   684.9  857.78   742.4  863.23   790.6  866.36   877.6  870.14   993.5  872.82
  1051.5  876.36  1080.4  877.36  1109.4  880.56  1186.7  893.06  1215.7  897.15
#Mann= 3 , 0 , 0
       0    .055       0   369.4    .045       0  390.92     .05       0
#XS Ineff= 2 , 0
          350.17  853.73
Permanent Ineff=
       F       F
Bank Sta=369.4,390.92
XS Rating Curve= 0 ,0
Exp/Cntr=0.3,0.1

Type RM Length L Ch R = 1 ,157981.5,647.4,647.3,645.7
XS GIS Cut Line= 4
     1570000.448      314597.044     1569314.684      314820.568
     1568919.718      315104.857     1568420.587      315111.367
#Sta/Elev= 30
       0  980.22    87.7  967.78   175.4  947.13   224.2  938.58   253.4  932.43
   292.4  920.69   350.9  896.31   370.4  889.62   380.1  889.59   409.4  895.87
   438.6  899.74   448.4  898.89   506.8  886.99   536.1  878.02   545.8  876.04
   575.1   874.5   614.1  869.94   721.3   852.3   915.9   846.8   925.7  846.68
   935.4  847.54   954.9  849.39  1364.5  870.64  1530.9  881.84  1550.5  880.82
  1609.2  874.27  1628.8  873.86  1648.4  876.91  1677.7   886.9  1707.1  895.56
#Mann= 3 , 0 , 0
       0     .05       0   915.9    .045       0   935.4     .06       0
Bank Sta=915.9,935.4
XS Rating Curve= 0 ,0
Exp/Cntr=0.3,0.1

Type RM Length L Ch R = 1 ,157334.2,560,566.9,570.6
XS GIS Cut Line= 4
     1569243.937      314209.023     1568944.458      314396.523
     1568717.896      314544.961     1568309.041      314810.586
#Sta/Elev= 30
       0  973.22    19.6  969.29    49.1  959.55    78.5  953.32   137.4  934.49
   215.9   910.6   225.7  907.08   235.6  902.29   255.2  889.26     265  884.98
   284.6  882.34   294.4  880.28   382.4  855.43   411.4  846.14   414.1  845.71
     421  844.61   429.1   844.6  432.89844.7264   479.1  847.55   517.8  849.15
   575.8  850.27   643.7  850.38     673  851.44   721.7  855.23   848.5  868.57
     868  872.29     985  901.42  1004.5  906.67  1053.2  921.55  1111.8  936.63
#Mann= 3 , 0 , 0
       0     .08       0   414.1    .045       0  432.89     .05       0
Bank Sta=414.1,432.89
XS Rating Curve= 0 ,0
Exp/Cntr=0.3,0.1

Type RM Length L Ch R = 1 ,156767.3,172.7,173.8,174.6
XS GIS Cut Line= 4
     1569053.833      314003.294     1568691.854      314107.461
     1568480.916      314193.398     1568048.625      314427.773
#Sta/Elev= 30
       0  922.39    38.6   919.1    67.6  915.38    86.9  912.45   115.9  906.84
   125.6  904.38   135.2  901.09   164.2  888.94   183.5  881.84   202.8  872.98
   212.5  869.21   222.1  867.64   241.4  865.84   318.7  852.99   347.7  849.17
   405.1  844.44   462.1  842.22   471.6  841.91     478  842.23   490.6  843.96
   566.5  858.49   604.4  864.22     752  877.36     811  881.71   830.6  885.36
   899.5  901.23   958.5  912.99  1017.5  926.72  1066.7  934.75  1096.2  938.71
#Mann= 3 , 0 , 0
       0     .05       0   462.1    .045       0     478    .055       0
Bank Sta=462.1,478
XS Rating Curve= 0 ,0
Exp/Cntr=0.3,0.1

Type RM Length L Ch R = 1 ,156593.5,61.3,61,60.7
XS GIS Cut Line= 4
     1569004.354      313761.107     1568702.271      313930.377
     1568392.375      314047.565     1568098.104      314138.711
#Sta/Elev= 30
       0  909.89      77  887.36    96.2  882.38   144.3     871   173.1  866.87
   182.8  864.78     202  856.41   211.6  853.11   221.2  851.13   250.1   847.8
   278.9  843.39   298.2  843.62   307.8  844.61   336.7  844.18   346.3  844.75
   365.8  843.45   414.5  842.17   492.4   841.8   531.4  842.69   550.9  842.44
   554.8  843.12   580.1  848.68   638.6  855.96   696.8   859.4   754.6  860.97
   802.7  865.19   860.5  877.31   927.9  887.51   966.4  896.74   985.6   900.5
#Mann= 3 , 0 , 0
       0    .055       0   531.4    .045       0   554.8     .06       0
#XS Ineff= 2 , 0
          498.33  853.82
Permanent Ineff=
       F       F
Bank Sta=531.4,554.8
XS Rating Curve= 0 ,0
Exp/Cntr=0.3,0.1

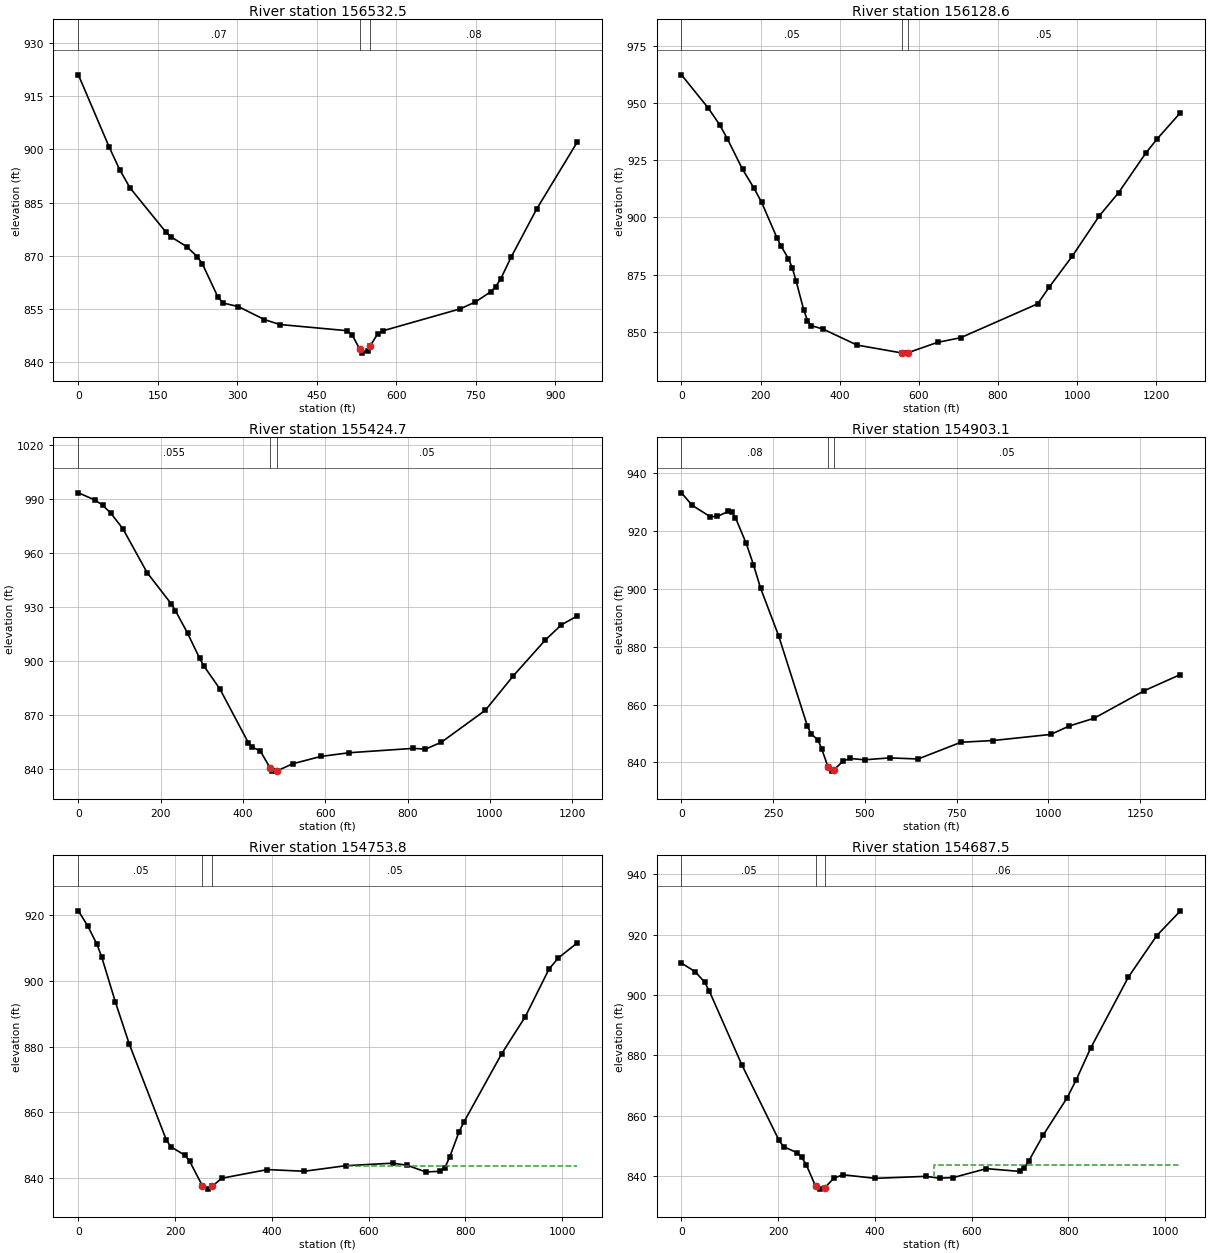
Type RM Length L Ch R = 1 ,156532.5,405.8,403.9,400.6
XS GIS Cut Line= 4
     1568960.083      313722.044     1568697.062      313870.482
     1568387.166      313987.669     1568092.896      314078.815
#Sta/Elev= 30
       0  921.04    58.4  900.58    77.9  894.32    97.4  889.17   165.6  876.61
   175.4   875.3   204.6  872.57   224.1  869.79   233.8  867.79     263  858.47
   272.8  856.71     302  855.68   350.7  852.05     380  850.64   506.6   848.9
   516.4  847.74   530.7  843.73   535.9  842.57   545.6  843.23  550.41844.5807
   565.1   848.1   574.9  848.88     720  855.04   748.8  856.97   777.7  859.85
   787.4  861.31     797  863.58   816.2  869.56   864.4  883.15   941.4  902.14
#Mann= 3 , 0 , 0
       0     .07       0   530.7    .045       0  550.41     .08       0
Bank Sta=530.7,550.41
XS Rating Curve= 0 ,0
Exp/Cntr=0.3,0.1

Type RM Length L Ch R = 1 ,156128.6,694.7,703.9,710.2
XS GIS Cut Line= 4
     1568741.333      313367.877     1568350.708      313578.815
     1568100.708      313706.419     1567585.083      313854.857
#Sta/Elev= 30
       0  962.37    67.6  947.88    96.5  940.53   115.8  934.48   154.4  921.05
   183.4   912.8   202.7  906.59   241.3  891.13   250.9  887.74   270.2  882.03
   279.9   878.1   289.5  872.36   308.8  859.75   318.5  854.91   328.1  852.69
   357.1  851.26   443.9  844.21   557.4  840.75   560.1  840.69   572.4  840.86
   647.2   845.4   705.3  847.41   900.2  862.24   929.5  869.56     988  883.14
  1056.3  900.75  1105.1  910.91  1173.4  928.12  1202.6  934.42  1261.2  945.83
#Mann= 3 , 0 , 0
       0     .05       0   557.4    .045       0   572.4     .05       0
Bank Sta=557.4,572.4
XS Rating Curve= 0 ,0
Exp/Cntr=0.3,0.1

Type RM Length L Ch R = 1 ,155424.7,523.7,521.6,518.5
XS GIS Cut Line= 4
     1568598.972       312906.94     1568187.514      313003.294
      1567885.43      313039.752     1567403.659      313102.252
#Sta/Elev= 30
       0  993.51    39.3  989.62      59  986.65    78.6  982.25   108.1  973.55
   167.1  949.05     226   931.6   235.9   927.9   265.4  915.36   294.8  901.29
   304.7  897.19     344  884.28   412.8  854.46   422.6  851.94   442.2  849.71
   466.4  840.17   471.7  838.72   481.4  838.54     483838.6903   520.7  842.63
   589.4  846.72   658.2  848.78   814.3  851.22   843.5  850.78   882.3  854.65
   989.2  872.46  1057.2  891.66  1134.9  911.58  1173.8  919.98  1212.7  924.97
#Mann= 3 , 0 , 0
       0    .055       0   466.4    .045       0     483     .05       0
Bank Sta=466.4,483
XS Rating Curve= 0 ,0
Exp/Cntr=0.3,0.1

Type RM Length L Ch R = 1 ,154903.1,136.5,149.3,162.1
XS GIS Cut Line= 4
     1568447.062      312498.086     1568113.729      312485.065
     1567697.062      312584.023     1567186.646      312896.523
#Sta/Elev= 30
       0  933.26    29.4  928.91    78.5  925.01    98.1  925.11   127.6  926.84
   137.4  926.56   147.2  924.67   176.6  915.74   196.2  908.44   215.8  900.24
   264.9   883.8   343.3  852.58     353  849.97   372.5   847.7   382.2  844.73
   400.1  838.26   411.4     837   415.1  837.35   440.6   840.5   460.1  841.38
     499  840.91   567.2  841.58     645   841.2   761.8  846.98   850.2  847.59
  1007.1   849.7  1056.2  852.57  1124.9  855.29  1262.2  864.85  1360.3  870.42
#Mann= 3 , 0 , 0
       0     .08       0   400.1    .045       0   415.1     .05       0
Bank Sta=400.1,415.1
XS Rating Curve= 0 ,0
Exp/Cntr=0.3,0.1

Type RM Length L Ch R = 1 ,154753.8,66.6,66.4,66.1
XS GIS Cut Line= 5
     1568259.562      312422.565     1568053.833       312375.69
     1567874.146      312315.794     1567717.896      312274.127
     1567249.146      312302.773
#Sta/Elev= 30
       0  921.33    19.2  916.76    38.4  911.15      48  907.39    76.7  893.49
   105.5  880.66   182.2  851.44   191.8  849.44   220.5   846.9   229.9  845.12
   256.6  837.56   267.8   836.6   277.3  837.52   296.2  839.91   390.9  842.55
     467  842.04   552.6  843.73   650.2   844.5   679.5  843.87   718.7  841.82
     748  842.03   757.8  843.14   767.6  846.34   787.2  854.09   796.9  856.98
   875.2  877.82   924.1  889.12     973  903.58   992.6  907.03  1031.7  911.58
#Mann= 3 , 0 , 0
       0     .05       0   256.6    .045       0   277.3     .05       0
#XS Ineff= 2 , 0
                          556.09          843.78
Permanent Ineff=
       F       F
Bank Sta=256.6,277.3
XS Rating Curve= 0 ,0
Exp/Cntr=0.3,0.1

Type RM Length L Ch R = 1 ,154687.5,358,351.8,344.9
XS GIS Cut Line= 5
     1568289.293      312364.188     1568083.564      312317.313
     1567903.876      312257.417     1567747.626      312215.751
     1567278.876      312244.397
#Sta/Elev= 30
       0  910.56    28.8  907.64      48  904.19    57.6  901.27   124.7  876.93
   201.4  851.97     211   849.8   239.4  847.74   248.9   846.2   258.4  843.67
   277.3  836.69   286.8  835.73   296.2  836.16   315.2  839.38   334.1  840.48
   400.4   839.3     505  839.96   533.6  839.35   562.1  839.57   630.6  842.51
   699.1   841.6   708.9  842.86   718.7  845.19     748  853.65   796.9  865.84
   816.5     872   845.8  882.34   924.1  905.93   982.8  919.66  1031.7  927.84
#Mann= 3 , 0 , 0
       0     .05       0   277.3    .045       0   296.2     .06       0
#XS Ineff= 2 , 0
                          521.78          843.82
Permanent Ineff=
       F       F
Bank Sta=277.3,296.2
XS Rating Curve= 0 ,0
Exp/Cntr=0.3,0.1

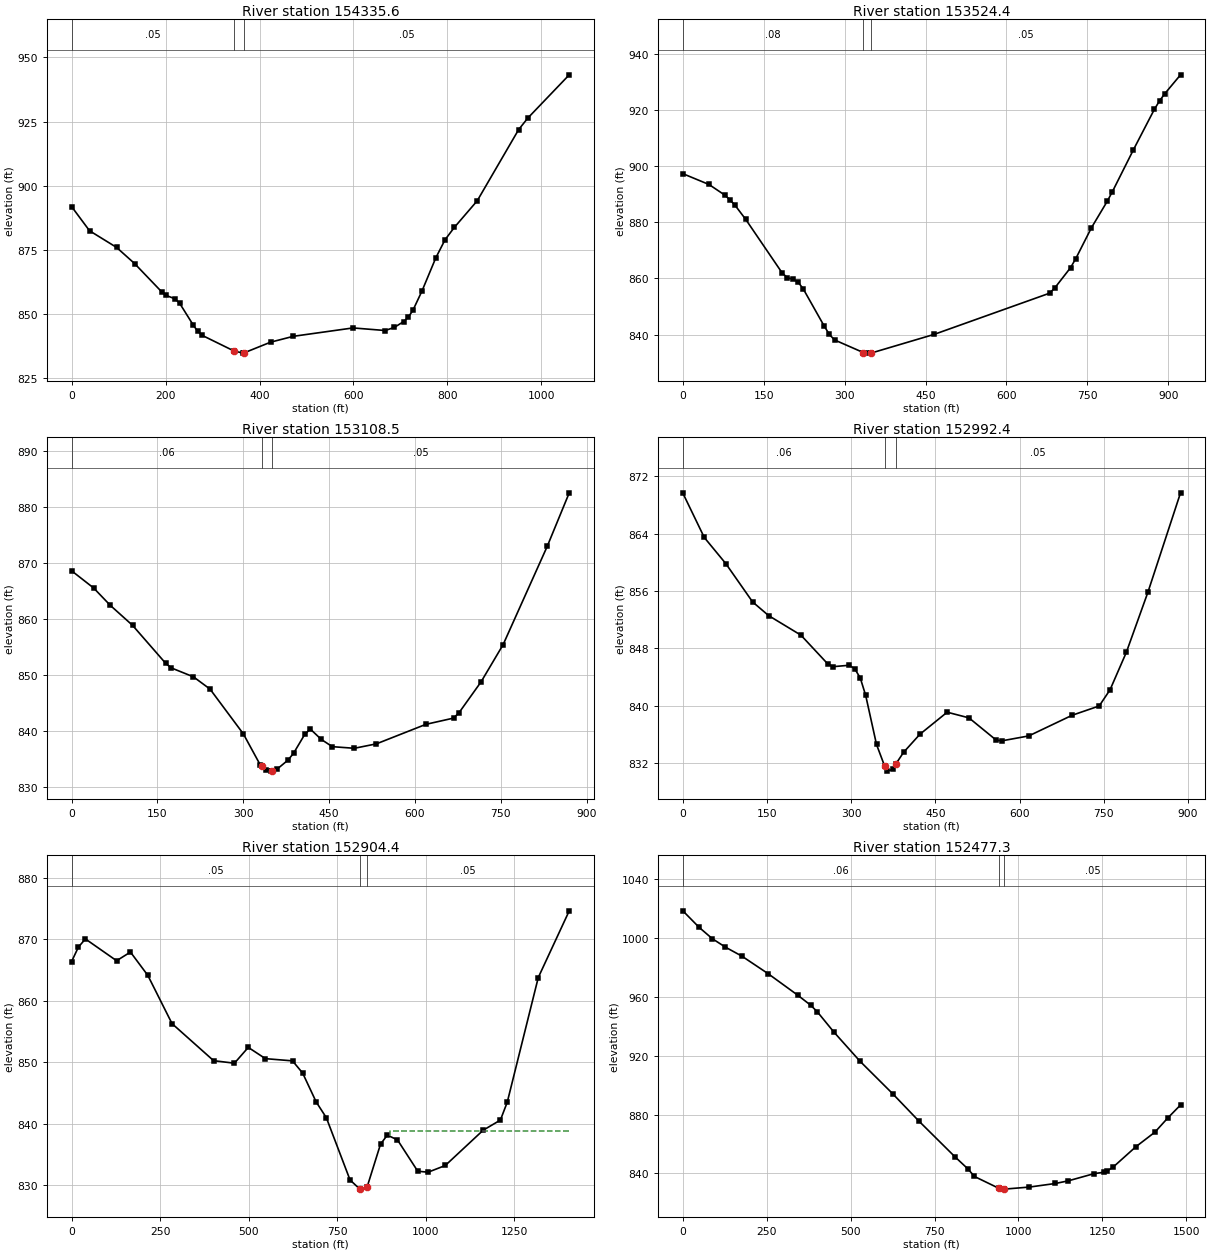
Type RM Length L Ch R = 1 ,154335.6,811.2,811.2,810.5
XS GIS Cut Line= 4
     1568449.666       312000.69     1568173.625       311969.44
     1567921.021      311961.627     1567392.375      311953.815
#Sta/Elev= 30
       0  891.88    38.3  882.44    95.8  875.95   134.1  869.67   191.6  858.68
   201.2  857.24   220.3  855.91   229.9  854.22   258.6  845.81   268.2  843.31
   277.8  841.69   345.8  835.58   365.3  834.75  366.66834.8173   423.6  839.02
   472.2  841.31   599.1  844.57   667.6  843.56   687.2  844.81   706.8  847.04
   716.6  848.74   726.4   851.4   745.9     859   775.3  871.92   794.9  878.94
   814.5  883.71   863.4  894.13   951.5  921.86   971.1  926.37  1059.2  943.21
#Mann= 3 , 0 , 0
       0     .05       0   345.8    .045       0  366.66     .05       0
Bank Sta=345.8,366.66
XS Rating Curve= 0 ,0
Exp/Cntr=0.3,0.1

Type RM Length L Ch R = 1 ,153524.4,392.7,415.9,440.1
XS GIS Cut Line= 4
     1568498.278      311277.166     1568235.691      311207.721
     1567953.573      311205.551     1567584.649      311203.381
#Sta/Elev= 30
       0  897.29    48.5  893.44    77.6  889.69    87.3     888      97  885.98
   116.4  881.07   184.3  861.91     194  860.24   203.7  859.74   213.4  858.76
   223.1  856.31   261.9   843.1   271.6  840.08   281.3   838.1   334.6  833.62
   339.7  833.41   349.6  833.46   466.2   840.1     680  854.75   689.7  856.65
   718.8  863.83   728.5  867.06   757.6  878.07   786.8  887.46   796.5  890.94
   835.3  905.78   874.1  920.16   883.8  923.22   893.5  925.77   922.7  932.48
#Mann= 3 , 0 , 0
       0     .08       0   334.6    .045       0   349.6     .05       0
Bank Sta=334.6,349.6
XS Rating Curve= 0 ,0
Exp/Cntr=0.3,0.1

Type RM Length L Ch R = 1 ,153108.5,119.1,116.1,113.5
XS GIS Cut Line= 5
     1568489.597      311057.982     1568280.396      310885.673
     1568174.927      310784.544     1568033.868      310754.162
     1567725.708      310751.992
#Sta/Elev= 30
       0  868.61    38.7  865.52    67.8  862.42   106.5  858.87   164.6  852.06
   174.2  851.26     213  849.66     242  847.47   300.2  839.47   329.5  833.97
   332.4   833.7   339.2  833.08     349  832.82  351.02832.8867   358.7  833.14
   378.2  834.79   387.9  836.01   407.4  839.37   417.2  840.33   436.4  838.48
   455.6  837.19   494.1   836.9   532.6  837.69   619.2  841.18   667.4  842.29
     677  843.25   715.5  848.76     754   855.4   831.1  872.96   869.6  882.53
#Mann= 3 , 0 , 0
       0     .06       0   332.4    .045       0  351.02     .05       0
#XS Ineff= 2 , 0
                          416.39          839.63
Permanent Ineff=
       F       F
Bank Sta=332.4,351.02
XS Rating Curve= 0 ,0
Exp/Cntr=0.3,0.1

Type RM Length L Ch R = 1 ,152992.4,105.8,88,68.4
XS GIS Cut Line= 5
     1568509.128      310958.155     1568302.531      310788.016
     1568191.854      310694.266     1568048.625      310668.225
       1567720.5      310678.641
#Sta/Elev= 30
       0  869.64    38.2  863.45    76.5  859.81   124.3  854.46   152.9  852.55
   210.3  849.83   258.1  845.82   267.6  845.43   296.6  845.63   306.3  845.12
     316  843.87   325.7  841.43     345  834.58  359.31831.5977   364.3  830.86
     374  831.11  379.29831.8394   393.3  833.49   422.4  836.01   470.9  839.08
   509.7  838.29   558.3  835.18   567.9  835.08   616.2  835.77   693.4  838.65
   741.7  839.95     761   842.2     790  847.42   828.6  855.84   886.6  869.68
#Mann= 3 , 0 , 0
       0     .06       0  359.31    .045       0  379.29     .05       0
#XS Ineff= 2 , 0
                          463.21          838.46
Permanent Ineff=
       F       F
Bank Sta=359.31,379.29
XS Rating Curve= 0 ,0
Exp/Cntr=0.3,0.1

Type RM Length L Ch R = 1 ,152904.4,441.5,427.1,412.1
XS GIS Cut Line= 5
      1569006.09      310836.627     1568500.622      310681.663
     1568294.458       310640.43     1568055.569      310628.294
     1567628.052      310647.825
#Sta/Elev= 30
       0  866.38    19.6  868.76    39.2  870.06   127.3  866.52   166.4  867.93
   215.4  864.15   283.9   856.3   401.4  850.28   460.2  849.87   499.3  852.44
   547.8  850.61   624.3  850.25   652.9  848.27   691.2  843.57   719.8  841.02
   786.8   830.9  813.87829.4456   815.5  829.41   834.6  829.68   872.9  836.71
     892  838.18   920.7  837.42   978.1  832.32  1007.3  832.16  1055.9  833.25
  1162.9  838.98  1211.6  840.63    1231  843.54  1318.6  863.79  1406.1  874.63
#Mann= 3 , 0 , 0
       0     .05       0  813.87    .045       0   834.6     .05       0
#XS Ineff= 2 , 0
                          899.52          838.85
Permanent Ineff=
       F       F
Bank Sta=813.87,834.6
XS Rating Curve= 0 ,0
Exp/Cntr=0.3,0.1

Type RM Length L Ch R = 1 ,152477.3,551.9,556.3,555
XS GIS Cut Line= 4
     1568817.896      309957.704     1568025.296      310263.602
     1567754.028      310448.064     1567541.355      310667.248
#Sta/Elev= 30
       0 1018.64    48.8 1007.33    87.9  999.67     127  993.91   175.8  987.82
   253.9   975.9   341.8  961.33   380.8  954.43   400.4  950.01   449.2  936.37
   527.3  916.43     625  894.23   703.1  875.63   810.5  851.33   849.6  842.98
   868.9  837.86   941.7  829.81   955.7  829.25  958.31829.2537  1032.9  830.66
  1110.1  833.09  1148.7   834.9  1225.3  839.78    1254  840.72  1263.5  841.45
  1282.6  844.32  1349.4     858  1406.7  868.03  1444.8  877.63    1483  886.51
#Mann= 3 , 0 , 0
       0     .06       0   941.7    .045       0  958.31     .05       0
Bank Sta=941.7,958.31
XS Rating Curve= 0 ,0
Exp/Cntr=0.3,0.1