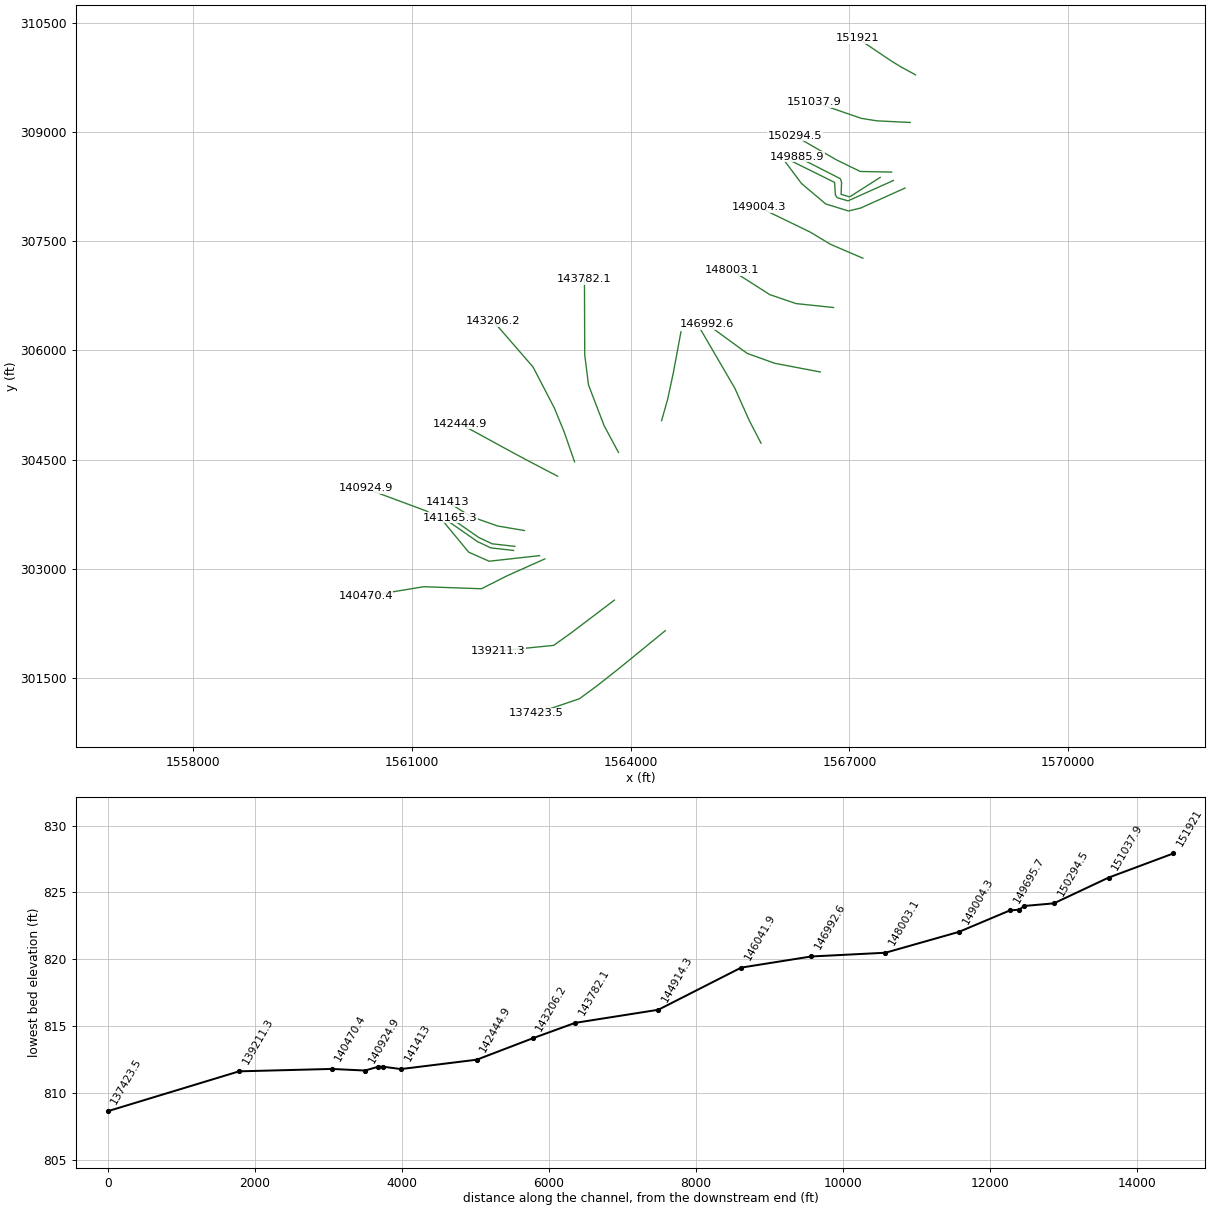
HEC-RAS study NFHGHSRV1.prj: NFHGHSRV1

--- NFHGHSRV1.g01 (geometry) --- (continued)

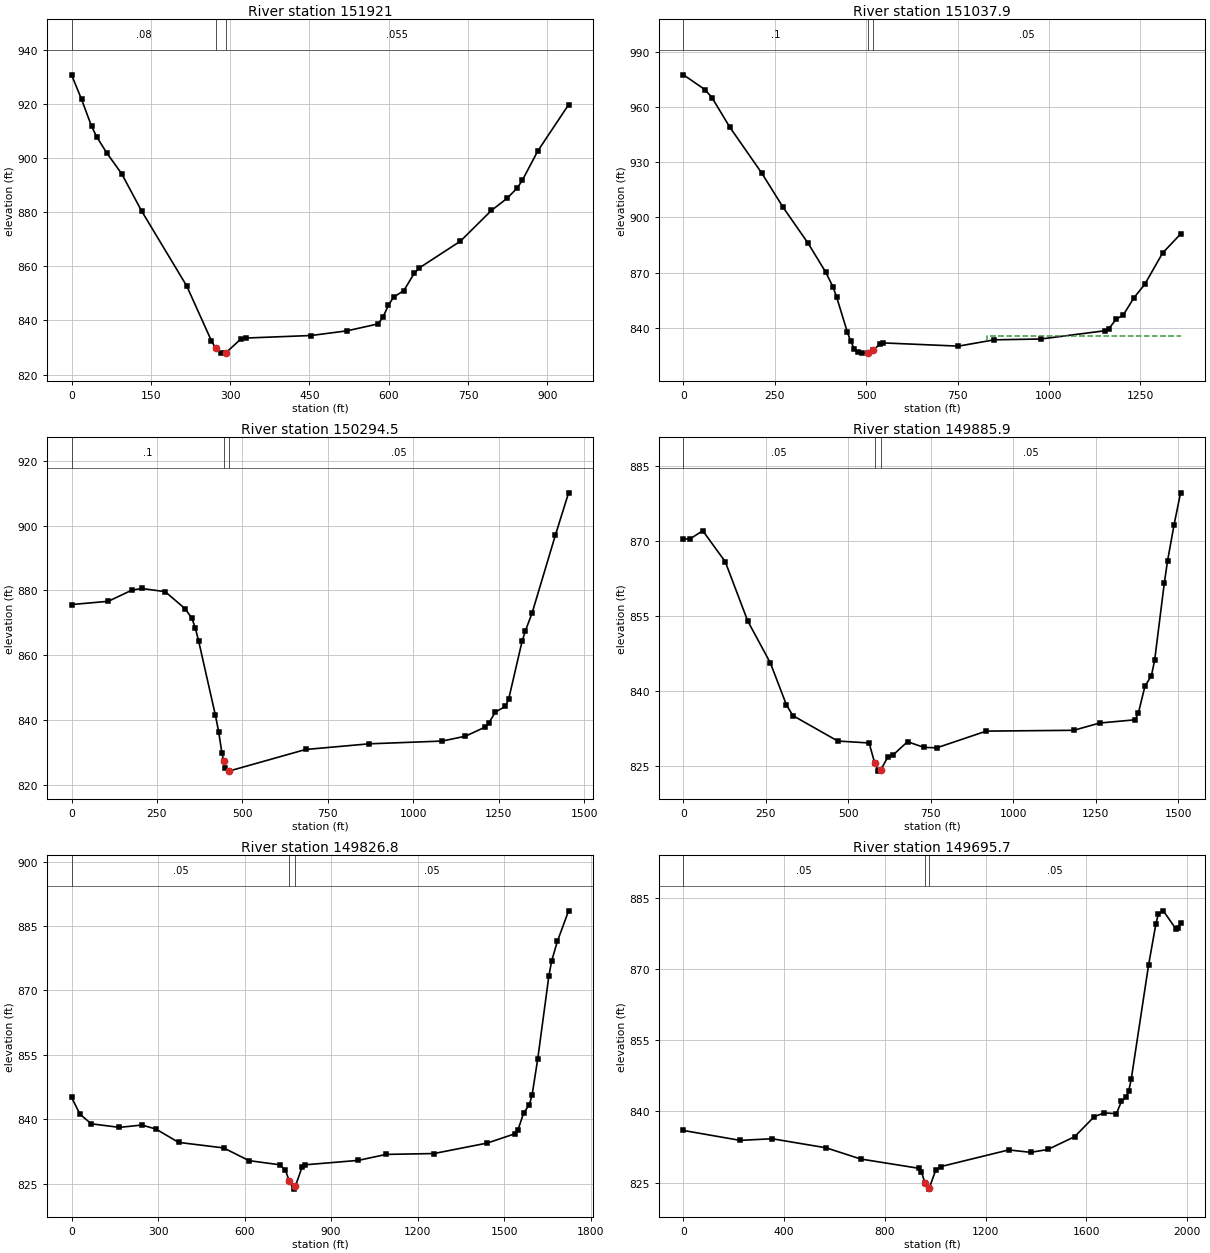
Type RM Length L Ch R = 1 ,151921  ,872.2,883.1,891.1
XS GIS Cut Line= 4
     1567908.108      309784.002     1567708.455      309892.509
     1567573.907      309974.974     1567113.837      310285.304
#Sta/Elev= 30
       0  930.72    18.9  921.71    37.9  911.73    47.3  907.93    66.3  901.97
    94.7  894.22   132.6   880.4   217.8  852.74   264.4  832.54   272.6  829.66
   282.9  827.92   292.2   828.1   320.1  833.12   329.4  833.49   453.2  834.43
   521.4  836.17   579.8  838.72   589.5  841.42   599.2  845.57     609  848.61
   628.4  851.01   647.9  857.35   657.6  859.38   735.5  869.29     794  880.61
   823.2  885.04   842.6  888.85   852.4  891.71   881.6  902.55     940  919.68
#Mann= 3 , 0 , 0
       0     .08       0   272.6    .045       0   292.2    .055       0
Bank Sta=272.6,292.2
XS Rating Curve= 0 ,0
Exp/Cntr=0.3,0.1

Type RM Length L Ch R = 1 ,151037.9,749.3,743.4,735.7
XS GIS Cut Line= 4
     1567835.257      309129.579      1567378.16      309152.057
     1567164.619      309185.911     1566516.181       309409.87
#Sta/Elev= 30
       0  977.63    58.4  969.62    77.9  965.26   126.6  949.16   214.2  924.11
   272.6  905.47   340.8  885.96   389.5  870.07     409  862.14   418.7  856.79
   447.9  837.81   457.6  832.48   467.5  828.45   477.3  826.51   487.1  826.11
   504.4  826.26   519.4  827.64   536.3  830.95   546.1  831.68   752.3  829.92
   850.3  833.36   977.7   833.8  1154.1  838.32  1163.9  839.47  1183.5  844.54
  1203.1  846.85  1232.5  856.29  1261.9  863.56  1310.9  880.64  1359.9  890.95
#Mann= 3 , 0 , 0
       0      .1       0   504.4    .045       0   519.4     .05       0
#XS Ineff= 2 , 0
                          831.38          835.21
Permanent Ineff=
       F       F
Bank Sta=504.4,519.4
XS Rating Curve= 0 ,0
Exp/Cntr=0.3,0.1

Type RM Length L Ch R = 1 ,150294.5,404.9,408.6,412
XS GIS Cut Line= 4
     1567579.181      308448.156     1567148.994      308456.745
     1566823.473      308615.599     1566250.556      308946.328
#Sta/Elev= 30
       0  875.62   107.6  876.63     176  880.05   205.4  880.58   273.8  879.61
   332.5  874.32     352  871.42   361.8  868.47   371.6  864.48   420.5   841.6
   430.3  836.41   440.1  829.66   445.4  827.26   449.8  825.26   459.6  824.19
   460.4   824.2   684.8  830.87   870.3  832.62  1084.3  833.47  1152.4  834.98
  1210.8  837.84  1220.5  839.02    1240  842.47  1269.2  844.15  1278.9  846.52
  1317.8  864.23  1327.5  867.48    1347  872.93  1415.1  896.97    1454  910.12
#Mann= 3 , 0 , 0
       0      .1       0   445.4    .045       0   460.4     .05       0
Bank Sta=445.4,460.4
XS Rating Curve= 0 ,0
Exp/Cntr=0.3,0.1

Type RM Length L Ch R = 1 ,149885.9,59,59.1,59.1
XS GIS Cut Line= 6
     1567422.714      308375.022     1567003.594      308107.786
     1566886.407      308142.509     1566892.917      308308.307
     1566875.556      308357.352     1566280.938      308661.172
#Sta/Elev= 30
       0  870.33    19.5  870.34    58.5  871.98   126.7  865.79   194.9  853.95
   263.2  845.63   311.9  837.27   331.4  835.09   467.8     830   562.9  829.61
  579.64825.6921   591.1  823.99  598.53824.2842   619.3  826.74   635.5  827.21
   679.5  829.86   728.7  828.74   768.1  828.64   918.3  831.98  1183.5  832.14
    1262  833.59    1370  834.24  1379.9  835.68  1399.5  840.96  1419.1  843.03
    1429  846.18  1458.4  861.64  1468.2  866.03  1487.9  873.21  1507.5  879.55
#Mann= 3 , 0 , 0
       0     .05       0  579.64    .045       0  598.53     .05       0
Bank Sta=579.64,598.53
XS Rating Curve= 0 ,0
Exp/Cntr=0.3,0.1

Type RM Length L Ch R = 1 ,149826.8,131.4,131.2,130.7
XS GIS Cut Line= 6
     1567605.005      308333.355     1566981.459      308053.099
     1566833.889      308096.502     1566807.848      308134.696
     1566797.431      308306.571     1566204.549      308600.408
#Sta/Elev= 30
       0  845.11    29.3  841.17    68.4  838.94     166  838.11   244.2  838.65
     293  837.71   371.1  834.61   527.4  833.32   615.3  830.36   722.1  829.39
   741.3  828.18  754.57825.6782   770.2  823.72  776.48824.4769     799  828.79
   808.6  829.38   994.3  830.42  1090.8  831.81  1256.3  832.01  1441.2  834.45
  1538.5  836.64  1548.2  837.59  1567.6  841.47  1587.1  843.36  1596.8  845.65
  1616.3  854.02  1655.2  873.48    1665  876.97  1684.4  881.43  1723.4  888.56
#Mann= 3 , 0 , 0
       0     .05       0  754.57    .045       0  776.48     .05       0
Bank Sta=754.57,776.48
XS Rating Curve= 0 ,0
Exp/Cntr=0.3,0.1

Type RM Length L Ch R = 1 ,149695.7,697,691.4,673.4
XS GIS Cut Line= 6
     1567763.642      308228.972      1567157.74      307955.534
     1566988.469      307913.868     1566675.969      308010.222
     1566342.636      308291.472     1566120.348      308589.991
#Sta/Elev= 30
       0     836   224.8  833.92   351.9  834.26     567  832.35   703.5     830
   935.2  828.04   944.9  827.35  958.81824.9912   973.7  823.66   976.9  823.99
  1002.6  827.75  1021.8   828.4  1292.1  831.91  1379.3   831.4  1447.2     832
  1553.8   834.7  1631.6  838.91  1670.8   839.7  1719.8  839.54  1739.3  842.11
  1758.9     843  1768.7  844.37  1778.5  846.79  1847.1  870.74  1876.5   879.5
  1886.3  881.58  1905.8  882.22  1954.8   878.5  1964.6  878.56  1974.4  879.61
#Mann= 3 , 0 , 0
       0     .05       0  958.81    .045       0   976.9     .05       0
Bank Sta=958.81,976.9
XS Rating Curve= 0 ,0
Exp/Cntr=0.3,0.1

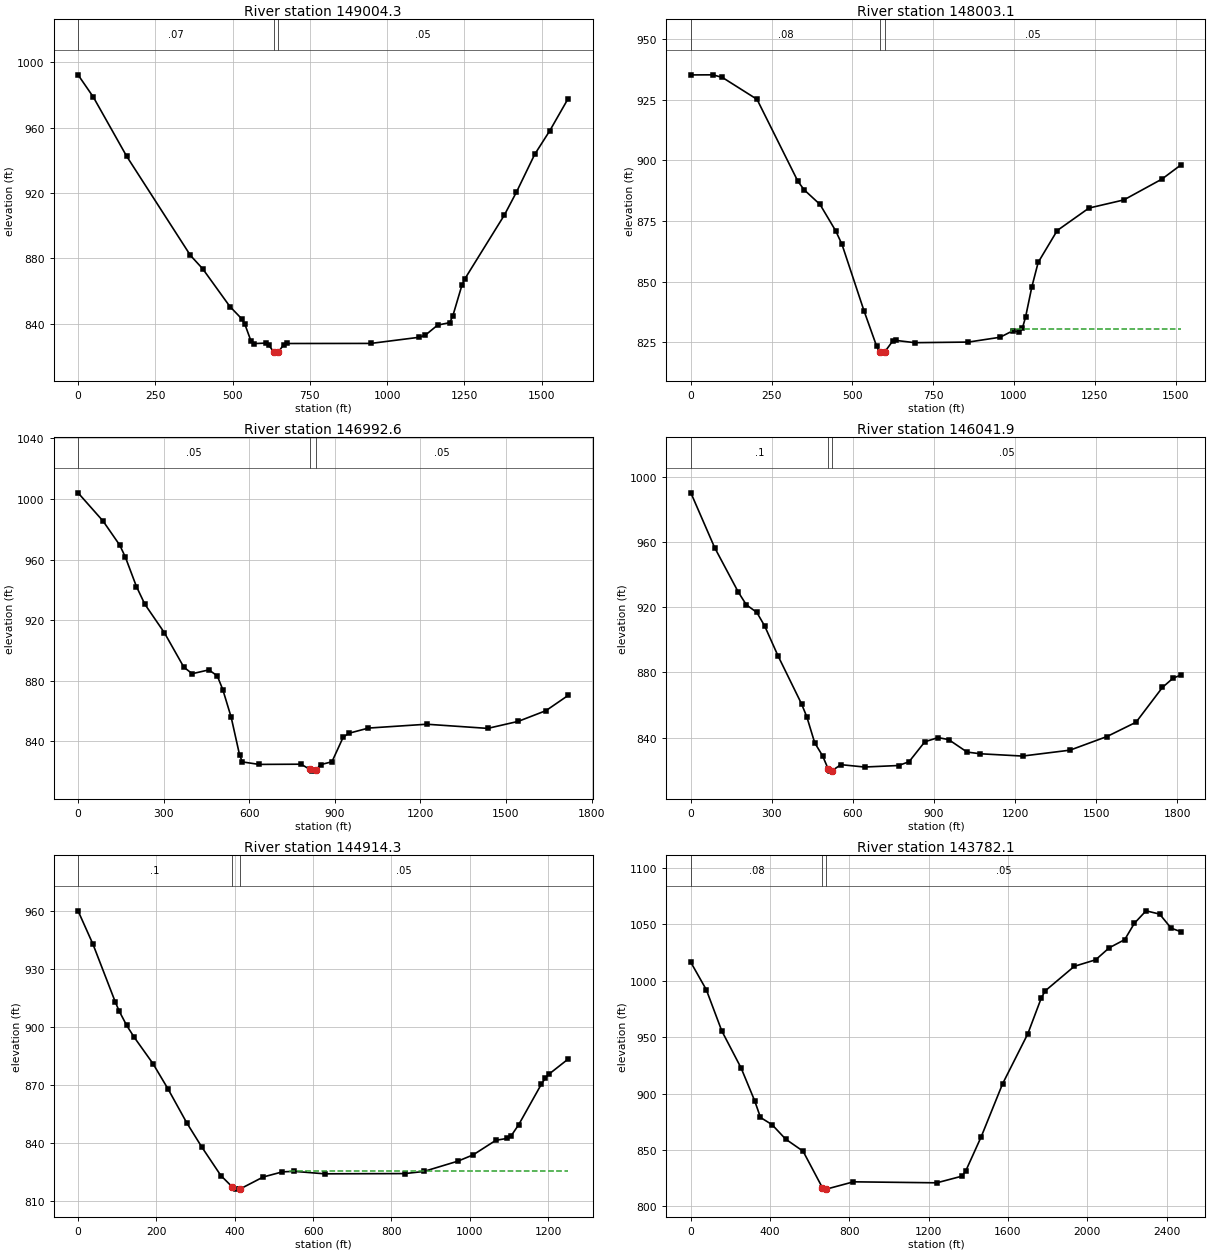
Type RM Length L Ch R = 1 ,149004.3,995.6,1001.2,1005
XS GIS Cut Line= 4
     1567185.452      307265.338     1566742.744      307455.443
     1566461.494      307624.713     1565763.577      307963.255
#Sta/Elev= 30
       0  992.29    49.2  978.77   157.3  942.49   363.8   881.8   403.1  873.71
   491.4  850.56   530.1  842.97   539.7   839.8     559  829.78   568.7  827.88
   607.3   828.2     617     827   633.4  822.74   645.9  822.06   648.4  822.71
   665.2  827.23   674.9  827.95   947.5     828  1104.6  831.77  1124.3  833.12
  1163.5  839.19  1202.8  840.72  1212.6  844.73  1242.1  863.54  1251.9  867.55
  1379.6  906.52  1418.8   920.6  1477.7  943.63  1526.8  958.18  1585.8  977.71
#Mann= 3 , 0 , 0
       0     .07       0   633.4    .045       0   648.4     .05       0
Bank Sta=633.4,648.4
XS Rating Curve= 0 ,0
Exp/Cntr=0.3,0.1

Type RM Length L Ch R = 1 ,148003.1,1009.1,1010.5,1009.1
XS GIS Cut Line= 4
     1566782.493      306588.185     1566268.785      306642.074
     1565907.493      306765.269      1565386.66      307098.602
#Sta/Elev= 30
       0  935.26    68.2   935.3    97.5  934.22   204.7   925.2   331.4  891.34
   350.8  887.84   399.6  881.85   448.3  870.93   467.8  865.32   536.1  837.86
   575.2  823.25   584.8  820.95   594.8   820.5   599.8  820.98   624.2  825.39
     634  825.76   692.7  824.81   859.1  825.06   957.1  827.05   996.4  829.72
    1016  829.21  1025.8  830.71  1035.7  835.28  1055.3  847.85  1074.9  857.94
  1133.8  871.07    1232  880.34  1339.9  883.69  1457.7  892.28  1516.6  898.13
#Mann= 3 , 0 , 0
       0     .08       0   584.8    .045       0   599.8     .05       0
#XS Ineff= 2 , 0
                          990.56          830.51
Permanent Ineff=
       F       F
Bank Sta=584.8,599.8
XS Rating Curve= 0 ,0
Exp/Cntr=0.3,0.1

Type RM Length L Ch R = 1 ,146992.6,968.3,950.7,932.6
XS GIS Cut Line= 4
     1566600.201      305702.769     1565977.119      305821.762
     1565597.597      305957.977     1565048.118      306359.019
#Sta/Elev= 30
       0 1004.05    87.8  985.37   146.4  969.43   165.9  961.57   204.9  942.05
   234.2  930.46   302.5  911.68   370.8   888.9   400.1  884.57   458.7   887.1
     488  883.14   507.5  874.02   536.8  855.79     566  831.09   575.8  826.32
   634.3  824.66   781.9   824.8   811.4  821.49   821.2  820.22   834.5  821.12
   850.7  824.52     890  826.39   929.4  842.63   949.1  845.21  1017.9  848.66
  1222.2   851.2    1436  848.45  1542.9  853.08  1640.1  860.16  1717.8  870.21
#Mann= 3 , 0 , 0
       0     .05       0   811.4    .045       0   834.5     .05       0
Bank Sta=811.4,834.5
XS Rating Curve= 0 ,0
Exp/Cntr=0.3,0.1

Type RM Length L Ch R = 1 ,146041.9,1141.1,1127.6,1111.9
XS GIS Cut Line= 4
     1565787.014      304725.408     1565625.556      305037.908
     1565427.639      305480.616     1564936.139      306325.165
#Sta/Elev= 30
       0  990.32    87.9  956.72   175.9  929.26   205.2  921.58   244.3  916.84
   273.6  908.41   322.4  890.26   409.9  860.61   429.3  852.68   458.4  836.77
   487.5  828.81   508.2  820.76   516.6  819.39   523.2  819.74   555.4  823.36
   642.7  821.91   768.8  822.84   807.6  825.16     866  837.42   914.8  839.97
   953.9  838.78  1022.3   831.1  1071.2  830.05  1227.5  828.64  1403.4  832.27
  1540.2  840.64  1647.7  849.42  1745.4  870.81  1784.5  876.44  1813.8  878.44
#Mann= 3 , 0 , 0
       0      .1       0   508.2    .045       0   523.2     .05       0
Bank Sta=508.2,523.2
XS Rating Curve= 0 ,0
Exp/Cntr=0.3,0.1

Type RM Length L Ch R = 1 ,144914.3,1118.3,1132.2,1144.6
XS GIS Cut Line= 4
     1564423.299      305033.568     1564506.451      305327.769
     1564584.758      305692.422     1564688.924      306254.922
#Sta/Elev= 30
       0  960.02    38.2  942.72    95.5   912.7   105.1  908.19   124.2  900.79
   143.3  894.71   191.1  881.12   229.3  868.13   277.1  850.62   315.5  838.09
   364.6  823.23   394.1  817.28   403.9  816.24   413.7  816.33   472.6  822.51
   521.6  825.16   551.1  825.43   629.6  824.15   833.8  824.27   882.3  825.35
   969.6   830.7  1008.4  833.94  1066.5  841.48  1095.6  842.45  1105.3  843.72
  1124.7  849.53  1182.9  870.57  1192.6  873.54  1202.3  875.69  1250.8  883.42
#Mann= 3 , 0 , 0
       0      .1       0   394.1    .045       0   413.7     .05       0
#XS Ineff= 2 , 0
                          540.57          825.47
Permanent Ineff=
       F       F
Bank Sta=394.1,413.7
XS Rating Curve= 0 ,0
Exp/Cntr=0.3,0.1

Type RM Length L Ch R = 1 ,143782.1,575.3,575.9,576.2
XS GIS Cut Line= 5
     1563831.972      304596.866     1563634.056      304966.658
     1563420.514      305523.949     1563368.431      305940.616
     1563364.958      306977.074
#Sta/Elev= 30
       0 1016.32      78  992.07   156.1  955.53   253.6  922.65   321.9  893.64
   351.2  878.82   409.7  872.43   478.1  859.63   566.2  848.88     664  816.42
   682.9  815.26   683.6  815.26   820.6  821.74  1240.8  820.86  1367.8  826.75
  1387.3  831.53  1465.5  861.92    1573  908.71  1700.1     953  1768.6  984.98
  1788.1   991.1  1934.8 1012.84  2042.4 1018.62  2110.8 1029.24    2189 1036.49
  2237.9 1051.02  2296.6 1062.04    2365 1059.16  2423.7  1046.6  2472.6 1043.54
#Mann= 3 , 0 , 0
       0     .08       0     664    .045       0   683.6     .05       0
Bank Sta=664,683.6
XS Rating Curve= 0 ,0
Exp/Cntr=0.3,0.1

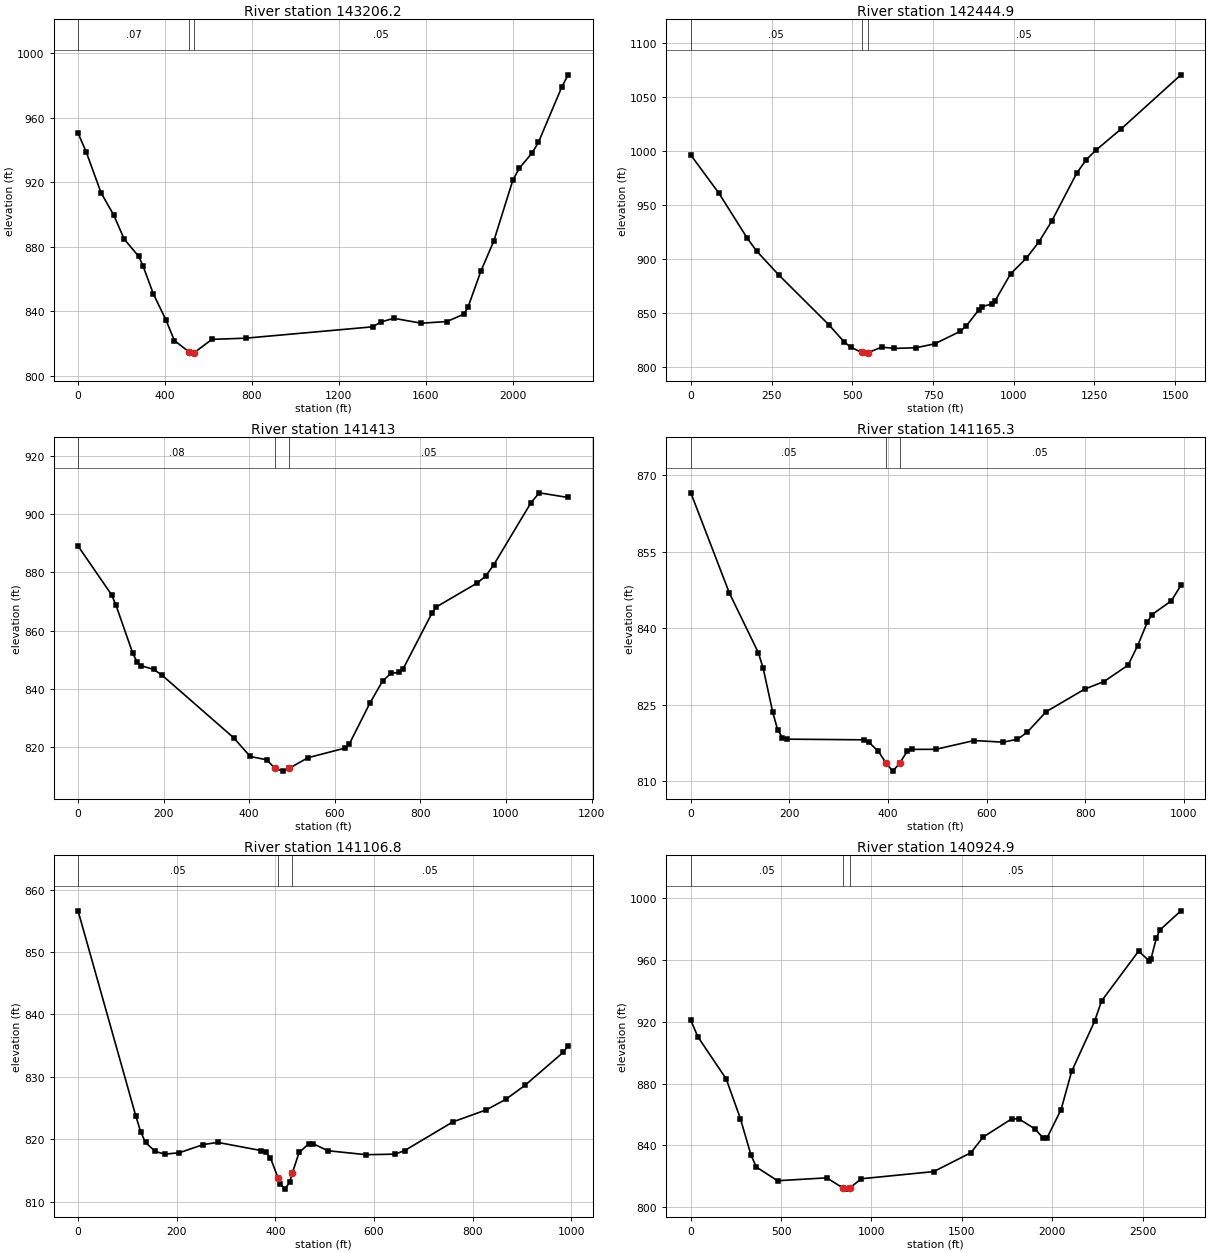
Type RM Length L Ch R = 1 ,143206.2,745,761.3,776.1
XS GIS Cut Line= 5
     1563228.855      304469.331     1563086.494      304879.054
     1562951.077      305208.915      1562659.41      305771.415
     1562114.271      306399.887
#Sta/Elev= 30
       0  950.44    38.6  938.38     106  913.37   163.9  899.72   212.1  884.82
   279.5  873.97   298.8  868.23     347  850.68   404.8  834.62   443.4   821.9
  508.86815.0884   530.1  814.11     535814.4686   616.9  822.65     771  823.36
  1355.7   830.4  1394.7  833.42  1453.3  835.67  1580.6  832.64    1698  833.69
  1776.3  838.27  1795.9  842.93  1854.6  864.99  1913.3  883.39  2001.4  921.23
  2030.8  928.59  2089.5  938.01  2118.9  944.59  2226.5  978.87  2255.9  986.49
#Mann= 3 , 0 , 0
       0     .07       0  508.86    .045       0     535     .05       0
Bank Sta=508.86,535
XS Rating Curve= 0 ,0
Exp/Cntr=0.3,0.1

Type RM Length L Ch R = 1 ,142444.9,1026.9,1031.8,1033.6
XS GIS Cut Line= 4
     1562996.216      304271.415     1562617.744      304469.331
     1562371.216      304601.276      1561659.41      304990.165
#Sta/Elev= 30
       0  996.02    87.4   960.5   174.7  919.03   203.8  907.09   271.8   885.1
   427.1   838.9   475.3  822.76   494.6  818.14   528.8  813.18   542.8  812.51
  547.17812.7698     591  818.06   629.6  816.88   697.1  817.47   755.6  821.16
   833.8  832.61   853.3  837.71   892.4  852.84   902.2  855.64   931.5  857.96
   941.2   860.4   990.1  885.87    1039  900.44  1078.1   915.6  1117.2  934.56
  1195.3  979.35  1224.6  991.72    1254 1000.39  1332.2 1020.11  1517.8 1070.37
#Mann= 3 , 0 , 0
       0     .05       0   528.8    .045       0  547.17     .05       0
Bank Sta=528.8,547.17
XS Rating Curve= 0 ,0
Exp/Cntr=0.3,0.1

Type RM Length L Ch R = 1 ,141413  ,249.7,247.8,245.2
XS GIS Cut Line= 4
     1562541.355      303524.887     1562173.299      303587.387
     1561808.716      303715.859     1561482.327       303920.72
#Sta/Elev= 30
       0  889.03    78.6  872.24    88.4  868.82   127.7  852.32   137.5  849.36
   147.4  847.96   176.8  846.69   196.5  844.69   363.5  823.27   402.3  816.85
     441  815.68   460.3  812.72   479.6  811.81  493.13812.7788   537.6  816.42
   624.6  819.74   634.2  821.21   682.6  835.31   711.6  842.69   730.9  845.32
   750.2   845.7   759.9  846.95   827.3  866.09     837  868.11   933.3  876.37
   952.6  878.71   971.8  882.67  1058.5  903.89  1077.8  907.26  1145.2  905.66
#Mann= 3 , 0 , 0
       0     .08       0   460.3    .045       0  493.13     .05       0
Bank Sta=460.3,493.13
XS Rating Curve= 0 ,0
Exp/Cntr=0.3,0.1

Type RM Length L Ch R = 1 ,141165.3,58.5,58.5,58.5
XS GIS Cut Line= 4
      1562409.41      303307.873     1562098.646      303342.595
     1561914.619      303429.401     1561522.258       303701.97
#Sta/Elev= 30
       0  866.57    78.2  846.91   136.8  835.24   146.6  832.23   166.1  823.55
   175.9  820.15   185.7  818.56   195.4  818.26   351.4  818.13   361.1  817.65
   380.5  815.85  395.98 813.557   409.6  811.99   423.2813.5036   438.7  815.85
   448.4  816.25   496.8  816.27   574.7  817.99   633.2  817.67   662.4  818.24
   681.9   819.6   720.9  823.66   798.9  828.08   837.9  829.56   886.7  832.77
   906.2   836.6   925.7  841.19   935.4   842.7   974.4  845.38   993.9  848.42
#Mann= 3 , 0 , 0
       0     .05       0  395.98    .045       0   423.2     .05       0
Bank Sta=395.98,423.2
XS Rating Curve= 0 ,0
Exp/Cntr=0.3,0.1

Type RM Length L Ch R = 1 ,141106.8,181.3,181.9,182.4
XS GIS Cut Line= 4
     1562392.049      303251.449     1562081.285      303286.172
     1561897.258      303372.977     1561504.896      303645.547
#Sta/Elev= 30
       0  856.61   117.3  823.67     127  821.19   136.8  819.47   156.4  818.04
   175.9   817.6   205.2  817.82   254.1  819.14   283.4  819.48   370.8  818.18
   380.5  817.91   390.2  817.01  405.28813.8398   409.6  812.86   419.3  811.99
     429  813.06  434.35814.5326   448.4  817.89   467.7  819.23   477.4  819.25
   506.5  818.15   584.4  817.51   642.9   817.6   662.4  818.17   759.9  822.76
   828.2  824.71   867.2  826.37   906.2  828.62   984.2  833.94   993.9  834.98
#Mann= 3 , 0 , 0
       0     .05       0  405.28    .045       0  434.35     .05       0
Bank Sta=405.28,434.35
XS Rating Curve= 0 ,0
Exp/Cntr=0.3,0.1

Type RM Length L Ch R = 1 ,140924.9,434.2,454.5,473.2
XS GIS Cut Line= 6
     1562747.952      303180.269      1562056.98      303103.446
     1561777.032      303227.144      1561440.66       303635.13
     1561201.907        303790.8     1560360.799       304103.88
#Sta/Elev= 30
       0  921.04    39.2   910.3   195.8  883.06   274.2  857.41   332.9  833.81
   362.3  826.03   479.8  817.14   752.6  819.01  843.59812.3098   857.8   811.7
  879.94812.4794   943.9  818.42    1344  823.05  1549.7  835.23  1618.5  845.46
  1775.8   857.2  1815.1  857.23  1902.9  850.83  1951.6  844.64  1971.2  844.81
  2049.2  863.16  2107.7  887.91  2234.6  920.36  2273.6  933.59  2478.4  965.86
    2537  959.55  2546.7  960.64    2576  974.03  2595.5  979.47  2712.6  991.95
#Mann= 3 , 0 , 0
       0     .05       0  843.59    .045       0  879.94     .05       0
Bank Sta=843.59,879.94
XS Rating Curve= 0 ,0
Exp/Cntr=0.3,0.1

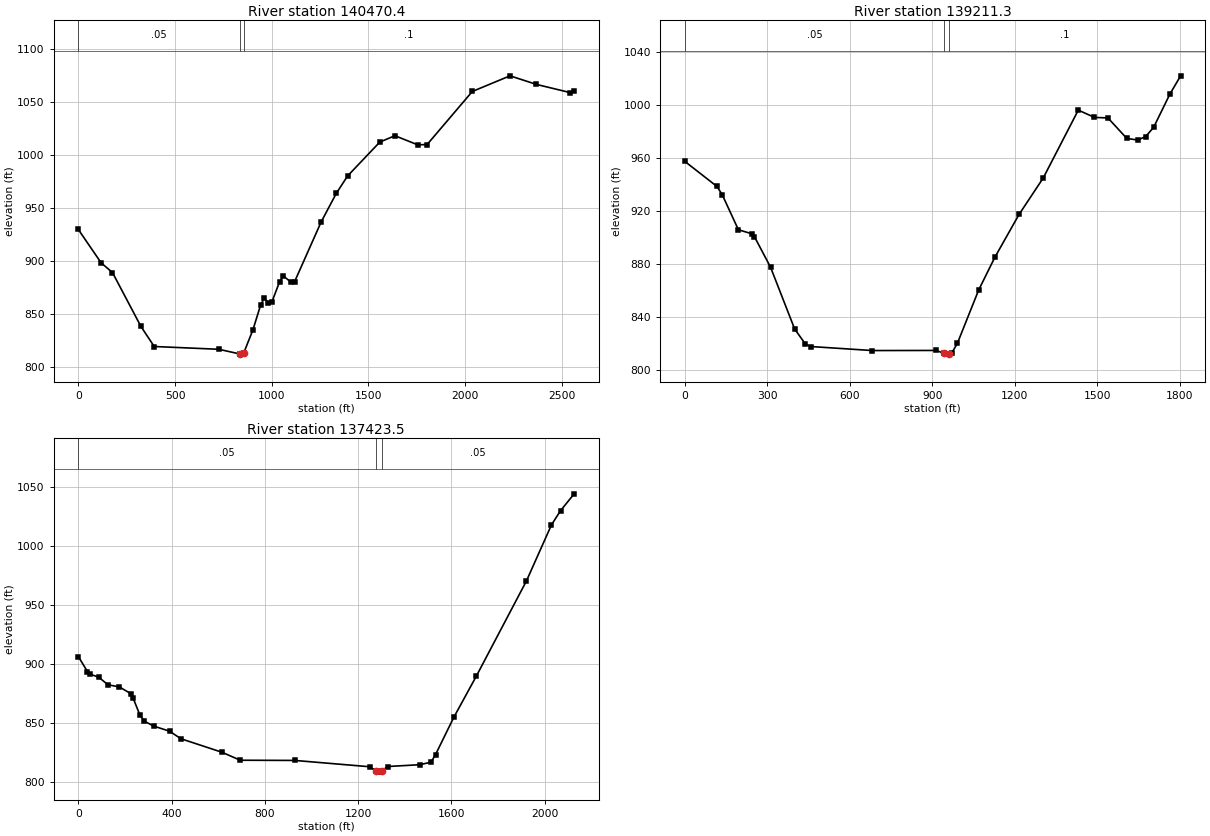
Type RM Length L Ch R = 1 ,140470.4,1254.4,1259.1,1262.5
XS GIS Cut Line= 5
     1562820.869       303135.13     1562301.771      302902.491
     1561951.077      302725.408      1561159.41      302753.186
     1560360.799      302621.241
#Sta/Elev= 30
       0  929.39   117.7  897.97   176.5  888.76   323.6  837.92   392.3  819.01
     726  816.39     834  812.02   843.8  811.82  854.27812.5458   902.8  834.78
   942.1  857.99   961.7  864.83   981.3  860.49  1000.8  861.15    1040  879.85
  1059.5  885.64  1098.6  879.76  1118.2  880.21  1255.1  936.42  1333.3  963.35
    1392  979.86  1558.3 1011.77  1636.5 1017.82  1753.9 1009.28  1802.6  1009.4
  2036.7 1059.54  2231.7  1074.3  2368.3 1066.21  2543.8 1058.43  2563.3 1059.57
#Mann= 3 , 0 , 0
       0     .05       0     834    .045       0  854.27      .1       0
Bank Sta=834,854.27
XS Rating Curve= 0 ,0
Exp/Cntr=0.3,0.1

Type RM Length L Ch R = 1 ,139211.3,1780.9,1787.8,1785.3
XS GIS Cut Line= 4
      1563775.73      302569.158     1563185.452      302121.241
     1562942.396       301947.63      1562181.98      301871.241
#Sta/Elev= 30
       0  957.14     117  938.21   136.5  931.85     195  905.52   243.7   902.5
   253.5  900.22     312  877.23   399.7  830.59   438.7  819.27   458.2  817.38
   682.5  814.34   914.4  814.42   943.3  812.24     953  811.64   962.6   811.8
   972.2  812.85   991.5   819.7  1069.1  860.01  1127.9  884.68    1216  917.06
  1304.2  944.67  1431.6  995.84  1490.4  990.33  1539.4  989.94    1608  974.49
  1647.2  973.27  1676.6  975.82  1705.9  982.91  1764.7 1007.86  1803.9 1021.72
#Mann= 3 , 0 , 0
       0     .05       0   943.3    .045       0   962.6      .1       0
Bank Sta=943.3,962.6
XS Rating Curve= 0 ,0
Exp/Cntr=0.3,0.1

Type RM Length L Ch R = 1 ,137423.5,1519.3,1506.8,1493.3
XS GIS Cut Line= 5
     1564473.646      302149.019     1563845.174       301635.13
     1563532.674      301388.602     1563296.563      301214.991
     1562706.285      301013.602
#Sta/Elev= 30
       0  906.58    39.1  893.87    48.9  891.89      88  888.93   127.2  882.69
   176.1  880.82     225  875.17   234.7  871.52   264.1  857.01   283.6  851.78
   322.8  847.71   391.2  843.32   440.2  836.93   616.2  825.49   694.4  818.74
   928.3  818.57  1248.9  813.23 1275.12809.9855    1288  808.66  1301.3809.7421
  1327.1  813.42  1463.8  814.94  1512.7  817.08  1532.2  823.58  1610.1  854.97
  1707.6  890.19    1922  970.66  2029.2  1018.1  2068.1 1030.13  2126.6 1044.43
#Mann= 3 , 0 , 0
       0     .05       0 1275.12    .045       0  1301.3     .05       0
Bank Sta=1275.12,1301.3
XS Rating Curve= 0 ,0
Exp/Cntr=0.3,0.1