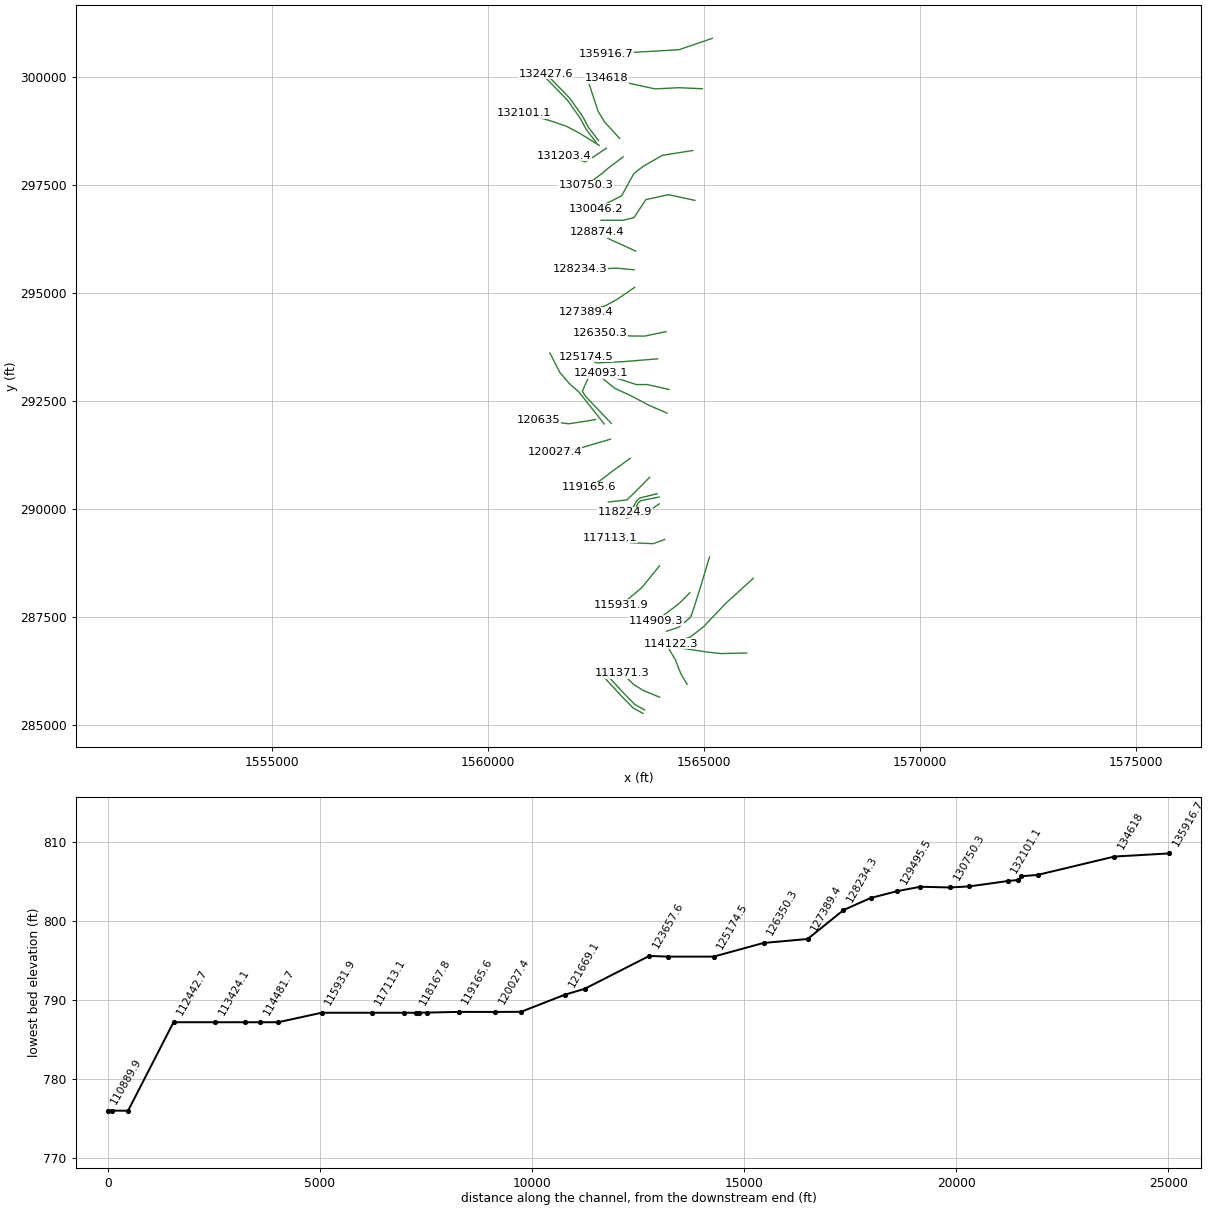
HEC-RAS study NFHGHSRV1.prj: NFHGHSRV1

--- NFHGHSRV1.g01 (geometry) --- (continued)

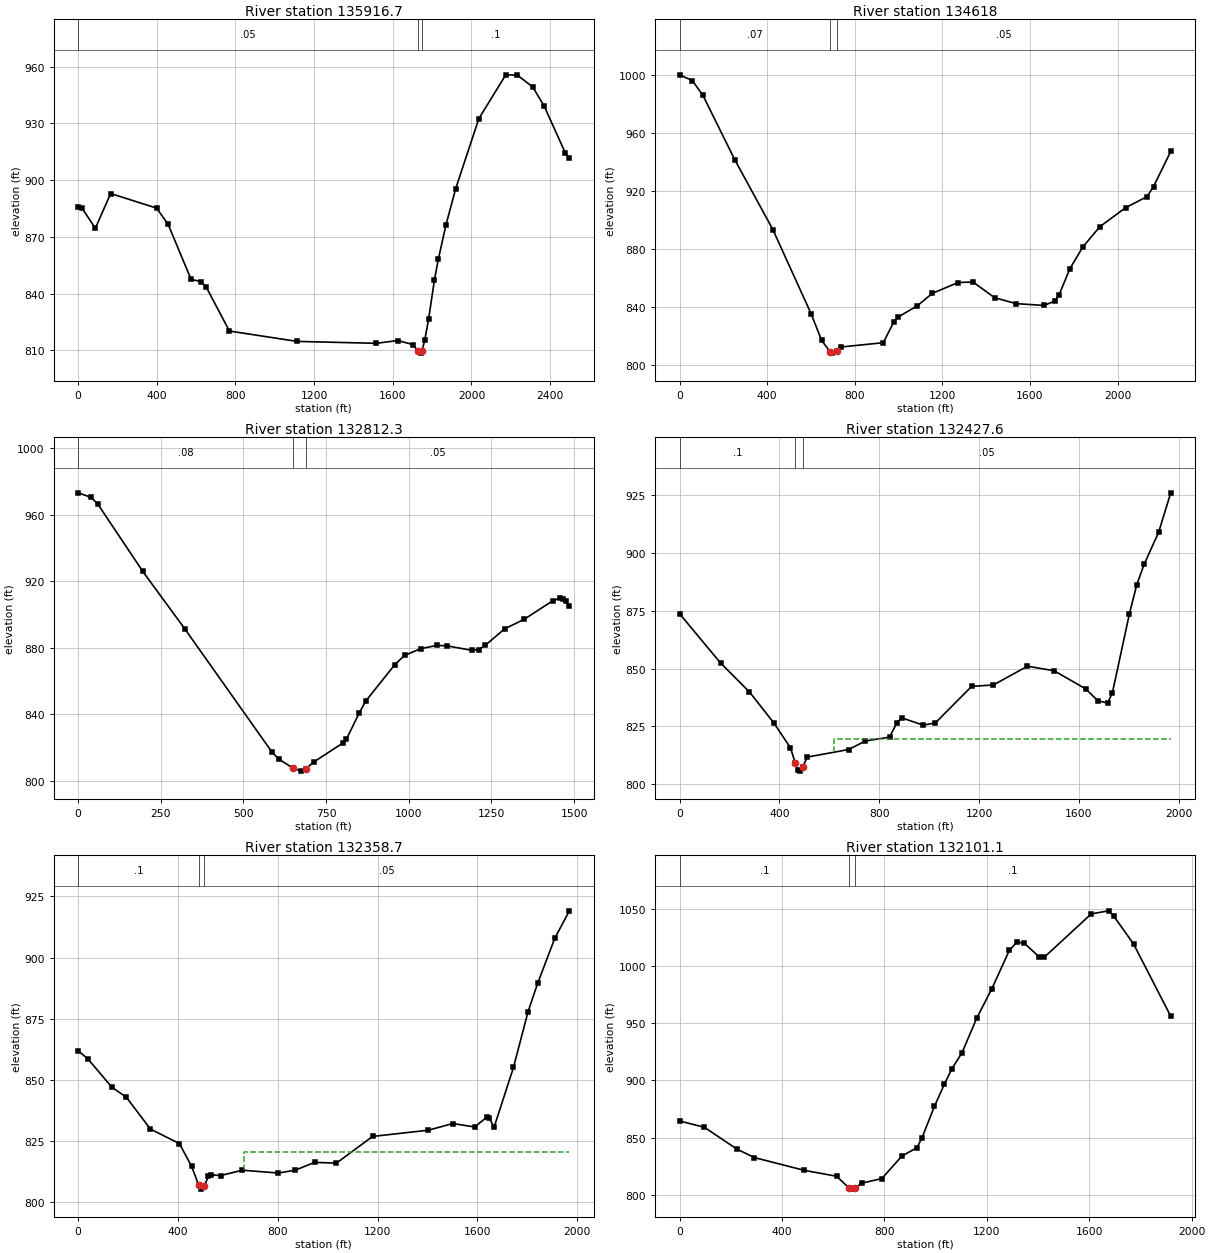
Type RM Length L Ch R = 1 ,135916.7,1297.5,1298.7,1297
XS GIS Cut Line= 4
      1565195.93      300888.066     1564421.563      300624.713
     1563331.347      300561.677     1562744.541      300530.427
#Sta/Elev= 30
       0  885.62    19.5  885.26    87.6  874.52   165.5  892.92   399.2  885.22
   457.6  876.64   574.5  847.54   623.2  846.42   652.4  843.29   769.2  820.24
  1113.1  814.76  1516.4  813.74  1624.6  815.22  1703.4  813.06  1726.3809.8143
  1742.7  808.56 1747.44 809.508  1762.4   815.3  1782.1  826.57  1811.6  847.15
  1831.3  858.07  1870.6  876.48  1919.8   895.5  2037.3  932.48  2174.4  955.67
  2233.2  955.51  2311.5  949.27  2370.3  939.01    2478  914.19  2497.6  911.56
#Mann= 3 , 0 , 0
       0     .05       0  1726.3    .045       0 1747.44      .1       0
Bank Sta=1726.3,1747.44
XS Rating Curve= 0 ,0
Exp/Cntr=0.3,0.1

Type RM Length L Ch R = 1 ,134618  ,1829.2,1805.7,1781.1
XS GIS Cut Line= 4
      1564963.23      299721.936     1564421.563      299746.241
      1563869.48      299718.463     1562747.952      299961.519
#Sta/Elev= 30
       0 1000.03    58.1   996.1   106.5  985.98   251.7  941.65     426  893.38
   600.4  835.44   648.9  816.87   687.7  809.05   697.4  808.16   716.8  809.86
   736.2  812.36   930.1  815.35   978.6  829.69     998  833.07  1085.3  840.73
  1153.8  849.33  1271.5  856.84  1340.2  857.19  1438.3  846.38  1536.4  842.29
  1663.9  841.04  1712.9     844  1732.5  848.16  1781.6  866.21  1840.4   881.2
  1918.9  895.31  2036.6  908.42  2134.7   916.1  2164.1  922.99  2242.6  947.26
#Mann= 3 , 0 , 0
       0     .07       0   687.7    .045       0   716.8     .05       0
Bank Sta=687.7,716.8
XS Rating Curve= 0 ,0
Exp/Cntr=0.3,0.1

Type RM Length L Ch R = 1 ,132812.3,386.6,384.7,383.2
XS GIS Cut Line= 4
     1563050.035       298572.63     1562706.285       298947.63
     1562553.508       299197.63      1562338.23      299846.936
#Sta/Elev= 30
       0  973.23    39.1  970.54    58.7  966.71   195.7  925.92   322.8  891.39
   586.8  817.18   606.4  813.16  650.02807.6478   674.7  805.84  688.17807.2342
   713.8  811.46   801.7  822.85   811.5  825.04   850.6  840.91   870.1     848
   958.1  869.95   987.4  875.45  1036.2  879.49  1085.1  881.44  1114.4  881.22
  1192.6  878.46  1212.1  878.98  1231.7  881.54  1290.3  891.46    1349  897.12
  1436.9  908.46  1456.4  909.84  1466.2  909.67    1476  907.93  1485.8  904.96
#Mann= 3 , 0 , 0
       0     .08       0  650.02    .045       0  688.17     .05       0
Bank Sta=650.02,688.17
XS Rating Curve= 0 ,0
Exp/Cntr=0.3,0.1

Type RM Length L Ch R = 1 ,132427.6,68.9,68.9,68.9
XS GIS Cut Line= 5
     1562559.584      298525.755     1562325.209      298833.047
     1562199.547      299073.395     1561898.766      299500.045
     1561350.155      300066.017
#Sta/Elev= 30
       0  873.72   164.2  852.42   280.2  839.89   376.8  826.64   444.6  815.74
     464  809.03   473.6  806.12   483.3  805.67     493  807.54   512.4  811.76
     677  814.99   744.7   818.7   841.4  820.36   870.4  826.49   889.7  828.71
   976.7  825.53    1025  826.51    1170  842.27  1257.6  842.91  1393.8  851.01
  1500.8  849.04  1627.3   841.2    1676  836.07  1714.9   835.1  1734.4  839.62
  1802.5  873.76  1831.7  886.16  1860.9  894.96  1919.3  908.86  1967.9  925.93
#Mann= 3 , 0 , 0
       0      .1       0     464    .045       0     493     .05       0
#XS Ineff= 2 , 0
                          618.73          819.74
Permanent Ineff=
       F       F
Bank Sta=464,493
XS Rating Curve= 0 ,0
Exp/Cntr=0.3,0.1

Type RM Length L Ch R = 1 ,132358.7,241.7,257.5,273.5
XS GIS Cut Line= 5
     1562507.501      298478.012     1562273.126      298785.304
     1562147.464      299025.652     1561846.682      299452.302
     1561298.071      300018.274
#Sta/Elev= 30
       0  861.86    38.6  858.59   135.3   846.9   193.2  842.82   289.8  829.78
   405.8  823.85   454.3   814.6   483.3  806.81     493   805.2  505.42806.4087
   522.1  810.52   531.8  811.06   570.5  810.75   657.7  812.95   802.7  811.78
   870.4  812.98   947.7  816.16  1034.7  815.83  1179.7  826.77  1403.5  829.32
  1500.8  832.06  1588.4  830.64  1637.1  834.61  1646.8  834.42  1666.3   830.5
  1744.1     855  1802.5  877.84  1841.4  889.56  1909.5  907.85  1967.9  919.12
#Mann= 3 , 0 , 0
       0      .1       0   483.3    .045       0  505.42     .05       0
#XS Ineff= 2 , 0
                          665.55           820.3
Permanent Ineff=
       F       F
Bank Sta=483.3,505.42
XS Rating Curve= 0 ,0
Exp/Cntr=0.3,0.1

Type RM Length L Ch R = 1 ,132101.1,876.4,897.8,918.4
XS GIS Cut Line= 5
     1562580.417      298410.304     1562117.082      298696.659
     1561821.943      298852.909     1561453.019      298978.777
     1560829.321      299160.635
#Sta/Elev= 30
       0  864.59    97.3  859.03   223.7  840.08   291.8  832.64   486.3   821.5
   613.4   816.3   662.6  805.93   672.4  805.06   683.5  805.63   711.7  810.24
   790.2  814.32   868.8  834.03   927.4  841.27   946.8   849.9   995.6  877.43
  1034.6  896.94  1063.8  910.24  1102.8  924.03  1161.2  954.68  1219.7  980.09
  1287.8 1013.52  1316.9 1020.68    1346 1019.86  1404.2 1007.87  1423.6 1007.42
  1607.8  1045.4  1675.7 1048.06  1695.1 1043.62  1772.7  1019.2  1918.1  956.02
#Mann= 3 , 0 , 0
       0      .1       0   662.6    .045       0   683.5      .1       0
Bank Sta=662.6,683.5
XS Rating Curve= 0 ,0
Exp/Cntr=0.3,0.1

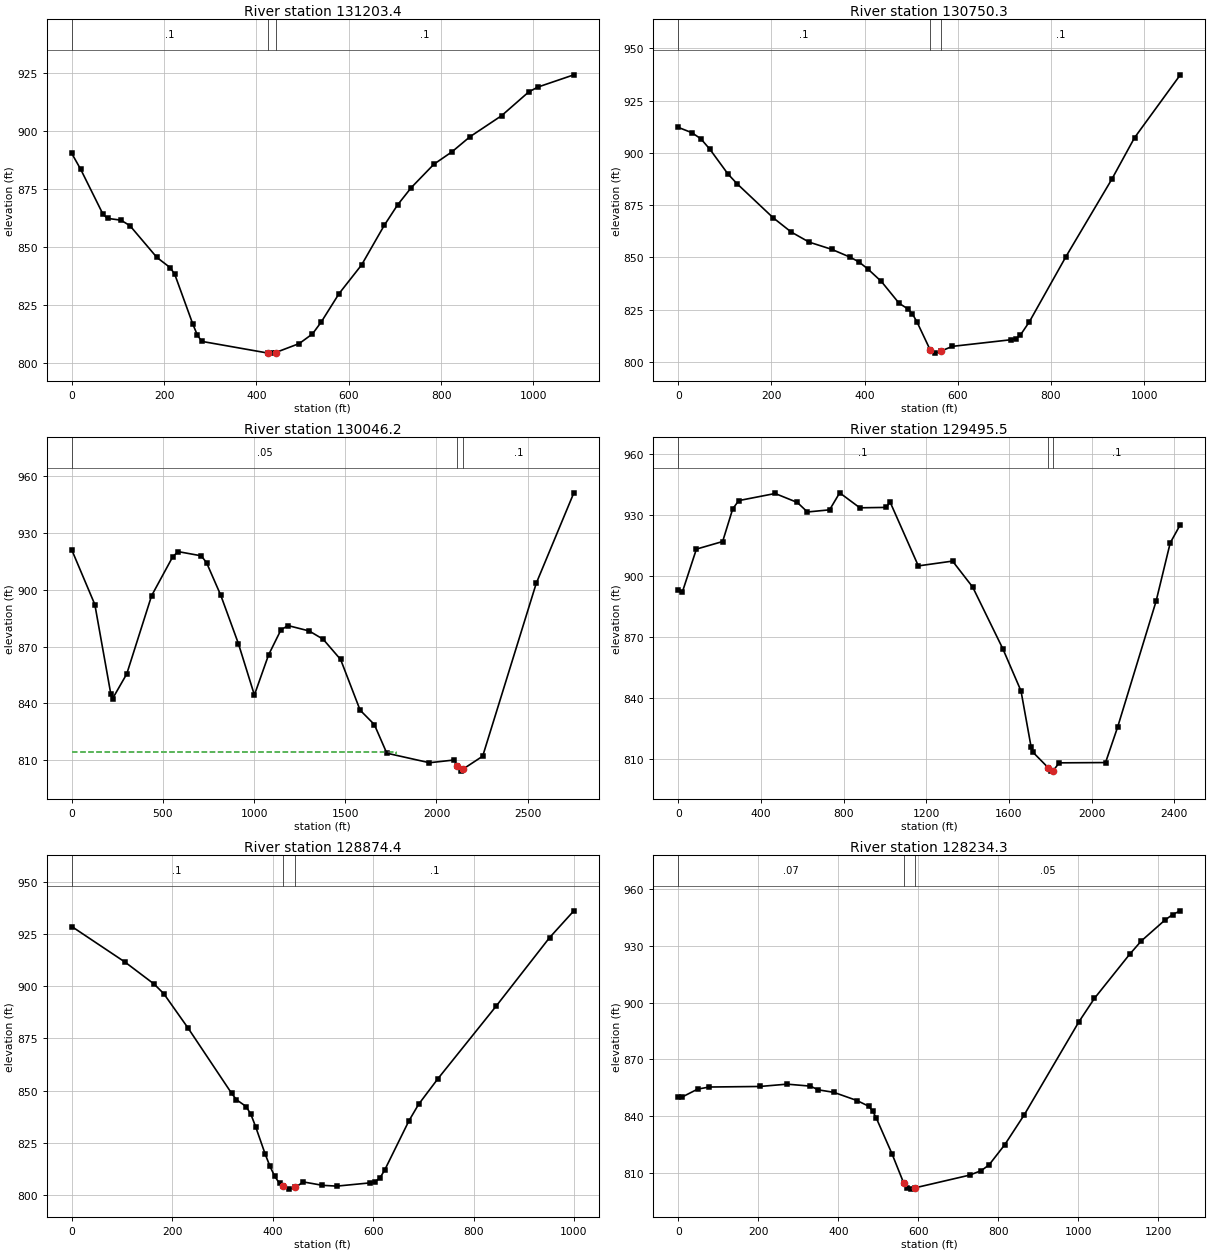
Type RM Length L Ch R = 1 ,131203.4,449.1,453.1,456.7
XS GIS Cut Line= 4
     1562741.876      298346.068     1562460.626      298155.963
     1562254.896      298033.568     1561765.313      298171.588
#Sta/Elev= 30
       0   890.4    19.4  883.54    67.9  864.11    77.6  862.43   106.7  861.66
   126.1  859.26   184.3  845.62   213.4  841.18   223.1  838.32   261.9  817.04
   271.6  812.36   281.3  809.46  424.24804.4387   435.2  804.39   441.3  804.63
   492.7  808.51   521.4  812.67   540.6  817.87   578.9  830.02   627.8   842.4
   676.7  859.38     706  868.32   735.4   875.7   784.3  885.75   823.4  891.09
   862.5   897.6     931  906.67   989.7  916.89  1009.3  918.98  1087.5  924.27
#Mann= 3 , 0 , 0
       0      .1       0  424.24    .045       0   441.3      .1       0
Bank Sta=424.24,441.3
XS Rating Curve= 0 ,0
Exp/Cntr=0.3,0.1

Type RM Length L Ch R = 1 ,130750.3,703.9,704.2,704.2
XS GIS Cut Line= 4
     1563131.633      298146.415     1562791.355       297889.47
     1562631.633      297754.054     1562277.466      297490.165
#Sta/Elev= 30
       0  912.25    29.1  909.71    48.4  906.81    67.8  901.81   106.6  889.97
     126  885.33   203.5  869.04   242.3   862.2     281  857.34   329.5  853.89
   368.2  850.22   387.6  847.91     407  844.49   435.9  838.54     474   828.1
     493  825.37   502.5  823.02   512.1  819.31   540.6  805.84   550.1  804.25
   564.2805.2579   588.2  807.48   714.3  810.66   724.1  811.22   733.9  812.76
   753.6  819.26   832.1  850.43   930.2  887.33   979.3  907.31  1077.5  937.38
#Mann= 3 , 0 , 0
       0      .1       0   540.6    .045       0   564.2      .1       0
Bank Sta=540.6,564.2
XS Rating Curve= 0 ,0
Exp/Cntr=0.3,0.1

Type RM Length L Ch R = 1 ,130046.2,560.6,550.7,540
XS GIS Cut Line= 6
     1564735.799      298292.248      1564034.41      298181.137
     1563580.827      297917.513     1563377.292      297757.526
     1563096.042      297244.505     1562502.292      296945.026
#Sta/Elev= 30
       0  920.94   126.5  892.15     214  845.06   223.7  842.52   301.6  855.59
   437.8   896.8   554.5  917.45   583.7  920.03   710.1  917.82   739.3  914.18
     817  897.06   914.2  871.46  1001.6  844.46  1079.3  865.59  1147.3  878.81
  1186.2  881.05  1301.9  878.22  1378.6  873.86  1474.5  863.18  1581.4  836.48
  1659.4  828.89  1727.7   813.8  1961.7  808.76  2098.1  810.22 2113.21 807.301
    2137  804.34  2146.7  805.47  2253.6  812.21  2547.5  903.35  2753.6  951.02
#Mann= 3 , 0 , 0
       0     .05       0 2113.21    .045       0  2146.7      .1       0
#XS Ineff= 2 , 0
         1777.56  814.63
Permanent Ineff=
       F       F
Bank Sta=2113.21,2146.7
XS Rating Curve= 0 ,0
Exp/Cntr=0.3,0.1

Type RM Length L Ch R = 1 ,129495.5,635.9,621,605.7
XS GIS Cut Line= 6
     1564791.355       297139.47     1564180.244      297271.415
     1563655.938      297156.831     1563382.501      296741.901
     1563137.709      296679.401      1562619.48      296679.401
#Sta/Elev= 30
       0  892.88    19.5  891.88    87.9  913.16   214.9   916.9   263.8  933.03
   293.1  937.07   468.9  940.56   576.4  936.14   625.2  931.45   732.5  932.51
   781.3  940.89   878.9  933.51  1005.8  933.71  1025.3  936.34  1161.9  904.89
  1327.5  907.26    1425  894.44  1571.1     864  1658.8  843.27  1707.4   815.8
  1717.1  813.04 1789.86805.5092  1804.6  803.78 1815.28804.0864  1843.4  807.86
  2067.9     808  2126.6  825.55  2312.3  887.43  2380.8   916.2  2429.7  925.22
#Mann= 3 , 0 , 0
       0      .1       0 1789.86    .045       0 1815.28      .1       0
Bank Sta=1789.86,1815.28
XS Rating Curve= 0 ,0
Exp/Cntr=0.3,0.1

Type RM Length L Ch R = 1 ,128874.4,629.2,640.1,650.6
XS GIS Cut Line= 4
     1563421.563      295965.859     1563106.459      296111.693
     1562872.084      296215.859     1562520.521      296398.151
#Sta/Elev= 30
       0  928.56   106.1  911.53     164  901.02   183.2  896.43   231.5     880
   318.3  848.75   327.9  845.71   347.2  842.43   356.7  838.69   366.2   832.7
   385.2  819.63   394.7   813.8   404.2  809.01   413.7  805.66  419.81804.3865
   432.7  802.92  445.11803.7756   461.2  806.36   499.2  804.74   527.7  804.36
   594.2  805.92   603.7  806.47   613.4  808.18     623  812.02   671.3  835.59
   690.6   843.5   729.3  855.83   845.2  890.54   951.4  923.26   999.7  936.07
#Mann= 3 , 0 , 0
       0      .1       0  419.81    .045       0  445.11      .1       0
Bank Sta=419.81,445.11
XS Rating Curve= 0 ,0
Exp/Cntr=0.3,0.1

Type RM Length L Ch R = 1 ,128234.3,834.5,844.9,854.6
XS GIS Cut Line= 4
     1563382.501      295533.568     1562976.251       295572.63
     1562666.355      295554.401     1562129.896      295557.005
#Sta/Elev= 30
       0  850.06     9.7  850.14    48.6  854.33    77.7  855.43   204.1  855.72
   272.1  856.95   330.4   855.9   349.8  853.94   388.7  852.63   446.9  848.27
     476  845.28   485.7  842.82   495.4  838.85   534.2  820.15   563.3  804.76
     573  801.78   582.7  801.39   592.4   802.1   728.3   808.8   757.6   811.2
   777.1  814.26   816.1  824.87   864.9  840.72  1001.4  889.91  1040.4  902.37
  1128.2  925.64  1157.5  932.74    1216  943.68  1235.5  946.68    1255  948.68
#Mann= 3 , 0 , 0
       0     .07       0   563.3    .045       0   592.4     .05       0
Bank Sta=563.3,592.4
XS Rating Curve= 0 ,0
Exp/Cntr=0.3,0.1

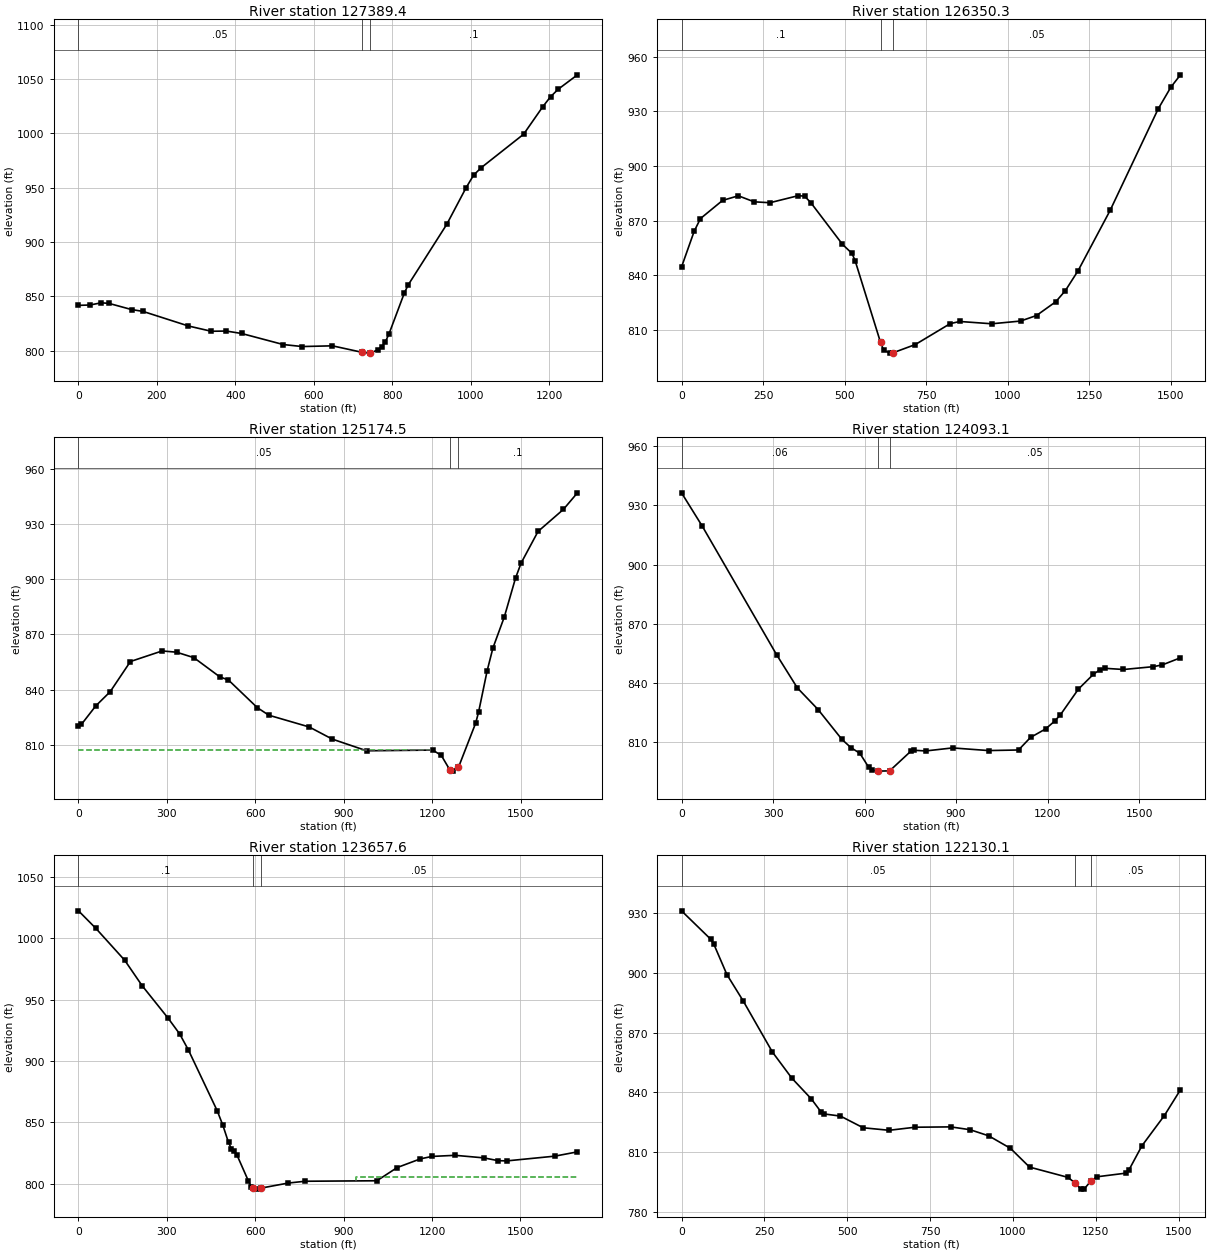
Type RM Length L Ch R = 1 ,127389.4,1050.4,1039.1,1027.1
XS GIS Cut Line= 4
      1563400.73      295129.922     1563002.292      294856.484
     1562723.646      294702.838     1562278.334      294551.797
#Sta/Elev= 30
       0  841.69      29  842.02      58  844.03    77.3  843.54   135.3  837.83
   164.3  836.14   280.3   822.7   338.3  817.86   376.9  818.04   415.6  815.82
   521.8  805.64     570  803.79   647.2  804.45   722.2  798.53   743.6  797.73
   762.9  800.78   772.5  803.47   782.2  808.11   791.8  815.78   830.8  853.35
   840.6  860.66   938.6  916.25   987.6  949.77  1007.2  961.62  1026.8  968.51
  1134.5   999.2  1183.5 1024.59  1203.1 1033.67  1222.7 1040.62  1271.7 1053.87
#Mann= 3 , 0 , 0
       0     .05       0   722.2    .045       0   743.6      .1       0
Bank Sta=722.2,743.6
XS Rating Curve= 0 ,0
Exp/Cntr=0.3,0.1

Type RM Length L Ch R = 1 ,126350.3,1173.8,1175.8,1176.8
XS GIS Cut Line= 4
     1564122.084       294103.88     1563629.896      293999.713
     1563309.584      294002.318     1562606.459      294064.818
#Sta/Elev= 30
       0  844.49    38.7  864.06      58  871.08   125.8  881.05   174.2  883.58
   222.5  880.28   270.9  879.78     358  883.66   377.3  883.39   396.7  879.72
   493.4  856.92   522.5  851.96   532.2  847.92   609.9  803.18   619.6  798.84
     639  797.23   648.7  797.45   716.6  801.94   823.4  813.41   852.8   814.6
   950.9  813.34  1039.1  814.83  1088.1  817.88    1147  825.42  1176.4   831.5
  1215.6   842.5  1313.6  875.53  1460.7  931.18  1499.9  943.22  1529.3  949.98
#Mann= 3 , 0 , 0
       0      .1       0   609.9    .045       0   648.7     .05       0
Bank Sta=609.9,648.7
XS Rating Curve= 0 ,0
Exp/Cntr=0.3,0.1

Type RM Length L Ch R = 1 ,125174.5,1081.9,1081.4,1079.2
XS GIS Cut Line= 4
     1563929.376      293473.672     1563129.896      293408.568
     1562507.501      293379.922     1562283.542      293525.755
#Sta/Elev= 30
       0  820.07     9.8  820.96    58.7  831.08   107.6  838.82   176.1  855.26
   283.7  861.03   332.6  860.35   391.3  857.37   479.3   846.9   508.7  845.17
   606.5  830.12   645.6  825.99   782.6  819.58   860.5  812.98   977.4  806.59
  1201.3  806.98  1230.5   804.1  1259.7  796.14  1269.4   795.5  1288.9  797.58
  1347.3  821.73    1357  827.61  1386.2  850.26  1405.7  862.63  1444.3  879.53
  1482.4  900.76  1501.5     909  1558.8   926.2  1644.7  938.19  1692.4  947.24
#Mann= 3 , 0 , 0
       0     .05       0  1259.7    .045       0  1288.9      .1       0
#XS Ineff= 2 , 0
         1195.75  807.21
Permanent Ineff=
       F       F
Bank Sta=1259.7,1288.9
XS Rating Curve= 0 ,0
Exp/Cntr=0.3,0.1

Type RM Length L Ch R = 1 ,124093.1,446.3,435.5,425.6
XS GIS Cut Line= 4
     1564192.849      292765.323     1563679.828      292879.906
     1563435.037      292878.604      1562612.12      293145.531
#Sta/Elev= 30
       0  936.39    68.1  919.49   311.5  854.49   379.6  837.65   447.8  826.66
   525.7  811.58     555  807.45   584.4  804.54   613.8  797.42   623.6     796
   643.2   795.5   682.3  795.64   750.9  805.47   760.7  806.08     800  805.71
   888.4  807.25  1006.4  805.91  1104.7   806.2    1144  812.55  1193.2  816.84
  1222.7  820.74  1242.3  824.07  1301.3  837.07  1350.5  844.57  1370.2  846.67
  1389.8  847.54  1448.8  846.95  1547.1  848.39  1576.6  849.31  1635.6  852.88
#Mann= 3 , 0 , 0
       0     .06       0   643.2    .045       0   682.3     .05       0
Bank Sta=643.2,682.3
XS Rating Curve= 0 ,0
Exp/Cntr=0.3,0.1

Type RM Length L Ch R = 1 ,123657.6,1561.3,1527.5,1492.8
XS GIS Cut Line= 5
     1564145.521      292218.463     1563731.459      292398.151
     1563348.646      292601.276     1562929.376      292796.588
     1562661.146      293015.338
#Sta/Elev= 30
       0 1022.23    58.9 1007.96     157  981.93   215.9  961.29   304.2   934.8
   343.4  921.97   372.9  908.98   470.6  859.52   489.9  847.67   509.2  833.58
   518.8  828.52   528.4  826.51     538  823.28   576.6  802.28   586.2  797.62
  592.17796.5006   605.5  795.59   619.4  796.42   711.4  800.52   769.2  802.01
  1012.7   802.4  1081.6  813.16  1160.3  820.23  1199.6  822.22  1278.4  823.12
  1376.1  821.03  1424.2  818.77    1453  818.57  1616.5  822.44  1693.4  825.94
#Mann= 3 , 0 , 0
       0      .1       0  592.17    .045       0   619.4     .05       0
#XS Ineff= 2 , 0
                          942.02          805.75
Permanent Ineff=
       F       F
Bank Sta=592.17,619.4
XS Rating Curve= 0 ,0
Exp/Cntr=0.3,0.1

Type RM Length L Ch R = 1 ,122130.1,435.5,461,485.8
XS GIS Cut Line= 4
     1562856.459      291981.484     1562262.915      292605.514
     1562187.188      292723.672     1562390.313      293184.609
#Sta/Elev= 30
       0  931.15    88.1  916.89    97.9  914.25     137  899.12     186  885.93
     274   860.3   332.8  847.14   391.5  836.74   420.8  830.21   430.6  829.16
   479.6  828.09     548  822.23   626.3  820.96   704.6   822.5   812.3  822.67
   870.6  821.25   926.7  818.19   992.2  811.92    1050  802.48  1166.2  797.31
  1185.6  794.74    1205  791.44  1214.7  791.42    1234  795.33  1253.4  797.62
  1340.6  799.44  1350.3  801.19    1389  813.17  1456.8  828.38  1505.3  841.31
#Mann= 3 , 0 , 0
       0     .05       0  1185.6    .045       0    1234     .05       0
Bank Sta=1185.6,1234
XS Rating Curve= 0 ,0
Exp/Cntr=0.3,0.1

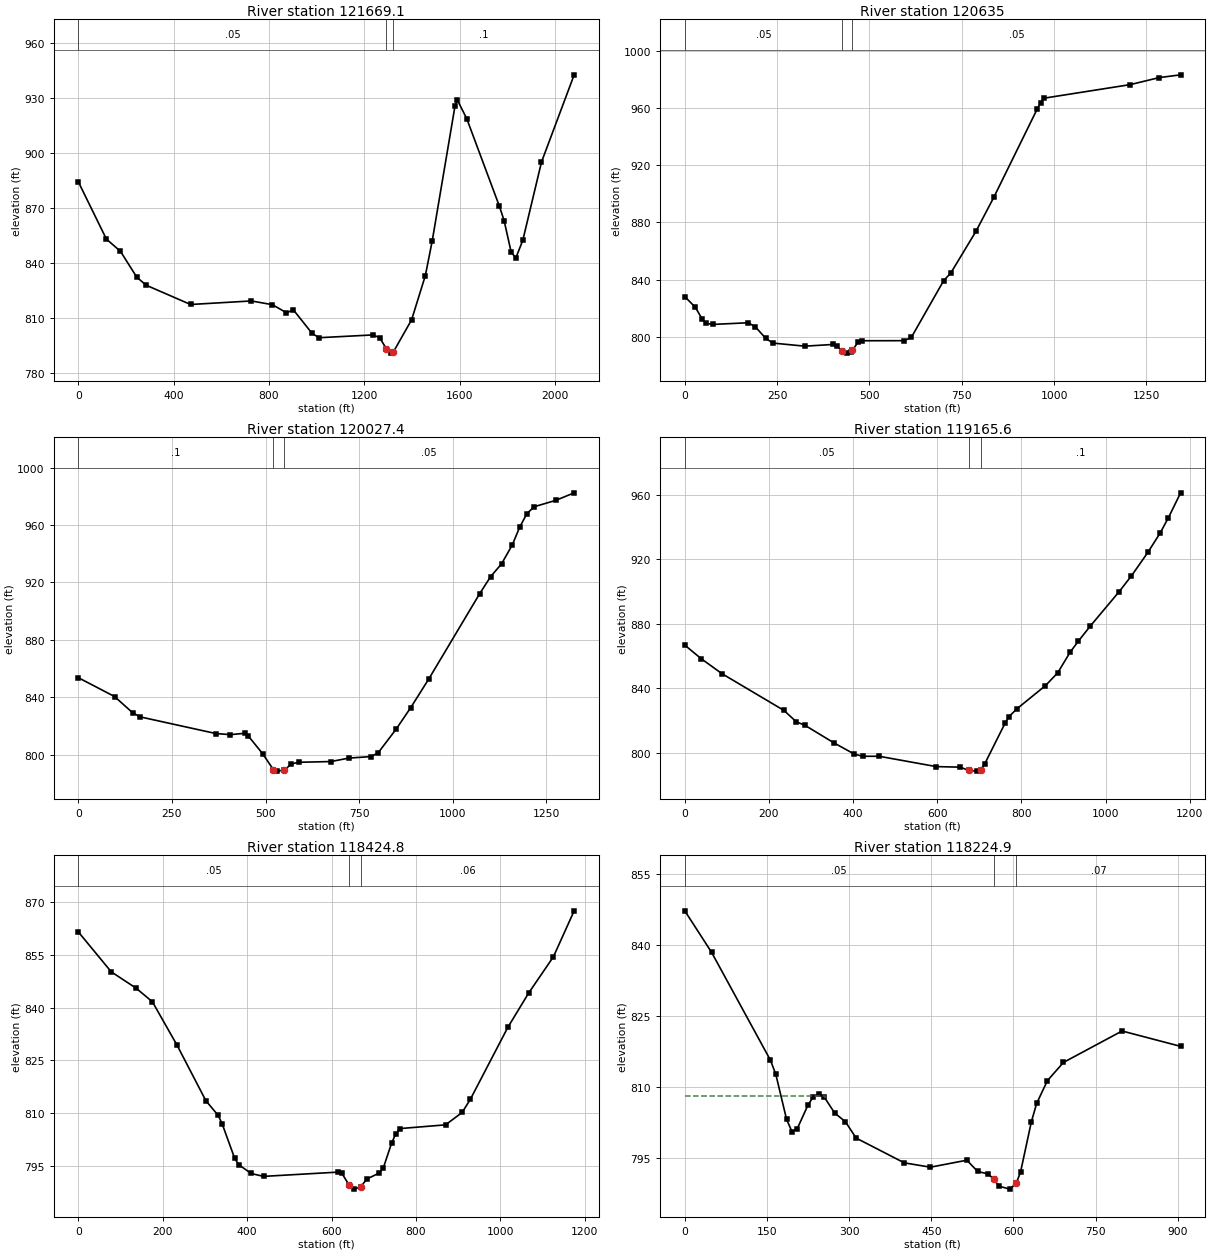
Type RM Length L Ch R = 1 ,121669.1,1011.3,1034.1,1056.4
XS GIS Cut Line= 5
     1562692.396      291968.463     1562107.533      292706.642
     1561887.709      292900.755     1561663.751      293163.776
     1561437.188      293609.088
#Sta/Elev= 30
       0  884.13   117.7   852.9   176.6  846.24   245.3  832.09   284.5  827.74
   470.9  817.22     726  819.15   814.3  817.11   873.1  812.73   902.6  814.23
   980.9  801.42  1010.2   799.1    1235  800.61  1263.8   799.2  1292.6  793.01
  1311.8  790.69  1321.4  791.28  1398.2  808.87  1455.8  832.98  1484.6  851.87
  1580.5  925.71  1590.3  928.68  1629.5  918.57  1766.6  870.77  1786.2  863.01
  1815.6  845.91  1835.2  842.55  1864.6  852.19    1943   894.9  2080.1  942.49
#Mann= 3 , 0 , 0
       0     .05       0  1292.6    .045       0  1321.4      .1       0
Bank Sta=1292.6,1321.4
XS Rating Curve= 0 ,0
Exp/Cntr=0.3,0.1

Type RM Length L Ch R = 1 ,120635  ,604.3,607.6,611.1
XS GIS Cut Line= 4
      1562494.48      292070.026     1562278.334      292033.568
      1561869.48      291971.068     1561166.355      292067.422
#Sta/Elev= 30
       0  828.08    28.6  820.56    47.6  812.16    57.2  809.41    76.2  808.62
   171.6  809.77   190.6  807.03   219.2  798.86   238.4  795.56     325  793.39
     402   794.6   411.6  793.64  425.71789.8221   440.4  788.52     450  788.98
  453.63790.4208   469.3  796.29   478.9  797.19   594.3  797.24   613.6  799.63
   700.9  839.23   720.3  844.62   788.4  873.79     837  897.73   953.6  959.06
   963.4  963.86   973.1  966.97  1206.4  976.46  1284.2  981.35  1342.5   983.3
#Mann= 3 , 0 , 0
       0     .05       0  425.71    .045       0  453.63     .05       0
Bank Sta=425.71,453.63
XS Rating Curve= 0 ,0
Exp/Cntr=0.3,0.1

Type RM Length L Ch R = 1 ,120027.4,852.9,861.8,869.7
XS GIS Cut Line= 4
     1562835.626      291614.297     1562455.417      291502.318
     1562179.376      291421.588     1561546.563      291325.234
#Sta/Elev= 30
       0  853.63    96.7  840.49     145   829.2   164.3  826.36   367.4  814.69
   405.9  813.94   444.3  814.86   453.9     813   492.2  800.65     521  789.49
   530.6   788.5  550.43789.2234   568.9  793.52   588.1  794.67   674.4  795.17
   722.8   797.6     781  798.62   800.3  801.15   848.8   817.8   887.6  832.73
   936.1  852.84  1071.9  912.24    1101  924.06  1130.1  932.94  1159.2  946.33
  1178.6  958.58    1198     968  1217.4  972.78  1275.6  977.28  1324.1  982.48
#Mann= 3 , 0 , 0
       0      .1       0     521    .045       0  550.43     .05       0
Bank Sta=521,550.43
XS Rating Curve= 0 ,0
Exp/Cntr=0.3,0.1

Type RM Length L Ch R = 1 ,119165.6,738.5,740.7,743.3
XS GIS Cut Line= 4
     1563296.563      291174.193     1562882.501      290874.713
     1562624.688      290674.193     1562330.417      290502.318
#Sta/Elev= 30
       0  866.61    39.3  858.16    88.4  848.92   235.8  826.11   265.3  819.02
     285  817.01   353.8  806.13   402.9  799.06   422.6  797.71   461.9  797.72
   597.5  791.32   655.1  790.97   674.3  788.93   693.5  788.51   703.1  789.35
   712.8  793.01   760.8  818.04   770.4  822.27   789.6  827.21   857.1   841.5
   886.3  849.48   915.5  862.11     935  868.99   964.2  878.59  1032.4  899.81
  1061.6   909.6  1100.5  924.12  1129.7   936.1  1149.2  945.54  1178.4  961.05
#Mann= 3 , 0 , 0
       0     .05       0   674.3    .045       0   703.1      .1       0
Bank Sta=674.3,703.1
XS Rating Curve= 0 ,0
Exp/Cntr=0.3,0.1

Type RM Length L Ch R = 1 ,118424.8,192.7,199.9,207.2
XS GIS Cut Line= 4
      1563744.48      290734.088     1563395.521      290379.922
     1563218.438      290210.651     1562788.751      290161.172
#Sta/Elev= 30
       0  861.49      78  850.15   136.5  845.54   175.5  841.64     234  829.28
   302.2  813.53   331.5  809.34   341.2  806.82   370.5  797.13   380.2  795.35
   409.5  792.86   438.7  792.04   614.8  793.25   624.6  792.86  641.15789.6572
     654  788.42  668.59789.0023   683.4  791.28   712.8  792.99   722.6  794.46
   742.2  801.49     752   804.1   761.8  805.62     870  806.68   909.3   810.2
   928.9  813.97  1017.4  834.34  1066.6  844.07  1125.6  854.44  1174.7  867.48
#Mann= 3 , 0 , 0
       0     .05       0  641.15    .045       0  668.59     .06       0
Bank Sta=641.15,668.59
XS Rating Curve= 0 ,0
Exp/Cntr=0.3,0.1

Type RM Length L Ch R = 1 ,118224.9,55.5,57.2,59
XS GIS Cut Line= 5
     1563916.127      290353.343     1563517.649      290254.805
     1563446.303      290192.422     1563368.178      290045.286
     1563170.261      289921.588
#Sta/Elev= 30
       0  847.29    48.9  838.51   156.4  815.68   166.2  812.69   185.7  803.22
   195.5  800.61   205.2  801.19   224.8  806.18   234.6  807.95   244.3   808.6
   254.1  807.98   273.6  804.52   293.2  802.68   312.8  799.22   400.7  793.98
   448.4  793.06     515  794.54   534.6  792.16   554.2  791.62     564   790.5
   573.8  789.04   593.4  788.42  605.35 789.726     613  792.06   632.6  802.62
   642.4  806.56     662  811.37   691.3  815.22   798.3  821.87   905.2  818.62
#Mann= 3 , 0 , 0
       0     .05       0     564    .045       0  605.35     .07       0
#XS Ineff= 2 , 0
          255.85  808.09
Permanent Ineff=
       F       F
Bank Sta=564,605.35
XS Rating Curve= 0 ,0
Exp/Cntr=0.3,0.1

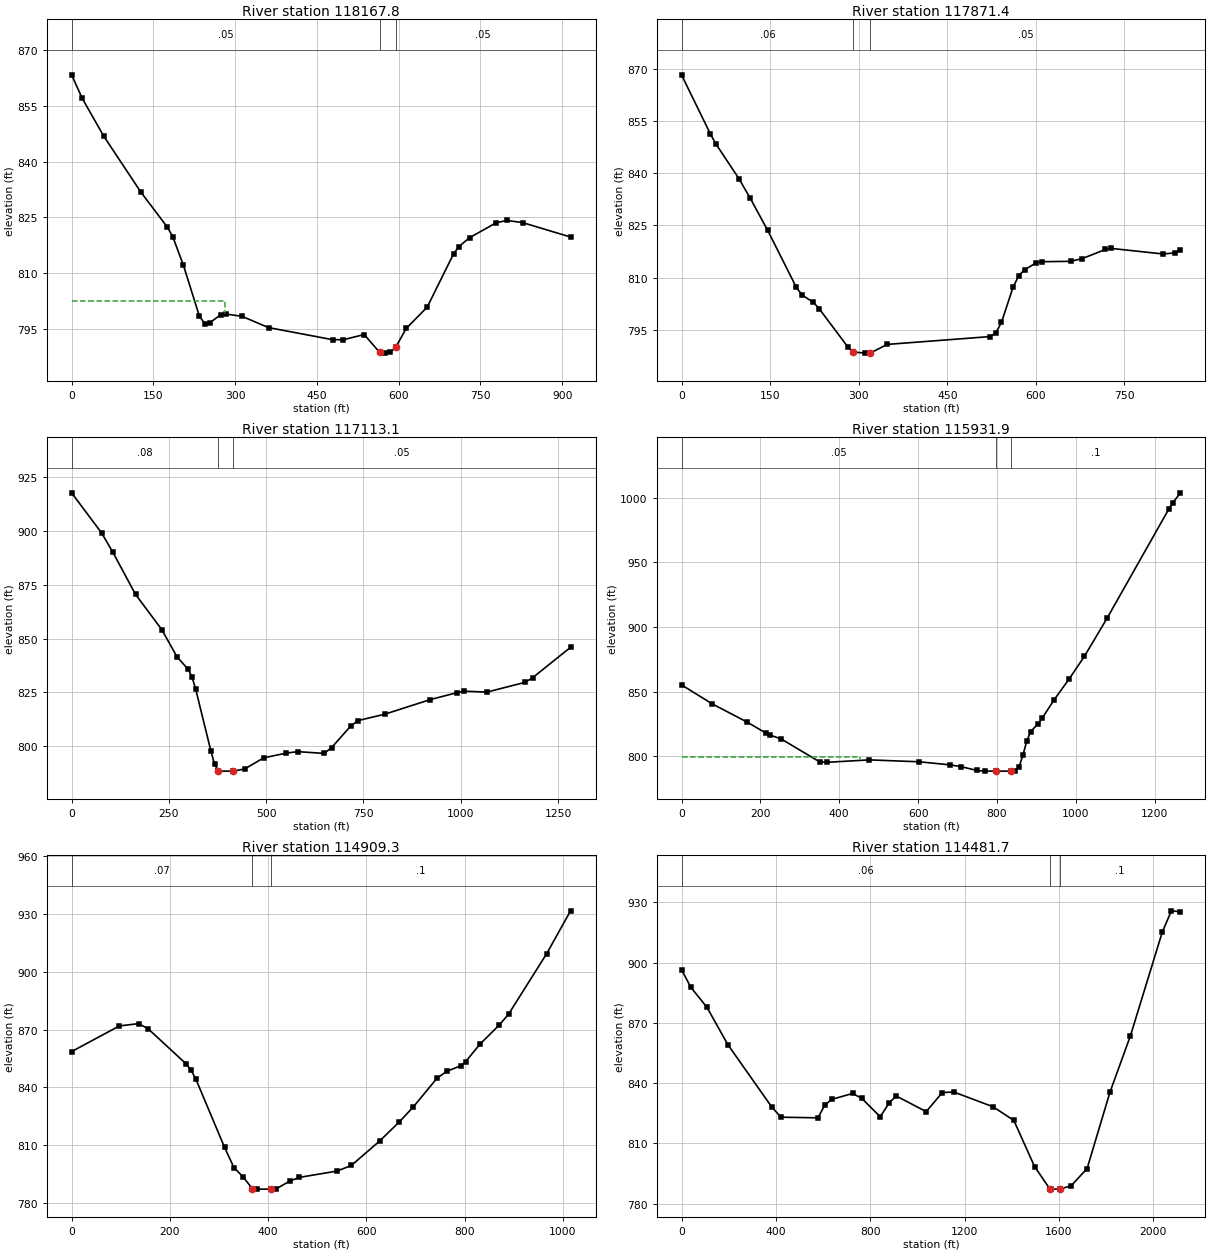
Type RM Length L Ch R = 1 ,118167.8,310.1,296.4,282.5
XS GIS Cut Line= 5
     1563963.002      290277.823     1563551.543      290194.489
     1563484.063      290154.661     1563411.146      289986.693
     1563215.834      289857.786
#Sta/Elev= 30
       0  863.38    19.5  857.03    58.6  846.94   126.9  831.81   175.7  822.33
   185.5  819.78     205  812.12   234.3   798.4   244.1  796.37   253.8  796.59
   273.4  798.76   283.1  798.93   312.4  798.32   361.2  795.28   478.6  792.03
   498.2     792   536.7  793.41   565.3  788.57   575.3   788.4   584.9  788.67
   594.5  789.98   613.8  795.05   652.4  800.82   700.8  815.19   710.5  817.12
     730  819.49   778.8  823.52   798.3  824.15   827.5  823.56   915.3  819.68
#Mann= 3 , 0 , 0
       0     .05       0   565.3    .045       0   594.5     .05       0
#XS Ineff= 2 , 0
          280.94  802.34
Permanent Ineff=
       F       F
Bank Sta=565.3,594.5
XS Rating Curve= 0 ,0
Exp/Cntr=0.3,0.1

Type RM Length L Ch R = 1 ,117871.4,771.8,758.3,744.6
XS GIS Cut Line= 4
     1563967.136      290119.505      1563750.99      289971.068
     1563605.157      289879.922     1563204.115       289791.38
#Sta/Elev= 30
       0   868.2    48.6  851.34    58.3  848.35    97.1  838.46   116.5  832.77
   145.7  823.67   194.2  807.34   203.9  805.08   223.4  802.95   233.1  801.13
   281.3  790.25   290.9  788.74     310   788.4   319.5   788.4   348.2   790.9
   522.2  793.14     532  794.14   541.8  797.21   561.3  807.25   571.1  810.61
   580.9   812.3   600.4  814.27   610.2  814.62   659.1  814.72   678.6  815.51
   717.8  818.12   727.5  818.43   815.5  816.83   835.1  817.13   844.9  817.83
#Mann= 3 , 0 , 0
       0     .06       0   290.9    .045       0   319.5     .05       0
Bank Sta=290.9,319.5
XS Rating Curve= 0 ,0
Exp/Cntr=0.3,0.1

Type RM Length L Ch R = 1 ,117113.1,1162.9,1181.3,1198.7
XS GIS Cut Line= 4
     1564089.532      289293.984     1563826.511       289197.63
     1563303.074      289221.068     1562839.532      289338.255
#Sta/Elev= 30
       0   917.8    77.3  899.08   106.2  890.09   164.2  870.59   231.8  854.18
   270.5  841.67   299.5  835.68   309.2  832.31   318.9  826.47   357.7  797.91
   367.4  791.58  376.28788.6688   377.1   788.4     416   788.4   445.1  789.45
   493.6  794.57   551.8  796.78   580.9  797.46   648.8  796.64   668.2  799.34
   716.8  809.29   736.2  811.91   804.1  814.83   921.2  821.64   989.5  824.85
    1009  825.56  1067.5  825.15  1165.1  829.68  1184.6  831.82  1282.2  845.97
#Mann= 3 , 0 , 0
       0     .08       0  376.28    .045       0     416     .05       0
Bank Sta=376.28,416
XS Rating Curve= 0 ,0
Exp/Cntr=0.3,0.1

Type RM Length L Ch R = 1 ,115931.9,1022.6,1022.6,1021.7
XS GIS Cut Line= 3
     1563972.344      288684.609     1563560.886      288179.401
     1563089.532      287786.172
#Sta/Elev= 30
       0  855.18    77.8   840.5   165.3  826.56     214  817.88   223.7   816.4
   252.8  813.32   350.1  795.61   369.5  795.24   476.5  797.11   602.9  795.63
   680.8  793.27     710  791.83     749  788.91   768.5   788.4   797.7   788.4
   836.7   788.4   846.4   788.7   856.2  791.73   865.9  800.87   875.7  811.77
   885.4  818.98   904.9  825.28   914.6  829.37   943.9  843.17   982.8  859.67
  1021.8  877.32  1080.3  907.37  1236.2  991.56  1245.9  996.25  1265.4 1003.95
#Mann= 3 , 0 , 0
       0     .05       0   797.7    .045       0   836.7      .1       0
#XS Ineff= 2 , 0
          453.36  799.45
Permanent Ineff=
       F       F
Bank Sta=797.7,836.7
XS Rating Curve= 0 ,0
Exp/Cntr=0.3,0.1

Type RM Length L Ch R = 1 ,114909.3,426.7,427.6,428.3
XS GIS Cut Line= 4
     1564672.865      288062.213     1564454.115      287840.859
     1564297.865      287715.859     1563894.219      287413.776
#Sta/Elev= 30
       0  858.56    97.2  871.86   136.2  873.06   155.6  870.41   233.4   852.1
   243.1   848.9   252.8  844.32   311.2  808.92   330.3  798.39   349.3  793.45
   367.9787.3901   377.9   787.2   406.5   787.2     416  787.29   444.6  791.45
   463.7   793.3   540.4  796.58   569.5   799.5   627.6  812.32   666.4  821.93
   695.5  829.86     744  844.83   763.4  848.28   792.5  851.27   802.2   853.4
   831.3  862.48     870  872.23   889.4     878     967  909.41  1015.5  931.58
#Mann= 3 , 0 , 0
       0     .07       0   367.9    .045       0   406.5      .1       0
Bank Sta=367.9,406.5
XS Rating Curve= 0 ,0
Exp/Cntr=0.3,0.1

Type RM Length L Ch R = 1 ,114481.7,360.7,359.4,358.3
XS GIS Cut Line= 6
     1565128.594      288887.734     1564928.074      288221.068
     1564764.011      287700.234     1564691.094      287497.109
     1564417.657      287265.338     1564133.803      287171.588
#Sta/Elev= 30
       0  896.49    39.2   887.7   107.9  877.69   196.1  859.18   382.4  828.11
   421.6  823.01   578.5  822.69   607.9  829.11   637.3  831.89   725.4  834.83
   764.4  832.38   842.4  823.21   881.4  830.31   910.7  833.55  1037.5  825.77
  1105.7  835.28  1154.5  835.54  1320.7   828.2    1409   821.4  1496.8  798.45
 1561.71787.2805  1564.6   787.2  1603.4   787.2  1651.8  788.87  1719.6  797.46
  1816.5  835.46  1903.3  863.54  2038.3  915.16  2076.9  925.73  2115.4  925.25
#Mann= 3 , 0 , 0
       0     .06       0 1561.71    .045       0  1603.4      .1       0
Bank Sta=1561.71,1603.4
XS Rating Curve= 0 ,0
Exp/Cntr=0.3,0.1

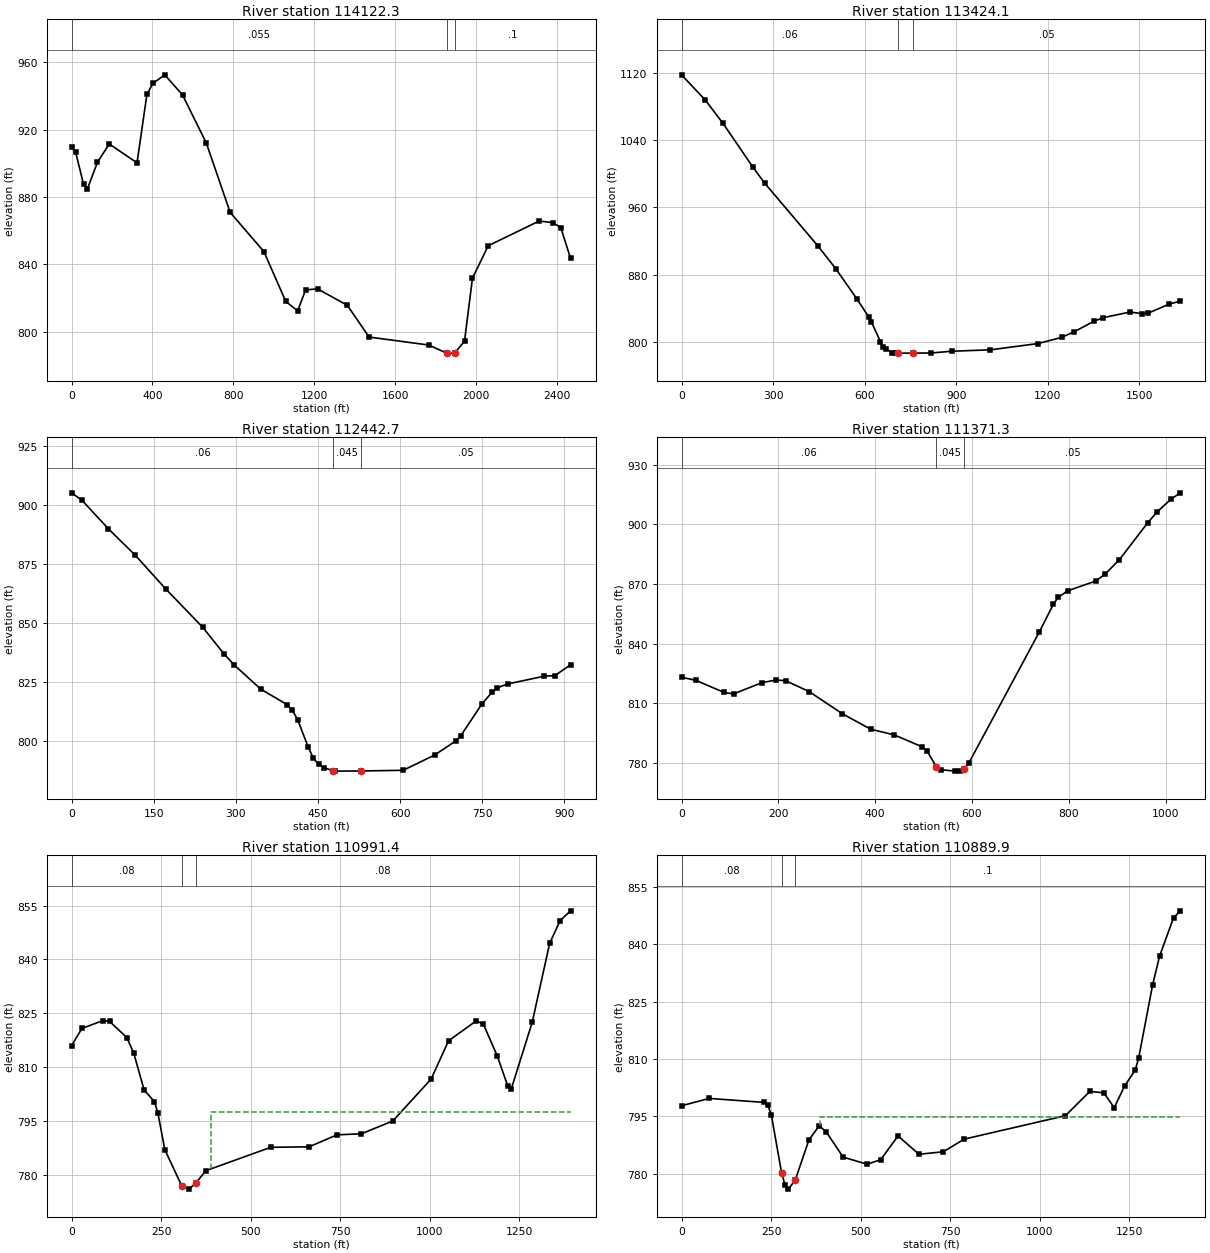
Type RM Length L Ch R = 1 ,114122.3,715.3,698.2,680.7
XS GIS Cut Line= 5
     1566144.219      288399.019      1565505.33      287819.158
     1564991.442      287277.491     1564689.358       287041.38
     1564241.442      286881.658
#Sta/Elev= 30
       0  909.44    19.6  906.72    58.8  887.57    78.4   884.8   127.5  900.48
   186.3  911.43   323.6   900.2   372.6  940.89     402  947.41   460.8  952.49
     549  940.48   666.7  911.89   784.4  870.76   951.2  847.54  1059.3  817.94
  1118.2  812.25  1157.5  824.73  1216.5  825.36  1363.8  815.62  1471.9  796.74
  1766.7  792.01  1855.2   787.2  1894.5   787.2  1943.7  794.26    1983  831.67
  2060.8  850.96  2313.1  865.66    2381  864.68  2419.9  861.78  2468.4  843.48
#Mann= 3 , 0 , 0
       0    .055       0  1855.2    .045       0  1894.5      .1       0
Bank Sta=1855.2,1894.5
XS Rating Curve= 0 ,0
Exp/Cntr=0.3,0.1

Type RM Length L Ch R = 1 ,113424.1,1006.1,981.4,956.4
XS GIS Cut Line= 4
     1565987.969      286669.852     1565404.636      286655.963
     1565074.775      286690.686     1564362.969      286798.324
#Sta/Elev= 30
       0 1117.33    77.8 1087.46   136.2 1059.61   233.4 1008.12   272.3  988.92
   447.4  914.16   505.7  887.27   573.8  851.99   612.8  830.46   622.5  824.03
   651.8  800.94   661.5  794.79   671.3  791.75   690.8  787.75   700.6   787.2
   710.3   787.2   759.1   787.2   817.6  787.37   885.9  789.46  1012.5  791.13
  1168.1  798.54    1246  805.92  1284.9  812.22    1353  825.23  1382.1  829.26
  1469.7  835.96  1508.6  834.12  1528.1  834.38  1596.2  845.11  1635.1  849.03
#Mann= 3 , 0 , 0
       0     .06       0   710.3    .045       0   759.1     .05       0
Bank Sta=710.3,759.1
XS Rating Curve= 0 ,0
Exp/Cntr=0.3,0.1

Type RM Length L Ch R = 1 ,112442.7,1057.2,1071.4,1085.8
XS GIS Cut Line= 4
     1564609.497      285944.158     1564460.192      286201.102
     1564342.136      286506.658     1564196.303      286753.186
#Sta/Elev= 30
       0  905.24    19.2  902.02    67.1  889.99     115  879.07   172.6   864.3
   239.7  848.14     278  837.01   297.2  832.17   345.4  821.98   393.5  815.42
   403.2  812.96   412.8  809.03   432.1  797.38   441.7  792.56   451.3  790.06
     461  788.65  478.01787.2935   480.2   787.2   528.4  787.27   605.5  787.55
   662.9  794.02   701.1  799.92   710.7   802.2   748.9  815.57     768  820.74
   777.5  822.56   796.6  824.18   863.4  827.49   882.5  827.71   911.2   832.3
#Mann= 3 , 0 , 0
       0     .06       0  478.01    .045       0   528.4     .05       0
Bank Sta=478.01,528.4
XS Rating Curve= 0 ,0
Exp/Cntr=0.3,0.1

Type RM Length L Ch R = 1 ,111371.3,386.4,379.9,373.3
XS GIS Cut Line= 4
      1563971.91      285647.717     1563592.136      285803.967
     1563364.271      285949.366     1563116.876      286196.762
#Sta/Elev= 30
       0  823.17    29.3  821.67      88  815.54   107.6  814.82   166.2  820.48
   195.6   821.8   215.1  821.46     264  815.94   332.4  804.82   391.1  797.05
   439.6  794.21   497.5  788.17   507.2  786.17   526.5  778.15   536.2   776.7
   565.1     776   574.8  776.06   584.4  777.13   594.1  780.32   739.3  845.99
   768.4  859.96   778.2  863.32   797.6  866.62   855.9  871.57   875.3  875.08
   904.5  882.25   962.8  900.73   982.2  906.21  1011.4  912.76  1030.8  915.89
#Mann= 3 , 0 , 0
       0     .06       0   526.5    .045       0   584.4     .05       0
Bank Sta=526.5,584.4
XS Rating Curve= 0 ,0
Exp/Cntr=0.3,0.1

Type RM Length L Ch R = 1 ,110991.4,102.2,101.5,100.7
XS GIS Cut Line= 4
     1563631.199      285350.408     1563403.334      285476.276
      1563188.49       285693.29     1562626.424      286300.929
#Sta/Elev= 30
       0  816.02    28.9  820.78    86.8  822.94   106.1  822.73   154.3  818.22
   173.5   813.9   202.5  803.64   231.4  800.36     241  797.16   260.3  787.01
     308  776.82   327.1  776.02   346.2  777.62   374.8  781.15   556.2  787.67
   663.1   787.8     741  791.14   809.1  791.43   896.8  794.99  1003.9  806.65
  1052.6  817.33  1130.5  822.92    1150  821.96  1188.9  813.07  1218.1  804.69
  1227.9  803.95  1286.3  822.48    1335  844.46  1364.2  850.81  1393.4  853.53
#Mann= 3 , 0 , 0
       0     .08       0     308    .045       0   346.2     .08       0
#XS Ineff= 2 , 0
                          389.37           797.4
Permanent Ineff=
       F       F
Bank Sta=308,346.2
XS Rating Curve= 0 ,0
Exp/Cntr=0.3,0.1

Type RM Length L Ch R = 1 ,110889.9,250.4,279.6,308.9
XS GIS Cut Line= 4
     1563589.966      285272.283     1563362.101      285398.151
     1563147.258      285615.165     1562585.192      286222.804
#Sta/Elev= 30
       0  797.75    77.1  799.68   231.4  798.63     241  797.88   250.7  795.44
   279.4  780.23     289  777.04   298.5  775.94   317.6  778.31   355.8  788.82
   384.4   792.5   403.5  791.01   451.2  784.33     518  782.45   556.2  783.64
   604.6  789.86   663.1  785.06   731.2  785.72   789.7  789.03  1072.1  795.16
  1140.2   801.5  1179.2  801.15  1208.4  797.26  1237.6  802.96  1266.8  807.06
  1276.6   810.2  1315.5  829.35    1335  836.89    1374  846.95  1393.4  848.77
#Mann= 3 , 0 , 0
       0     .08       0   279.4    .045       0   317.6      .1       0
#XS Ineff= 2 , 0
                          385.65          794.83
Permanent Ineff=
       F       F
Bank Sta=279.4,317.6
XS Rating Curve= 0 ,0
Exp/Cntr=0.3,0.1