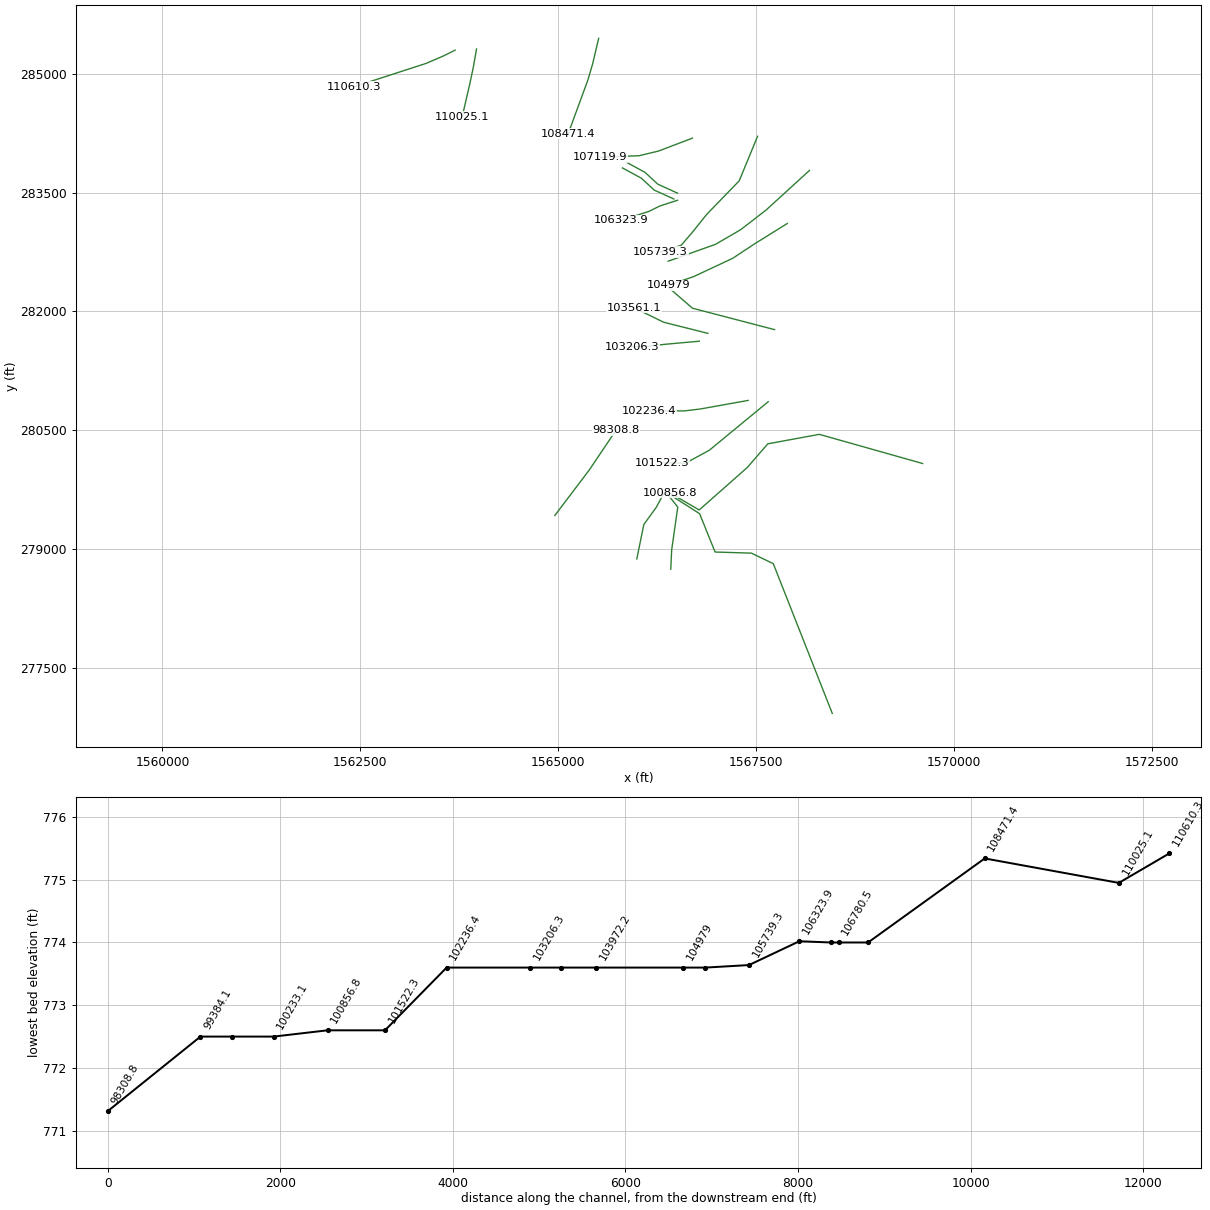
HEC-RAS study NFHGHSRV1.prj: NFHGHSRV1

--- NFHGHSRV1.g01 (geometry) --- (continued)

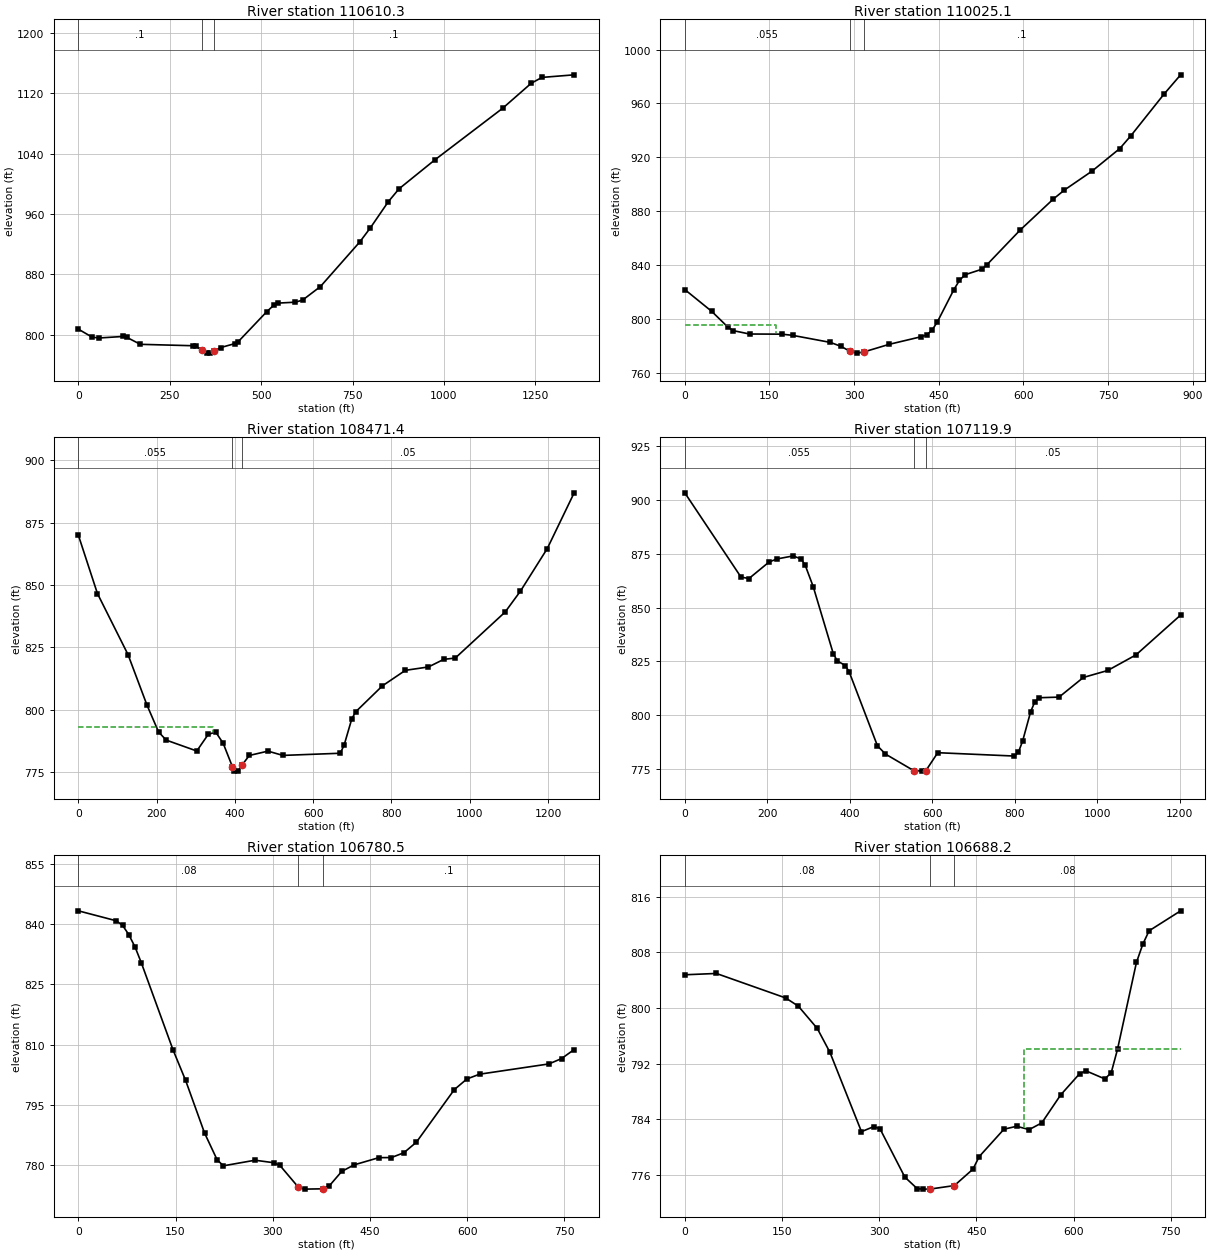
Type RM Length L Ch R = 1 ,110610.3,563.4,585.2,606.9
XS GIS Cut Line= 4
     1563698.473      285300.495     1563555.244       285228.88
     1563327.379      285131.224     1562425.328      284838.934
#Sta/Elev= 30
       0  807.23    37.7   796.6    56.5   795.5   122.5  797.51   131.9   796.5
   169.7  787.09   312.7  785.23   322.2   784.5  337.44779.2993   350.8  775.42
   360.4  775.57   369.9   777.7     389  782.74   427.6  787.97   437.4  790.62
   515.6  830.46   535.1  839.14   544.9   841.7   593.8  842.97   613.3  845.68
   662.2  863.66   769.7   922.7   799.1  941.67   847.9  976.16   877.3  993.26
     975 1031.52  1160.8 1100.07    1239 1133.24  1268.3 1140.94  1356.3 1144.36
#Mann= 3 , 0 , 0
       0      .1       0  337.44    .045       0   369.9      .1       0
Bank Sta=337.44,369.9
XS Rating Curve= 0 ,0
Exp/Cntr=0.3,0.1

Type RM Length L Ch R = 1 ,110025.1,1554.4,1553.7,1551
XS GIS Cut Line= 4
     1563967.863      285313.977     1563924.601      285069.158
     1563882.935      284874.713     1563785.712      284454.574
#Sta/Elev= 30
       0  822.08    47.8  805.87    76.5  794.18    86.1   791.6   114.7  789.12
   172.1  789.01   191.2  788.12   258.1  782.89     277  779.94  292.61776.3101
   305.4  774.95  317.28775.8132   362.2  781.47   419.1  787.13   428.5  788.45
     438  791.88   447.5  798.02   476.9  822.08   486.7   828.8   496.5  833.04
   525.9  837.05   535.7   840.6   594.5  866.26   653.3  889.25   672.9  895.89
   721.9  909.94   770.9  926.61   790.5  936.08   849.3  966.96   878.7  981.25
#Mann= 3 , 0 , 0
       0    .055       0  292.61    .045       0  317.28      .1       0
#XS Ineff= 2 , 0
          162.21   796.1
Permanent Ineff=
       F       F
Bank Sta=292.61,317.28
XS Rating Curve= 0 ,0
Exp/Cntr=0.3,0.1

Type RM Length L Ch R = 1 ,108471.4,1375.1,1351.5,1327.7
XS GIS Cut Line= 4
     1565510.828      285449.101     1565434.439      285126.184
     1565375.411      284924.796     1565125.411       284244.24
#Sta/Elev= 30
       0  869.98    48.8  846.55   126.9  822.08   175.7  801.68     205  791.05
   224.5  787.78   302.6  783.41   331.8  790.06   350.9  791.02     370  786.51
  393.55777.1396   398.6  775.48   408.1  775.34   417.7  777.67   436.8  781.62
   484.5  783.36   522.6  781.64   669.1  782.51   678.9  785.71   698.4  796.19
   708.2  799.07   776.8  809.53   835.6  815.76   894.4  817.11   933.6  820.16
     963  820.68  1090.4  839.14  1129.6  847.54  1198.1   864.6  1266.7  886.93
#Mann= 3 , 0 , 0
       0    .055       0  393.55    .045       0   417.7     .05       0
#XS Ineff= 2 , 0
          344.98  792.98
Permanent Ineff=
       F       F
Bank Sta=393.55,417.7
XS Rating Curve= 0 ,0
Exp/Cntr=0.3,0.1

Type RM Length L Ch R = 1 ,107119.9,361.1,339.4,316.5
XS GIS Cut Line= 4
     1566694.856      284188.684     1566267.772       284025.49
     1566021.244      283966.462     1565530.439       283946.83
#Sta/Elev= 30
       0  903.43   136.2  864.24   155.6  863.58   204.3  871.26   223.7  872.69
   262.6  874.09   282.1  872.66   291.8  869.78   311.3   859.8   359.9  828.65
   369.6  825.26   389.1  823.12   398.8  819.99     467  785.77   486.4  781.94
   554.7  774.26   574.2     774     584  774.12   613.2  782.57   799.1  781.01
   808.9  782.91   818.8  787.93   838.4  801.67   848.2  806.09   858.1  808.13
   907.2  808.42   966.1  817.56  1025.1   820.8  1093.8  828.07  1201.9  846.58
#Mann= 3 , 0 , 0
       0    .055       0   554.7    .045       0     584     .05       0
Bank Sta=554.7,584
XS Rating Curve= 0 ,0
Exp/Cntr=0.3,0.1

Type RM Length L Ch R = 1 ,106780.5,91.7,92.3,92.7
XS GIS Cut Line= 4
     1566505.619       283494.24     1566257.356      283607.087
     1566095.897      283756.393     1565856.314      283886.601
#Sta/Elev= 30
       0  843.31    58.4  840.84    68.2  839.71    77.9  837.38    87.7  834.24
    97.4  830.29   146.1  808.71   165.6  801.07   194.8  787.98   214.3  781.28
     224  779.81   272.7   781.2   301.4  780.58     311  779.93   339.6  774.48
   349.2     774   377.9  774.08   387.4  774.82   406.6  778.42   425.7  780.04
   463.9  781.84   483.1  781.86   502.4  783.05   521.8  785.69   580.3  798.78
   599.7  801.43   619.2  802.62   726.3  805.18   745.8  806.51   765.3  808.76
#Mann= 3 , 0 , 0
       0     .08       0   339.6    .045       0   377.9      .1       0
Bank Sta=339.6,377.9
XS Rating Curve= 0 ,0
Exp/Cntr=0.3,0.1

Type RM Length L Ch R = 1 ,106688.2,338.1,364.3,391.5
XS GIS Cut Line= 4
     1566460.481      283419.587     1566212.217      283532.434
     1566050.758       283681.74     1565811.175      283811.948
#Sta/Elev= 30
       0  804.77    48.7  804.96   155.8  801.44   175.3  800.26   204.5  797.06
     224  793.64   272.7  782.25   291.8  782.98   301.4  782.64   339.6  775.73
   358.8  774.06   368.3     774   377.9     774   416.1  774.51   444.8  776.87
   454.4  778.67   492.6   782.6   512.1  783.02   531.6  782.55     551  783.51
   580.3  787.54   609.5  790.58   619.2  790.98   648.4  789.82   658.2  790.72
   667.9  794.08   697.1  806.54   706.9  809.15   716.6  811.08   765.3  813.95
#Mann= 3 , 0 , 0
       0     .08       0   377.9    .045       0   416.1     .08       0
#XS Ineff= 2 , 0
                          523.08          794.08
Permanent Ineff=
       F       F
Bank Sta=377.9,416.1
XS Rating Curve= 0 ,0
Exp/Cntr=0.3,0.1

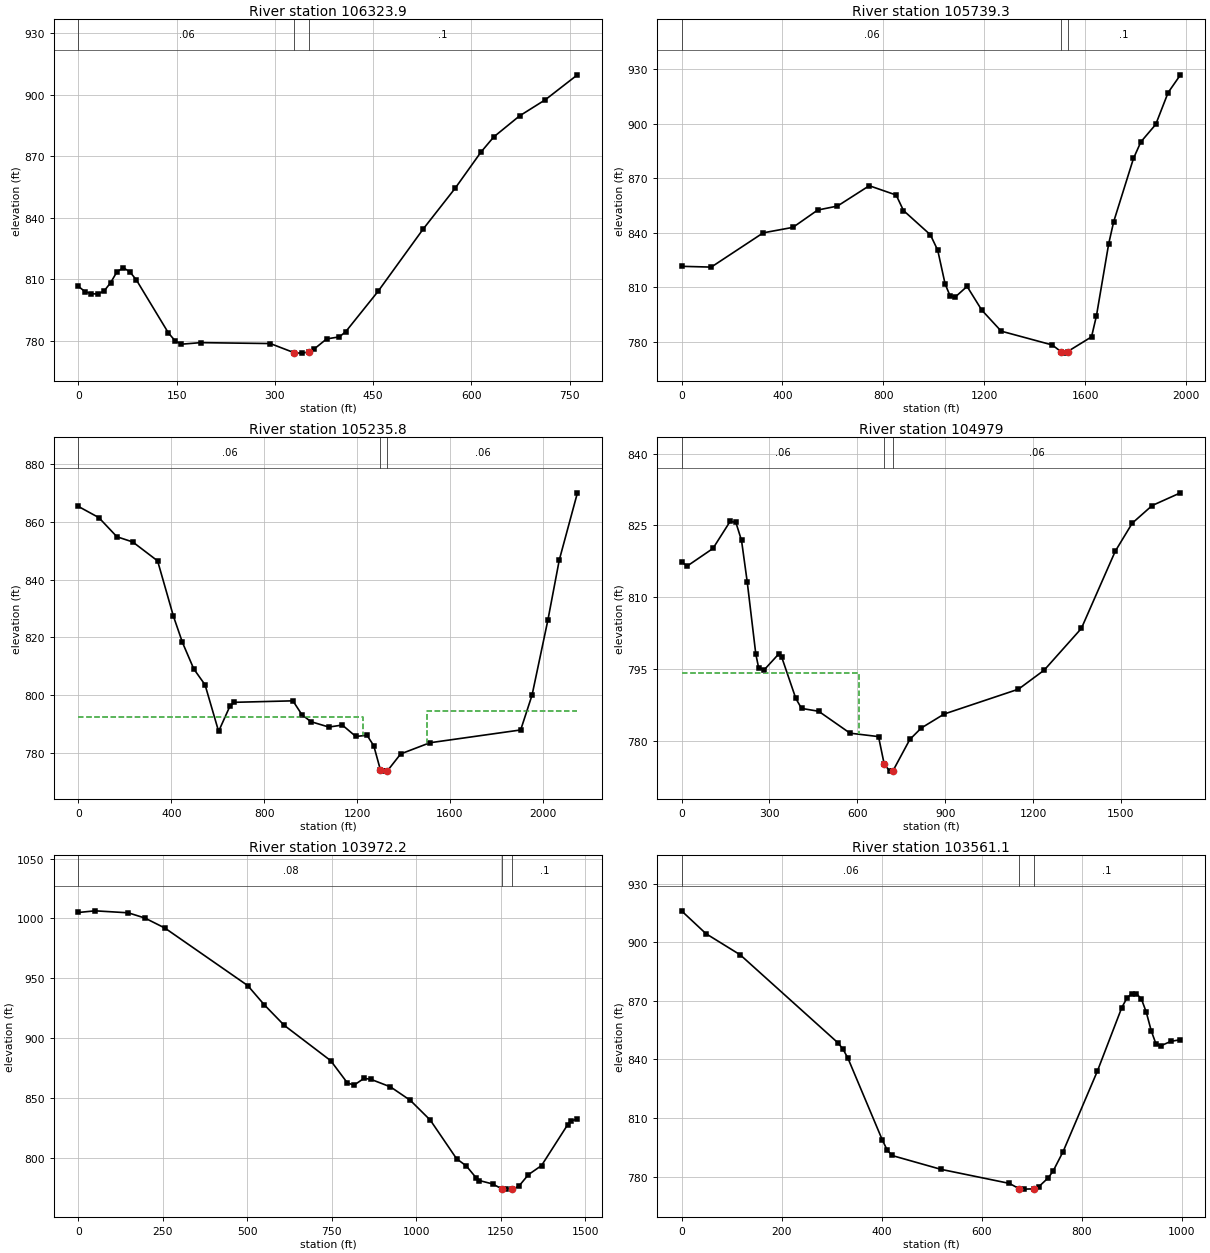
Type RM Length L Ch R = 1 ,106323.9,575.5,584.6,593.3
XS GIS Cut Line= 4
     1566507.356      283403.962     1566283.397      283331.046
     1566146.244      283263.337     1565790.342       283150.49
#Sta/Elev= 30
       0  806.52     9.8  804.03    19.6  802.94    29.4  802.85    39.2  804.33
    49.1  808.36    58.9  813.74    68.7  815.58    78.5   813.6    88.3  809.72
   137.4   783.8   147.2  780.15     157  778.37   186.5  779.13   292.9  778.69
  329.47774.1953   340.7  774.02  351.36774.5418   359.8  776.01   378.9  780.95
   398.3  781.94   408.1   784.5   457.3  804.09     526  834.38   575.2  854.42
   614.5     872   634.1  879.41   673.4  889.62   712.7  897.49   761.8  909.65
#Mann= 3 , 0 , 0
       0     .06       0  329.47    .045       0  351.36      .1       0
Bank Sta=329.47,351.36
XS Rating Curve= 0 ,0
Exp/Cntr=0.3,0.1

Type RM Length L Ch R = 1 ,105739.3,510,503.5,495.8
XS GIS Cut Line= 6
     1567517.776      284211.547     1567286.005      283649.047
     1566874.547      283224.567     1566700.064      283006.393
     1566554.231      282836.254     1566293.814      282749.448
#Sta/Elev= 30
       0  821.48   117.8  821.05   323.8  839.93   441.6  842.95   539.7  852.49
   618.1  854.69   744.1   865.9   850.7  860.76   879.7  852.22   986.3  838.86
  1015.4  830.36  1044.5  811.88  1063.9  805.32  1083.2  804.35  1131.7  810.41
  1189.9  797.37    1267  785.75  1469.3  778.14  1504.9  774.35  1517.9  773.64
 1530.48774.5167    1625   782.6  1644.5  794.22  1693.2  834.04  1712.8  846.07
  1791.2  880.91  1820.6  890.07  1879.5  899.68  1928.5  917.21  1977.5  927.01
#Mann= 3 , 0 , 0
       0     .06       0  1504.9    .045       0 1530.48      .1       0
Bank Sta=1504.9,1530.48
XS Rating Curve= 0 ,0
Exp/Cntr=0.3,0.1

Type RM Length L Ch R = 1 ,105235.8,255.5,256.8,258.5
XS GIS Cut Line= 5
     1568173.158      283780.123     1567626.432      283281.159
     1567305.099      283032.434      1566987.39      282847.539
     1566388.432      282633.997
#Sta/Elev= 30
       0  865.39    87.6  861.54   165.6  854.89   233.7  853.09   340.9  846.52
     409  827.35     448  818.22   496.7  809.06   545.4  803.53   603.8   787.4
   652.5  796.12     672  797.47     924  797.98   962.7  793.18  1001.4  790.76
  1078.8  788.89  1136.9  789.58  1194.9  785.63  1243.3  786.03  1272.3  782.41
  1301.3  773.93    1311   773.6 1330.72773.6585  1388.4  779.57  1514.1  783.44
  1905.4  787.88  1954.4  799.96  2022.8  826.06  2071.8  846.85    2150  870.13
#Mann= 3 , 0 , 0
       0     .06       0  1301.3    .045       0 1330.72     .06       0
#XS Ineff= 2 , 0
         1226.75  792.47 1501.33          794.38
Permanent Ineff=
       F       F
Bank Sta=1301.3,1330.72
XS Rating Curve= 0 ,0
Exp/Cntr=0.3,0.1

Type RM Length L Ch R = 1 ,104979  ,1035.8,1006.8,977.1
XS GIS Cut Line= 5
      1567893.64      283110.559     1567479.578      282852.747
     1567203.536      282670.455     1566708.744      282438.684
     1566388.432      282329.309
#Sta/Elev= 30
       0  817.36    19.5   816.5   107.3  820.17   165.8  825.82   185.4  825.65
   204.9  821.84   224.4  813.14   253.6  798.08   263.4  795.18   282.9  794.83
   331.7  798.09   341.4  797.56   390.2   788.8   409.7  786.72   468.2  786.12
   575.3  781.54   672.6  780.82   692.1  775.02   711.5   773.6   721.3   773.6
   779.6  780.24   818.6  782.62   896.6  785.54  1150.3  790.74  1238.1  794.72
    1365  803.44    1481  819.62    1539  825.48  1606.7  829.15  1703.4  831.81
#Mann= 3 , 0 , 0
       0     .06       0   692.1    .045       0   721.3     .06       0
#XS Ineff= 2 , 0
          607.44  794.14
Permanent Ineff=
       F       F
Bank Sta=692.1,721.3
XS Rating Curve= 0 ,0
Exp/Cntr=0.3,0.1

Type RM Length L Ch R = 1 ,103972.2,405.5,411.1,416.7
XS GIS Cut Line= 3
     1567732.186      281769.706     1566695.724      282040.247
     1566388.432      282305.872
#Sta/Elev= 30
       0 1004.98    49.1 1006.36   147.4  1004.7   196.6 1000.33   255.5  992.02
   501.2  943.83   550.3  927.72   609.3  910.57   746.9  881.01     796   862.5
   815.7  860.55   845.2  866.19   864.8  865.54   923.8  859.12   982.7  847.82
  1041.7  831.31  1119.5  799.04  1148.6  792.93  1177.6     783  1187.2  780.76
  1225.9  777.95  1254.9  773.67  1264.6   773.6    1284  773.61  1303.3  775.84
  1332.3  785.73    1371  793.29  1448.4  827.45    1458  830.75  1477.4  832.14
#Mann= 3 , 0 , 0
       0     .08       0  1254.9    .045       0    1284      .1       0
Bank Sta=1254.9,1284
XS Rating Curve= 0 ,0
Exp/Cntr=0.3,0.1

Type RM Length L Ch R = 1 ,103561.1,341.9,354.8,367.7
XS GIS Cut Line= 3
     1566891.036      281722.539      1566331.14      281863.164
     1565953.536      282048.059
#Sta/Elev= 30
       0  916.07    48.9  904.37   117.4  893.54   313.1  848.42   322.9  845.24
   332.7  840.66   401.2  798.96     411  793.72   420.7  790.83   518.6  783.74
   655.5  776.54   675.1  773.83   684.8   773.6   704.4  773.74   714.2   774.8
   733.7  779.48   743.5  783.06   763.1  792.86   831.5  833.98   880.4  866.56
   890.2  871.19     900  873.72   909.7  873.65   919.5  871.01   929.3   864.2
   939.1   854.8   948.8  847.85   958.6  846.99   978.2  849.23   997.7   850.1
#Mann= 3 , 0 , 0
       0     .06       0   675.1    .045       0   704.4      .1       0
Bank Sta=675.1,704.4
XS Rating Curve= 0 ,0
Exp/Cntr=0.3,0.1

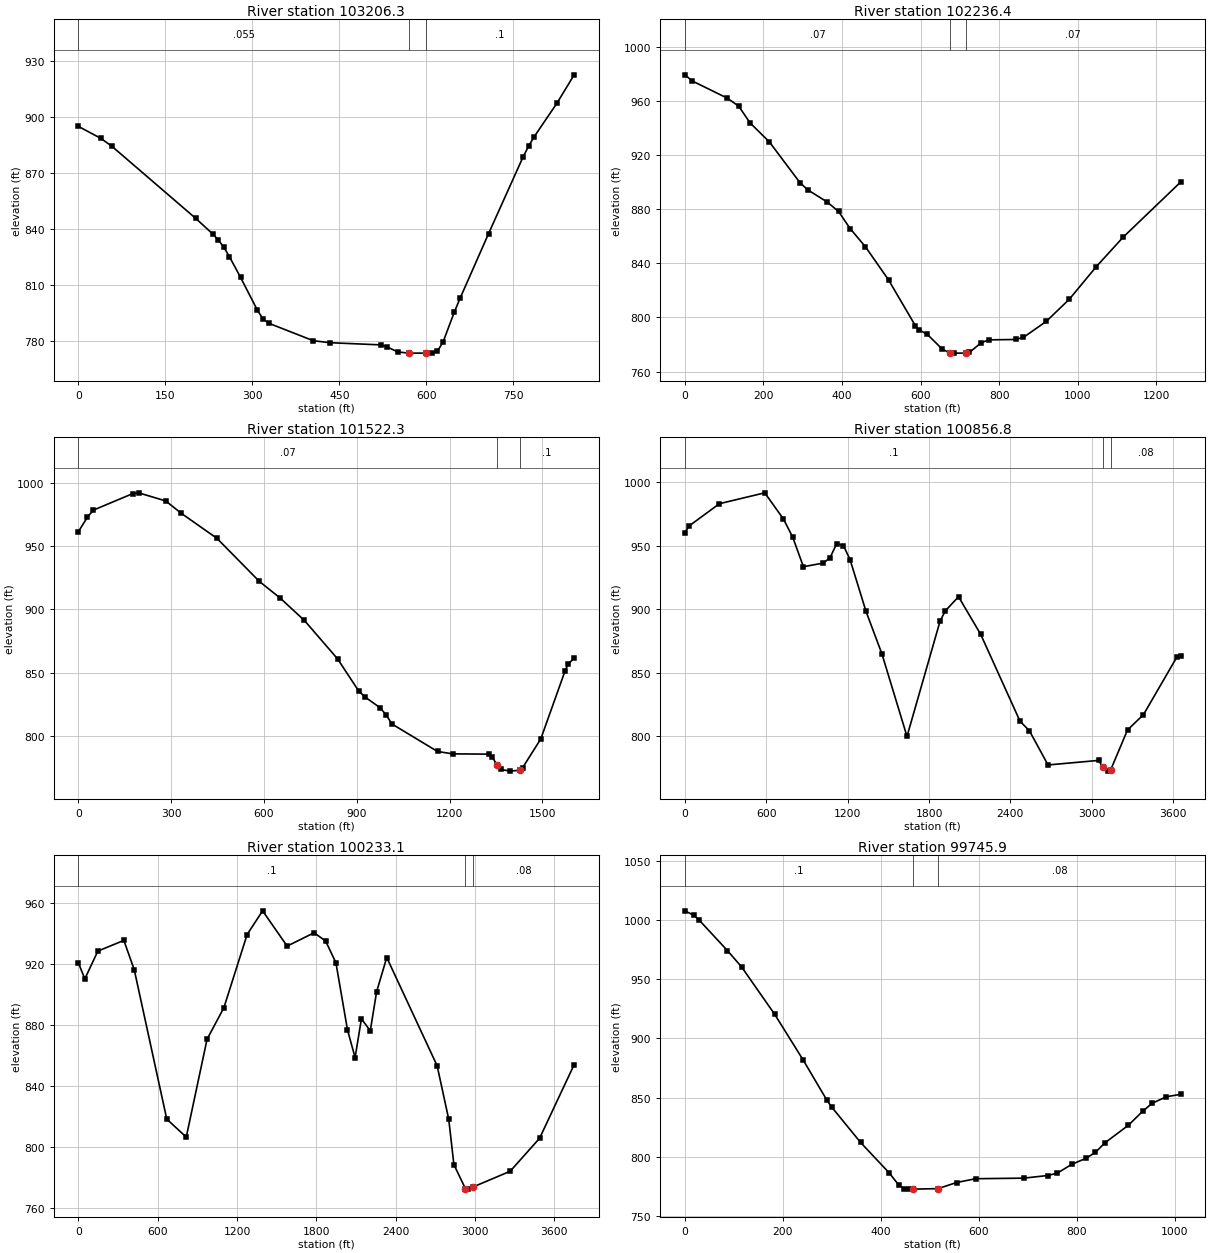
Type RM Length L Ch R = 1 ,103206.3,969.7,969.9,969.9
XS GIS Cut Line= 4
     1566781.661       281623.58     1566349.369      281584.518
     1566146.244       281561.08     1565930.099      281553.268
#Sta/Elev= 30
       0   894.9    38.6  888.51    57.9  884.24   202.6  845.62   231.5   837.4
   241.1  834.24   250.8  830.24   260.4  825.25   279.7   814.1   308.7  796.57
   318.3  791.93     328  789.62   405.1  780.24     434  779.17   521.7  778.01
   531.4  777.05   550.9  774.21   570.4   773.6   599.6   773.6   609.3   773.6
     619  774.59   628.8  779.59   648.4  795.72   658.2  802.99   707.3  837.57
   766.3  878.25   776.2  884.32     786  889.42   825.3  907.38   854.8  922.47
#Mann= 3 , 0 , 0
       0    .055       0   570.4    .045       0   599.6      .1       0
Bank Sta=570.4,599.6
XS Rating Curve= 0 ,0
Exp/Cntr=0.3,0.1

Type RM Length L Ch R = 1 ,102236.4,717,714.1,711
XS GIS Cut Line= 4
     1567398.852      280875.609     1566792.078      280766.809
     1566596.765      280743.372     1566147.811      280744.316
#Sta/Elev= 30
       0  979.36    19.6  974.73   107.6  962.19     137  956.26   166.3  943.77
   215.3  929.75   293.6  899.46   313.1   894.3     362  885.42   391.4  878.33
   420.8   865.7   459.9  852.19   518.6  827.74   587.1  793.77   596.9  790.65
   616.4  787.73   655.8  776.44   675.5  773.64   685.3   773.6   714.8   773.6
   724.6   774.1   754.2  781.25   773.8   783.4   842.4  783.69     862  785.24
   920.5  797.15   979.1  813.56  1047.4  837.52  1115.7  859.29  1262.1  900.07
#Mann= 3 , 0 , 0
       0     .07       0   675.5    .045       0   714.8     .07       0
Bank Sta=675.5,714.8
XS Rating Curve= 0 ,0
Exp/Cntr=0.3,0.1

Type RM Length L Ch R = 1 ,101522.3,648.3,665.5,682.5
XS GIS Cut Line= 5
     1567652.051      280858.784     1566907.259      280245.502
     1566605.176       280081.44     1566438.509      280086.648
     1566310.905      280086.648
#Sta/Elev= 30
       0  961.21    29.2  972.64    48.7  978.28   175.4  991.24   194.9   991.9
   282.6   985.5   331.3  976.04   448.3  955.98   584.7  922.22   652.9  908.88
   730.9   891.3   838.1  861.05   906.3  835.76   925.8  831.18   974.6  822.72
   994.3  817.18  1013.9  809.73  1161.2  788.08  1210.3  786.21  1328.2  785.98
    1338  783.87  1353.4  777.37  1367.4   773.9  1395.1   772.6 1428.15773.3112
  1436.1  775.25  1494.9   797.9  1573.5  851.58  1583.3  856.82  1602.9  861.73
#Mann= 3 , 0 , 0
       0     .07       0  1353.4    .045       0 1428.15      .1       0
Bank Sta=1353.4,1428.15
XS Rating Curve= 0 ,0
Exp/Cntr=0.3,0.1

Type RM Length L Ch R = 1 ,100856.8,667.4,623.7,579.4
XS GIS Cut Line= 6
     1569601.977      280078.734      1568297.55      280447.007
     1567646.509      280327.215     1567388.262      280028.604
     1566780.623      279491.928     1566408.227      279708.074
#Sta/Elev= 30
       0     960    29.5  965.48   255.4  983.17   589.3  991.72   726.8  971.14
   795.6  956.76   874.2  933.53  1021.5  936.43  1070.6  940.68  1119.7  951.75
  1168.8  950.22  1217.9  939.17  1335.8   898.3  1452.8  864.94  1637.7  799.93
  1881.1   890.6    1920  898.75  2017.4  909.94  2181.1  880.24    2471  811.84
  2539.7  804.41  2677.1  777.46  3049.9  781.04  3079.3  775.96    3117   772.6
 3139.25773.6354  3262.9  805.01  3380.4  817.06    3625  862.07  3654.4  863.18
#Mann= 3 , 0 , 0
       0      .1       0  3079.3    .045       0 3139.25     .08       0
Bank Sta=3079.3,3139.25
XS Rating Curve= 0 ,0
Exp/Cntr=0.3,0.1

Type RM Length L Ch R = 1 ,100233.1,498.4,487.2,476.4
XS GIS Cut Line= 6
     1568461.352      276922.484     1567716.561      278813.109
     1567440.515      278946.497     1566981.144      278960.678
     1566785.832      279445.053     1566426.457       279674.22
#Sta/Elev= 30
       0  920.91    49.2  910.38   147.6  928.57   344.3  935.59     423  916.35
   668.9  818.41   816.4  806.62   973.8  870.78  1101.1  891.47  1276.8  939.44
    1394  954.98  1579.5  931.84  1783.5   940.6  1870.9  935.16  1948.6  920.91
    2036  876.95  2093.5  858.72  2141.4  884.16  2208.5  876.34  2256.4  901.95
    2333  924.37  2714.2  853.39  2802.2  818.19  2840.9  788.59    2928  772.82
  2946.8   772.5    2986  773.92  3266.5   784.2  3489.2  805.85  3750.7  854.14
#Mann= 3 , 0 , 0
       0      .1       0    2928    .045       0    2986     .08       0
Bank Sta=2928,2986
XS Rating Curve= 0 ,0
Exp/Cntr=0.3,0.1

Type RM Length L Ch R = 1 ,99745.9 ,373.3,361.7,349.7
XS GIS Cut Line= 4
     1566421.248      278744.533     1566432.703      278985.559
      1566509.79      279528.387     1566371.769      279702.866
#Sta/Elev= 30
       0 1007.93    19.3    1004      29 1000.23    86.9  974.35   115.8  960.53
   183.4  920.42   241.3  881.94   290.2  847.63     300  841.83   358.8  811.98
   417.5   786.1   437.1  775.71   446.9  772.99   456.7   772.5   466.5   772.5
  517.03 772.923   554.6  778.09   593.8  781.31   691.7  781.78   740.6  784.02
   760.2     786   789.6  793.43   818.6  798.52   837.9  803.55   857.3  811.59
   905.6  826.62   934.7  838.44     954  845.16     983  850.65    1012  852.69
#Mann= 3 , 0 , 0
       0      .1       0   466.5    .045       0  517.03     .08       0
Bank Sta=466.5,517.03
XS Rating Curve= 0 ,0
Exp/Cntr=0.3,0.1

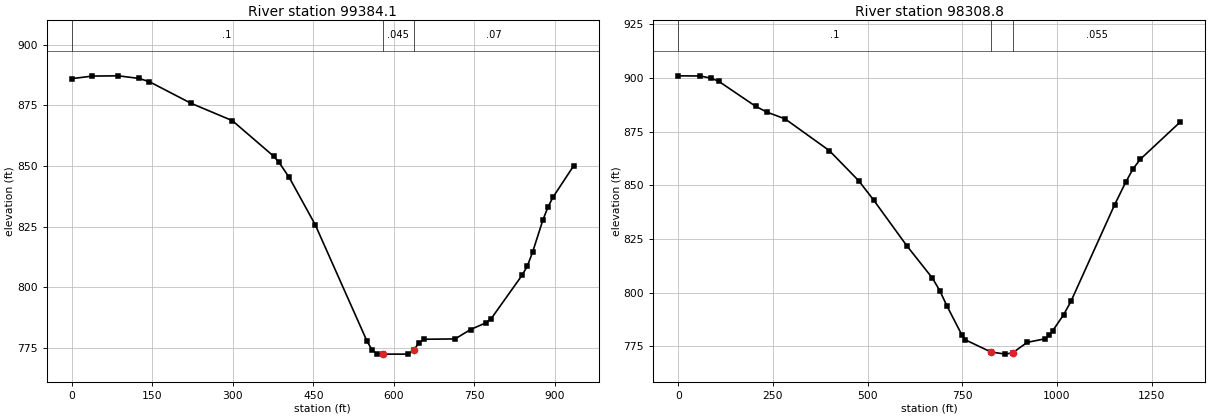
Type RM Length L Ch R = 1 ,99384.1 ,1074.9,1075.3,1074.9
XS GIS Cut Line= 4
     1565992.599       278873.58      1566081.14      279308.476
     1566239.994      279527.226     1566344.161      279722.539
#Sta/Elev= 30
       0  885.95    38.6  887.01    86.8  887.11   125.4  886.03   144.7  884.68
   221.9  875.83   299.1  868.66   376.3  853.98   385.9  851.54   405.2  845.25
   453.5  825.84     550  777.89   559.7  774.11   569.3  772.59     579   772.5
   627.3   772.5   636.9  774.05   646.6  777.07   656.2  778.63   714.2  778.76
     743  782.63   771.9  785.42   781.5  787.11   839.3  805.06   848.9  808.82
   858.5   814.4   877.8  827.72   887.4  833.16     897  837.25   935.5  850.17
#Mann= 3 , 0 , 0
       0      .1       0     579    .045       0   636.9     .07       0
Bank Sta=579,636.9
XS Rating Curve= 0 ,0
Exp/Cntr=0.3,0.1

Type RM Length L Ch R = 1 ,98308.8 ,1031,1036.9,1042.1
XS GIS Cut Line= 4
     1564957.273      279422.701     1565391.904      279996.844
     1565515.371      280180.144     1565730.446      280499.448
#Sta/Elev= 30
       0  900.97    58.4  900.89    87.6  899.83     107  898.41   204.4  886.77
   233.6  884.11   282.2   880.9     399  866.14   476.8  852.06   515.8  843.16
   603.3  821.89   671.4  806.72   690.9  800.82   710.4  793.52   748.9  780.32
   758.5  777.94   825.8  772.32   864.2  771.31   883.4  771.95   921.9   776.8
     970  778.49   979.6  779.99   989.2  782.25  1018.1  789.73  1037.4  795.96
  1152.8  840.99  1181.7  851.35    1201  857.55  1220.2  862.07  1326.1   879.5
#Mann= 3 , 0 , 0
       0      .1       0   825.8    .045       0   883.4    .055       0
Bank Sta=825.8,883.4
XS Rating Curve= 0 ,0
Exp/Cntr=0.3,0.1