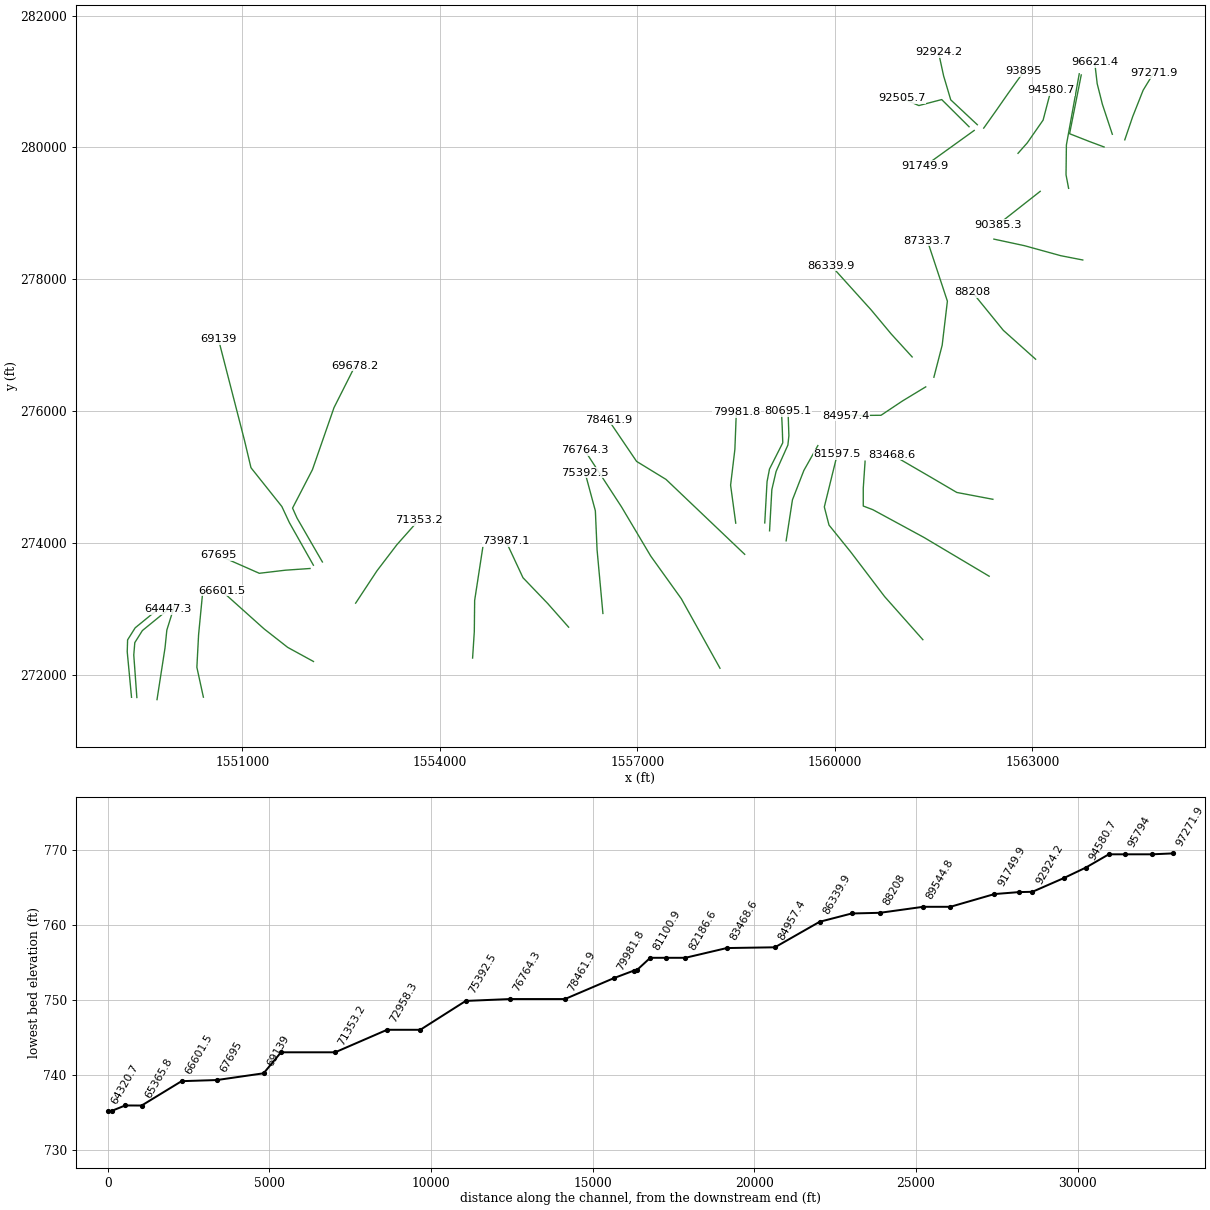
HEC-RAS study NFHGHSRV1.prj: NFHGHSRV1

--- NFHGHSRV1.g01 (geometry) --- (continued)

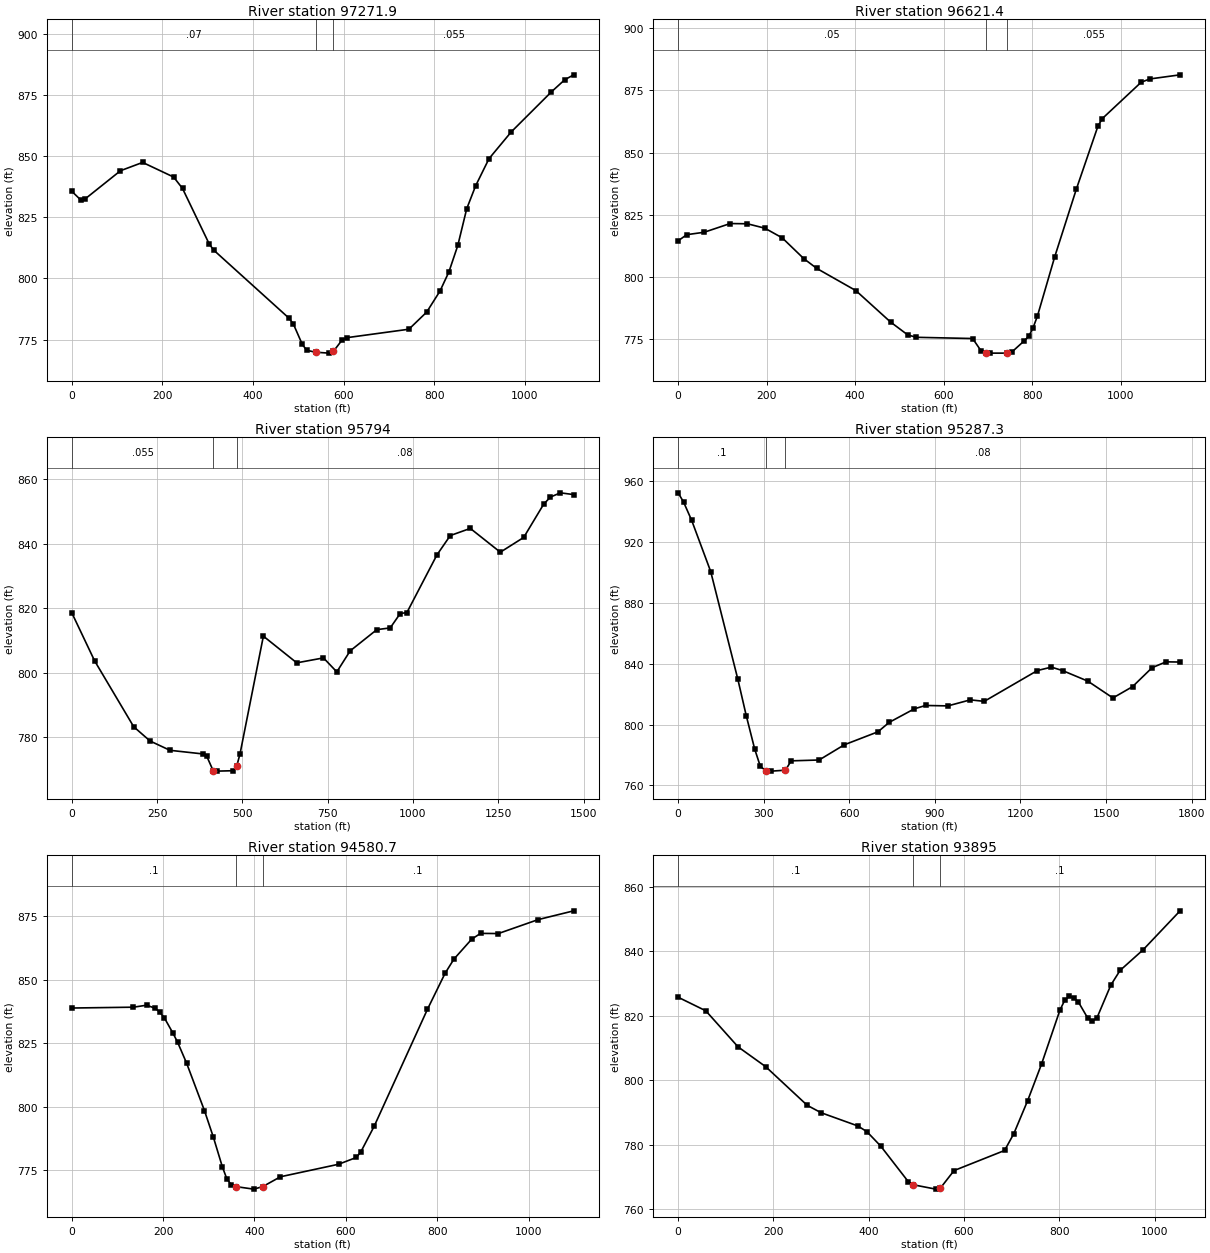
Type RM Length L Ch R = 1 ,97271.9 ,636.4,650.5,664.8
XS GIS Cut Line= 4
     1564403.189        280114.9     1564522.981      280466.462
     1564681.835      280867.504     1564840.689      281127.921
#Sta/Elev= 30
       0   835.6    19.6  832.09    29.3  832.44   107.5  843.98   156.4  847.37
   224.8   841.4   244.4  836.75     303  814.21   312.8  811.65   479.2  783.82
     489  781.43   508.7  773.11   518.5  770.69   538.1  769.89   567.5  769.52
   577.3  770.22   596.9  774.94   606.7  775.82     744  779.28   783.2  786.25
   812.6  794.84   832.3  802.67     852   813.5   871.6  828.44   891.3  837.82
   920.8   848.9     970  859.85  1058.6  876.19  1088.1  881.14  1107.8  883.13
#Mann= 3 , 0 , 0
       0     .07       0   538.1    .045       0   577.3    .055       0
Bank Sta=538.1,577.3
XS Rating Curve= 0 ,0
Exp/Cntr=0.3,0.1

Type RM Length L Ch R = 1 ,96621.4 ,805.2,827.4,848.8
XS GIS Cut Line= 4
     1564213.953      280199.101     1564062.911       280654.83
     1563984.038      280967.261     1563945.843      281297.122
#Sta/Elev= 30
       0  814.55    19.6  817.03    58.8  817.99   117.6   821.5   156.8   821.4
     196  819.63   235.2  815.76   284.1  807.38   313.5  803.44   401.7  794.54
   480.1   781.9   519.2  776.69   538.7  775.76   665.6  775.27   685.2  770.17
   694.9  769.44   704.7   769.4   743.8   769.4   753.5  769.73   782.8  774.44
   792.6   776.2   802.3  779.66   812.1  784.34   851.2  808.19     900  835.35
   948.8  860.67   958.6  863.69  1046.5  878.31    1066  879.63  1134.4  881.29
#Mann= 3 , 0 , 0
       0     .05       0   694.9    .045       0   743.8    .055       0
Bank Sta=694.9,743.8
XS Rating Curve= 0 ,0
Exp/Cntr=0.3,0.1

Type RM Length L Ch R = 1 ,95794   ,534.1,506.7,479.3
XS GIS Cut Line= 4
     1564088.953      280006.393     1563864.994      280089.726
     1563564.767      280207.713     1563741.995      281099.784
#Sta/Elev= 30
       0  818.55    66.9  803.63   181.6  783.16   229.4  778.75   287.8  775.86
   385.6  774.72   395.4  774.06   414.9  769.41   424.7   769.4   473.6  769.53
   483.3  770.91   493.1  774.78   561.5  811.28   659.3     803   737.6  804.53
   776.7  800.19   815.8  806.71     894   813.3   933.2  813.84   962.5  818.29
   982.1   818.6  1070.1  836.48  1109.2  842.49  1167.9  844.71  1255.9  837.33
  1324.4  841.91    1383  852.24  1402.6  854.43  1431.9  855.75    1471   855.2
#Mann= 3 , 0 , 0
       0    .055       0   414.9    .045       0   483.3     .08       0
Bank Sta=414.9,483.3
XS Rating Curve= 0 ,0
Exp/Cntr=0.3,0.1

Type RM Length L Ch R = 1 ,95287.3 ,719.8,706.5,693.3
XS GIS Cut Line= 4
      1563549.89      279378.789     1563510.828      279584.518
       1563516.3      280036.416     1563711.613      281117.145
#Sta/Elev= 30
       0  952.47      19  946.46    47.6  934.32   114.2  900.71   209.4  829.83
   238.9  805.84   268.4  783.94     288  772.64   307.6  769.57   327.3   769.4
   376.4  770.02   396.1  776.16   494.3  776.72   582.7  786.73   700.6  795.27
   739.8  801.46     828  810.37   867.3  812.59   945.7  812.31  1024.2  816.28
  1073.2   815.3  1259.5  835.58  1308.5  837.81  1347.7  835.54    1436  828.62
  1524.2  817.54  1592.9  824.96  1661.5  837.45  1710.5  841.29  1759.6  841.16
#Mann= 3 , 0 , 0
       0      .1       0   307.6    .045       0   376.4     .08       0
Bank Sta=307.6,376.4
XS Rating Curve= 0 ,0
Exp/Cntr=0.3,0.1

Type RM Length L Ch R = 1 ,94580.7 ,686,685.7,685.2
XS GIS Cut Line= 4
     1562781.661      279910.039     1562922.286      280068.893
     1563162.643      280414.195     1563280.913      280864.831
#Sta/Elev= 30
       0  838.87     135   839.2   163.9  839.98   183.2  838.74   192.9  837.16
   202.5  835.06   221.9  828.86   231.7  825.41   251.3  817.22   290.4  798.55
     310  788.06   329.6  776.44   339.4   771.7   349.1  769.36   358.9  768.64
   398.1  767.64   417.6  768.59   456.8   772.5     584  777.42   623.1  780.11
   632.9  782.34     662  792.38   778.5  838.34   817.3  852.57   836.7  858.15
   875.5  865.96   894.9  868.23   933.8  868.16  1021.1  873.66  1098.8   877.1
#Mann= 3 , 0 , 0
       0      .1       0   358.9    .045       0   417.6      .1       0
Bank Sta=358.9,417.6
XS Rating Curve= 0 ,0
Exp/Cntr=0.3,0.1

Type RM Length L Ch R = 1 ,93895   ,950.4,970.9,991
XS GIS Cut Line= 4
     1562260.828      280292.851     1562445.724      280553.268
     1562638.432      280829.309     1562870.203      281152.226
#Sta/Elev= 30
       0  825.74    58.1  821.53   125.8  810.35   183.9  804.19     271  792.21
     300  789.93   377.1  785.83   396.3  784.04   425.2  779.58   482.9  768.58
   492.5  767.61   540.6  766.23   550.2   766.5   579.1  771.98   685.1  778.21
   704.5  783.41   733.6  793.67   762.7  804.99   801.4  821.76   811.2  824.74
   820.8  825.99   830.5  825.63   840.2  824.22   859.6  819.29   869.3  818.32
     879  819.32   908.1  829.48   927.5  834.04     976  840.46  1053.5  852.53
#Mann= 3 , 0 , 0
       0      .1       0   492.5    .045       0   550.2      .1       0
Bank Sta=492.5,550.2
XS Rating Curve= 0 ,0
Exp/Cntr=0.3,0.1

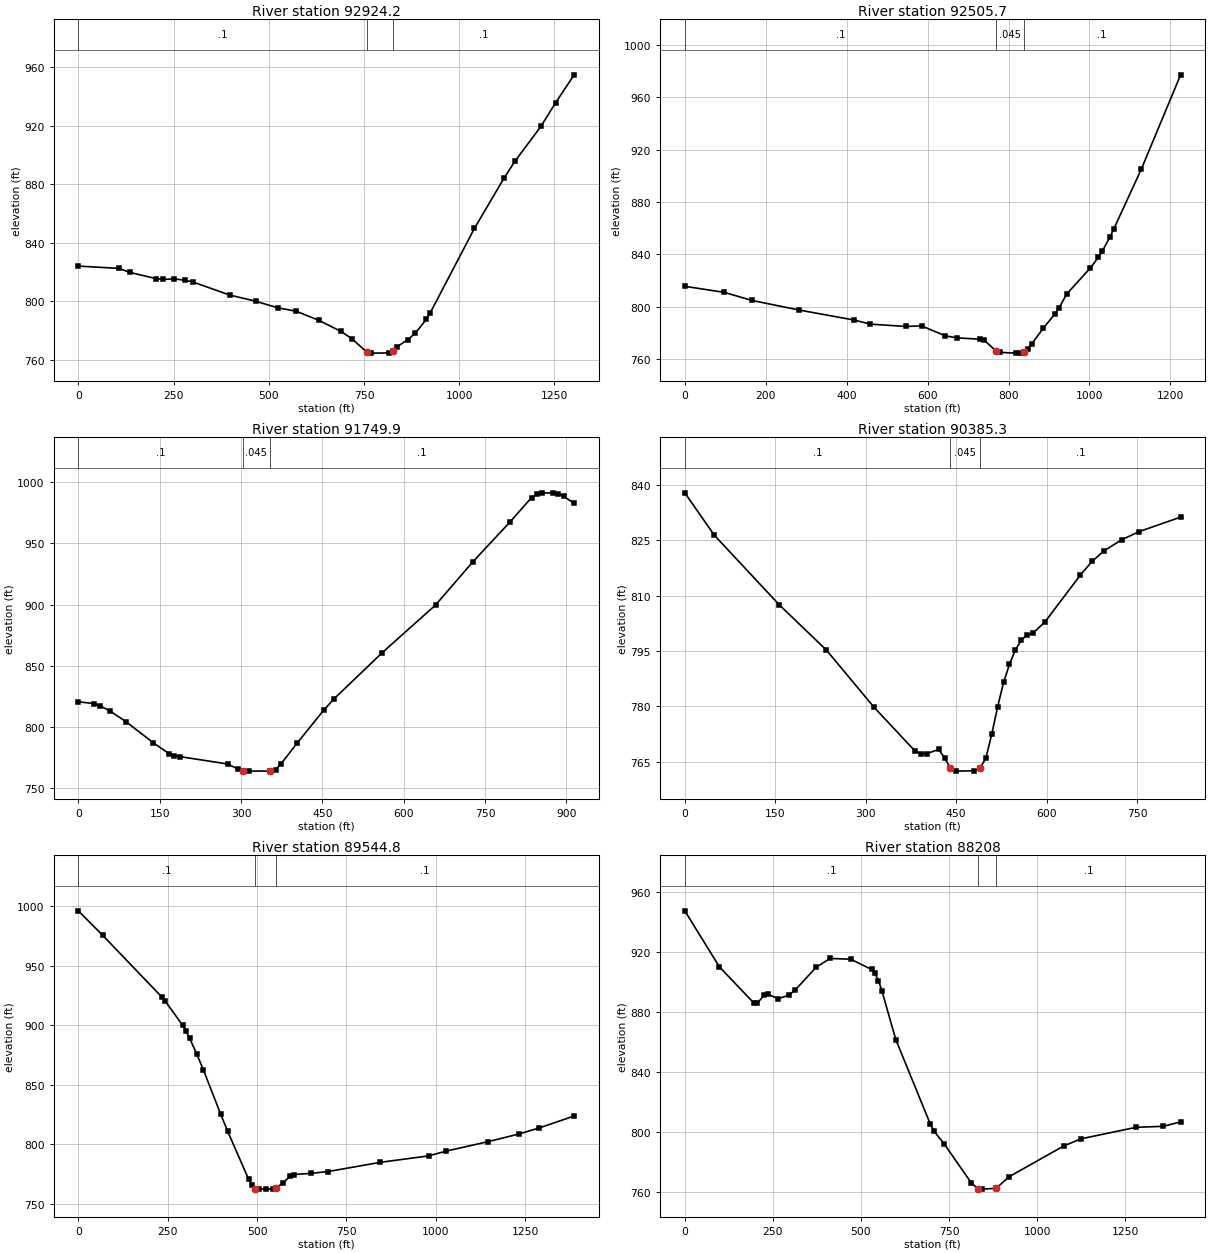
Type RM Length L Ch R = 1 ,92924.2 ,382.5,418.4,452.9
XS GIS Cut Line= 4
     1562163.606      280344.066      1561759.96      280721.671
     1561651.453      281086.254     1561573.328      281446.497
#Sta/Elev= 30
       0  823.95   106.7  822.37   135.8  819.59   203.6   815.4     223  814.81
   252.1  815.22   281.2   814.2   300.6  813.08   397.6  804.12   465.5  799.92
   523.6  795.41   572.2  793.03   630.8  786.92   689.3  779.28   718.5  774.19
   757.6  764.99   767.3   764.4   816.1  764.54   825.8  766.01   835.6  768.56
   864.8  773.56   884.4  778.04   913.6  787.43   923.4  791.74  1039.8  849.71
  1117.4  884.05  1146.5  895.79  1214.4  919.49  1253.2   935.8  1301.7   954.8
#Mann= 3 , 0 , 0
       0      .1       0   757.6    .045       0   825.8      .1       0
Bank Sta=757.6,825.8
XS Rating Curve= 0 ,0
Exp/Cntr=0.3,0.1

Type RM Length L Ch R = 1 ,92505.7 ,748,755.8,764
XS GIS Cut Line= 4
     1562037.738      280313.684     1561622.537      280725.971
     1561275.315      280634.825     1561017.772      280747.712
#Sta/Elev= 30
       0  815.46    97.5  810.82   165.8  804.66   282.8   797.3   419.3  789.61
   458.4  786.54   546.1  784.74   585.1   785.2   643.3  777.62   672.4  776.05
   730.7  774.97   740.4  774.06   769.5   765.9   779.2  764.94     818  764.36
   827.7  764.51   837.4  765.47   847.1  767.67   856.8  771.22   885.9  783.41
     915  794.47   924.7   798.9   944.1  809.69  1002.3  829.52  1021.7   837.5
  1031.4  842.13  1050.8  853.29  1060.5  859.56  1128.3  905.13  1225.3  977.17
#Mann= 3 , 0 , 0
       0      .1       0   769.5    .045       0   837.4      .1       0
Bank Sta=769.5,837.4
XS Rating Curve= 0 ,0
Exp/Cntr=0.3,0.1

Type RM Length L Ch R = 1 ,91749.9 ,1363.7,1364.6,1365.5
XS GIS Cut Line= 2
     1562115.863      280257.261     1561373.675      279723.407
#Sta/Elev= 30
       0  820.67    29.5  819.19    39.3  817.58      59  812.96    88.5  804.22
   137.6  787.42   167.1  778.39     177   776.8   186.8  775.98   275.3  769.93
   294.9  765.67  302.75764.5281   314.6   764.1   353.9  764.17   363.7   765.4
   373.6  769.96     403  786.73   452.2   813.7   471.9  823.27   560.3  860.72
   658.6  899.59   727.5   934.9   796.3  967.53   835.6  987.24   845.4  990.07
   855.3  990.95   874.9  991.13   884.8  990.49   894.6  988.38   914.2  982.56
#Mann= 3 , 0 , 0
       0      .1       0  302.75    .045       0   353.9      .1       0
Bank Sta=302.75,353.9
XS Rating Curve= 0 ,0
Exp/Cntr=0.3,0.1

Type RM Length L Ch R = 1 ,90385.3 ,861.6,840.5,819.3
XS GIS Cut Line= 2
     1563118.467      279332.782     1562471.765      278824.969
#Sta/Elev= 30
       0  837.89    48.9   826.4   156.6  807.52   234.9  795.23   313.2  779.83
   381.8  767.84   391.6  767.14   401.3  767.16   420.9  768.27   430.7  766.05
   440.5  763.18   450.3   762.4   479.6  762.49   489.4  763.19   499.2  765.89
     509  772.43   518.8  779.88   528.6  786.45   538.4  791.39   548.2  795.29
     558  797.93   567.7  799.38   577.5  799.87   597.1  802.84   655.8  815.55
   675.4  819.29     695  822.13   724.4  825.15   753.7  827.39   822.2   831.3
#Mann= 3 , 0 , 0
       0      .1       0   440.5    .045       0   489.4      .1       0
Bank Sta=440.5,489.4
XS Rating Curve= 0 ,0
Exp/Cntr=0.3,0.1

Type RM Length L Ch R = 1 ,89544.8 ,1349.4,1336.9,1320.9
XS GIS Cut Line= 4
     1563765.168      278291.115     1563430.967      278356.219
     1562879.751      278508.129     1562415.342      278607.955
#Sta/Elev= 30
       0  996.25    68.1  975.68   233.5  923.86   243.2  920.37   291.8  900.05
   301.6     895   311.3  889.16   330.8  876.34   350.2  862.35   398.6  825.18
     418  810.83   476.2   770.9   485.8  765.46   495.5  762.89   505.2  762.43
   524.6   762.4     544  762.54   553.7  763.44   573.1  767.83   592.4  773.14
   602.1  774.67   650.6  775.63     699  777.18   844.4  784.89   980.1  790.34
  1028.6   794.3  1144.9  802.19  1232.2  808.68  1290.3  813.86  1387.3  823.87
#Mann= 3 , 0 , 0
       0      .1       0   495.5    .045       0   553.7      .1       0
Bank Sta=495.5,553.7
XS Rating Curve= 0 ,0
Exp/Cntr=0.3,0.1

Type RM Length L Ch R = 1 ,88208   ,892.2,874.3,856.8
XS GIS Cut Line= 3
     1563049.022      276785.039     1562558.571      277223.407
     1562085.481      277805.004
#Sta/Elev= 30
       0  947.71    98.2  910.25   196.4  885.98   206.2  886.14   225.8  891.26
   235.6  891.95   265.1  888.98   294.5  891.18   314.2  894.97   373.1  910.05
   412.4  915.86   471.3  915.33   530.2  908.51     540  905.83   549.8  900.92
   559.6  894.16   598.9  861.65   696.8   805.2   706.5  800.61   735.7  792.04
   813.6   765.7  832.23761.7803   842.8   761.6   883.7762.1403   920.7  769.91
  1076.5  790.57  1125.2  795.27  1280.9  802.93  1358.8  803.61  1407.5  806.59
#Mann= 3 , 0 , 0
       0      .1       0  832.23    .045       0   883.7      .1       0
Bank Sta=832.23,883.7
XS Rating Curve= 0 ,0
Exp/Cntr=0.3,0.1

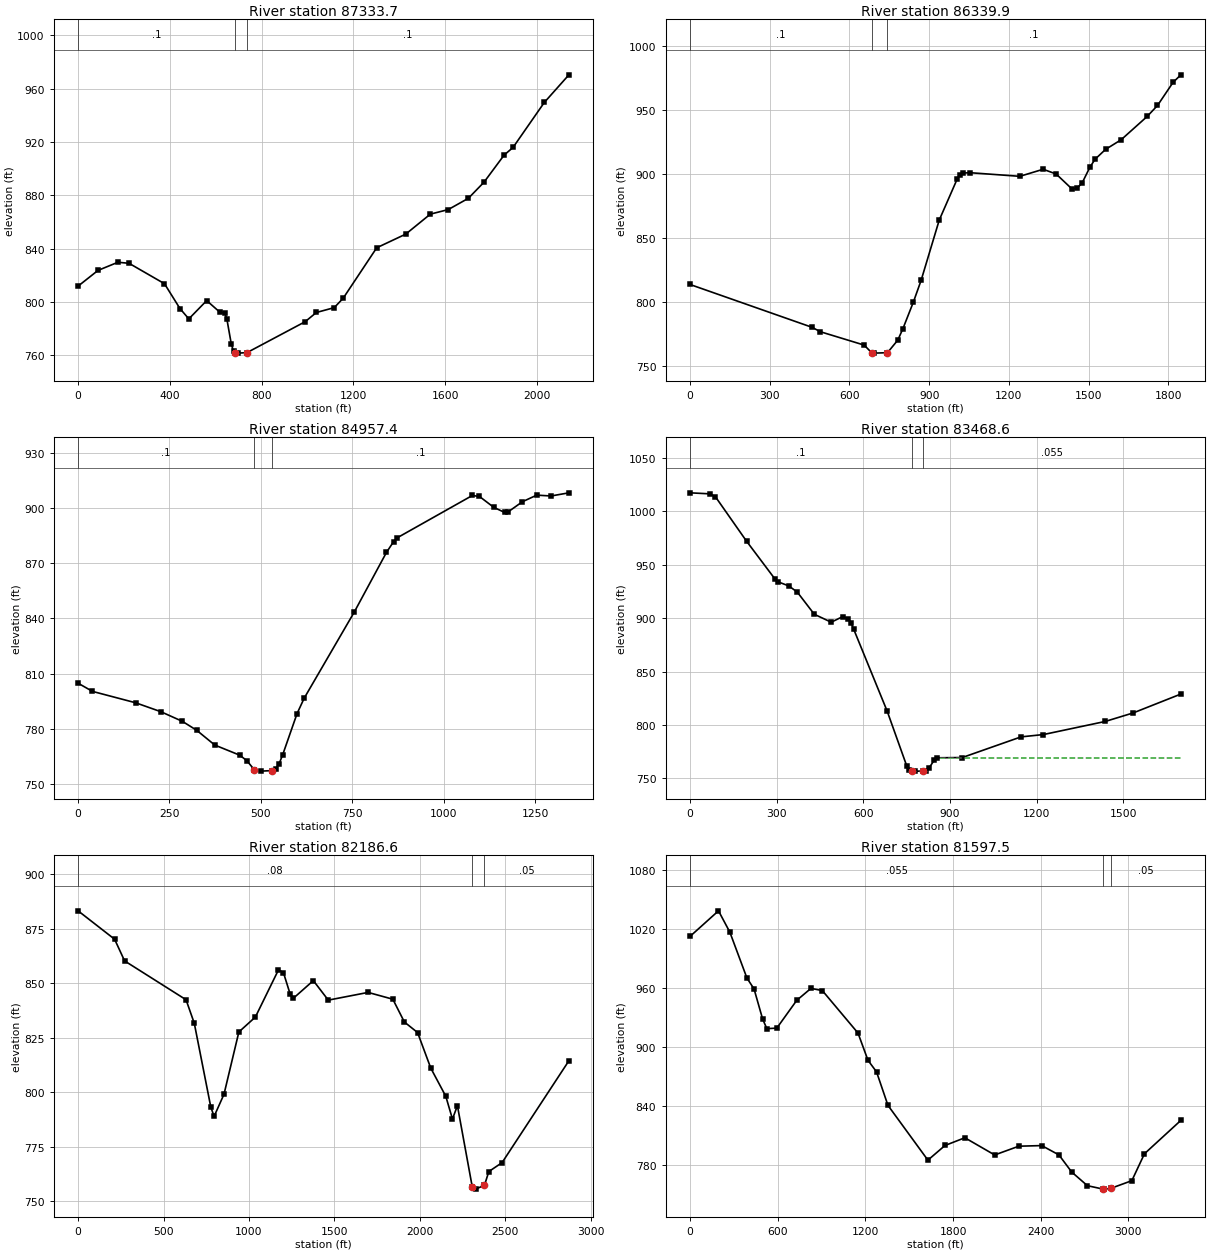
Type RM Length L Ch R = 1 ,87333.7 ,975,993.8,1011.5
XS GIS Cut Line= 4
     1561503.883      276511.601     1561629.751      276997.712
     1561708.997      277666.133     1561405.913      278581.845
#Sta/Elev= 30
       0  811.79    86.9  823.61   173.8  829.72   222.1  828.94   376.6  813.62
   444.2  794.95   482.8  787.21   560.7  800.95   619.2  792.06   638.7  791.94
   648.5  787.26     668  768.26   677.7  762.85  685.76761.7972   697.2  761.51
   736.3  761.88   989.9   785.1  1038.7  792.01  1116.7  795.65  1155.7  802.71
  1301.9  840.59  1428.6  850.85  1535.7  865.84  1613.7  869.26  1701.4  877.72
  1769.6  889.81  1857.3  910.16  1896.2  915.89  2032.6  949.69  2139.8  970.41
#Mann= 3 , 0 , 0
       0      .1       0  685.76    .045       0   736.3      .1       0
Bank Sta=685.76,736.3
XS Rating Curve= 0 ,0
Exp/Cntr=0.3,0.1

Type RM Length L Ch R = 1 ,86339.9 ,1349.2,1382.5,1415.6
XS GIS Cut Line= 4
     1561174.022      276819.761     1560856.868      277166.914
     1560550.878      277533.667     1559947.579      278201.347
#Sta/Elev= 30
       0     814   460.4  780.48   489.7  777.16   655.4  766.68  683.39 760.782
     694   760.4   743.2  760.75   782.1  770.57   801.6  779.63   840.6  800.21
   869.9  817.25   938.1  864.31  1006.5  896.76  1016.3  899.71  1026.1  901.03
  1055.4  901.27  1241.3  898.46  1329.3  903.97  1378.2  900.27  1436.9  888.77
  1456.5  889.07    1476  893.29  1505.4  905.66  1524.9  911.85  1564.1  919.48
  1622.8  927.01  1720.6  945.18  1759.7  953.77  1818.4  971.86  1847.7  977.72
#Mann= 3 , 0 , 0
       0      .1       0  683.39    .045       0   743.2      .1       0
Bank Sta=683.39,743.2
XS Rating Curve= 0 ,0
Exp/Cntr=0.3,0.1

Type RM Length L Ch R = 1 ,84957.4 ,1514.1,1488.8,1463.4
XS GIS Cut Line= 4
     1561379.871      276365.409     1561026.453      276151.358
     1560700.932      275934.344     1560162.738      275930.004
#Sta/Elev= 30
       0  804.76    39.4  800.31   157.4  794.13   226.3  789.29   285.3  784.04
   324.6  779.16   373.8  771.17   442.5  765.64   462.1  762.58   481.6  757.84
   500.6     757   530.6  757.29   540.3  758.17   550.1  761.12   559.9  766.01
     599  788.27   618.6  796.66   755.5  843.42   843.6  875.83   863.1  881.67
   872.9  883.74  1078.4  906.72    1098  906.18  1137.1  900.28  1166.5  897.54
  1176.3  897.81  1215.4  903.33  1254.6  906.91  1293.7  906.46  1342.6  908.17
#Mann= 3 , 0 , 0
       0      .1       0   481.6    .045       0   530.6      .1       0
Bank Sta=481.6,530.6
XS Rating Curve= 0 ,0
Exp/Cntr=0.3,0.1

Type RM Length L Ch R = 1 ,83468.6 ,1305.4,1282,1258.3
XS GIS Cut Line= 4
     1562399.836      274659.246     1561852.093      274762.979
     1561461.468      274992.145     1560865.114        275338.5
#Sta/Elev= 30
       0 1017.42    68.5 1016.47      88 1013.71   195.6  972.18   293.4     937
   303.2  934.27   342.3  930.24   371.6  924.43   430.3  903.74     489   896.3
   528.1  901.46   547.7  899.72   557.5  895.71   567.1  889.55   682.8  813.01
   750.2  762.01   759.8  757.86  768.63757.0043   778.1   756.9     808   756.9
   817.6  757.29   827.3  759.61   846.6  767.57   856.2  769.38   942.9  769.62
  1146.4  788.96    1224  791.14  1437.8  803.39  1534.9  811.39    1700  829.06
#Mann= 3 , 0 , 0
       0      .1       0  768.63    .045       0     808    .055       0
#XS Ineff= 2 , 0
                          865.74          769.46
Permanent Ineff=
       F       F
Bank Sta=768.63,808
XS Rating Curve= 0 ,0
Exp/Cntr=0.3,0.1

Type RM Length L Ch R = 1 ,82186.6 ,592.5,589.1,583.6
XS GIS Cut Line= 6
     1562343.413      273491.711     1561351.974      274081.046
     1560577.137      274501.303     1560431.303      274556.859
     1560431.303      274827.692     1560459.081      275237.415
#Sta/Elev= 30
       0  883.21   213.8  870.18   272.2  860.25   631.8  842.44   680.1  831.64
   776.7  793.24     796  788.94     854  799.12   940.9  827.66  1037.6   834.5
  1172.9  856.17    1202  854.82  1240.9  845.08  1260.3  843.14  1376.8  851.21
  1464.2  842.26  1697.3   845.8  1842.1  842.68  1909.6  832.23  1986.8   827.4
  2064.2  811.07    2152  798.17    2191  787.72    2220  793.88  2307.1  756.52
  2326.4   755.6 2378.35757.3755  2403.8  763.65  2481.4  767.76  2872.5  814.47
#Mann= 3 , 0 , 0
       0     .08       0  2307.1    .045       0 2378.35     .05       0
Bank Sta=2307.1,2378.35
XS Rating Curve= 0 ,0
Exp/Cntr=0.3,0.1

Type RM Length L Ch R = 1 ,81597.5 ,500.3,496.6,493.4
XS GIS Cut Line= 6
     1561336.468       272528.17     1560754.781      273183.483
     1560240.863      273859.691     1559911.001      274267.678
     1559839.868       274542.97     1560036.869      275344.066
#Sta/Elev= 30
       0 1012.89   194.7 1038.91   272.6 1017.14   389.4  970.47   438.1  959.37
   496.5  928.88   525.7  918.95   593.9  919.51   730.2  947.77   827.6  959.96
   905.5  957.71  1149.6  914.49  1217.9  886.76  1276.5  874.97  1354.6  840.88
    1628   785.1    1745  800.02    1881   807.9  2085.1  790.38  2250.2   799.3
  2407.1  799.92  2524.8  790.46  2612.6  772.97  2719.9   759.1  2826.8  755.65
  2836.2   755.6 2878.23 756.287    3024   764.2  3110.3   791.6  3359.6   825.6
#Mann= 3 , 0 , 0
       0    .055       0  2826.8    .045       0 2878.23     .05       0
Bank Sta=2826.8,2878.23
XS Rating Curve= 0 ,0
Exp/Cntr=0.3,0.1

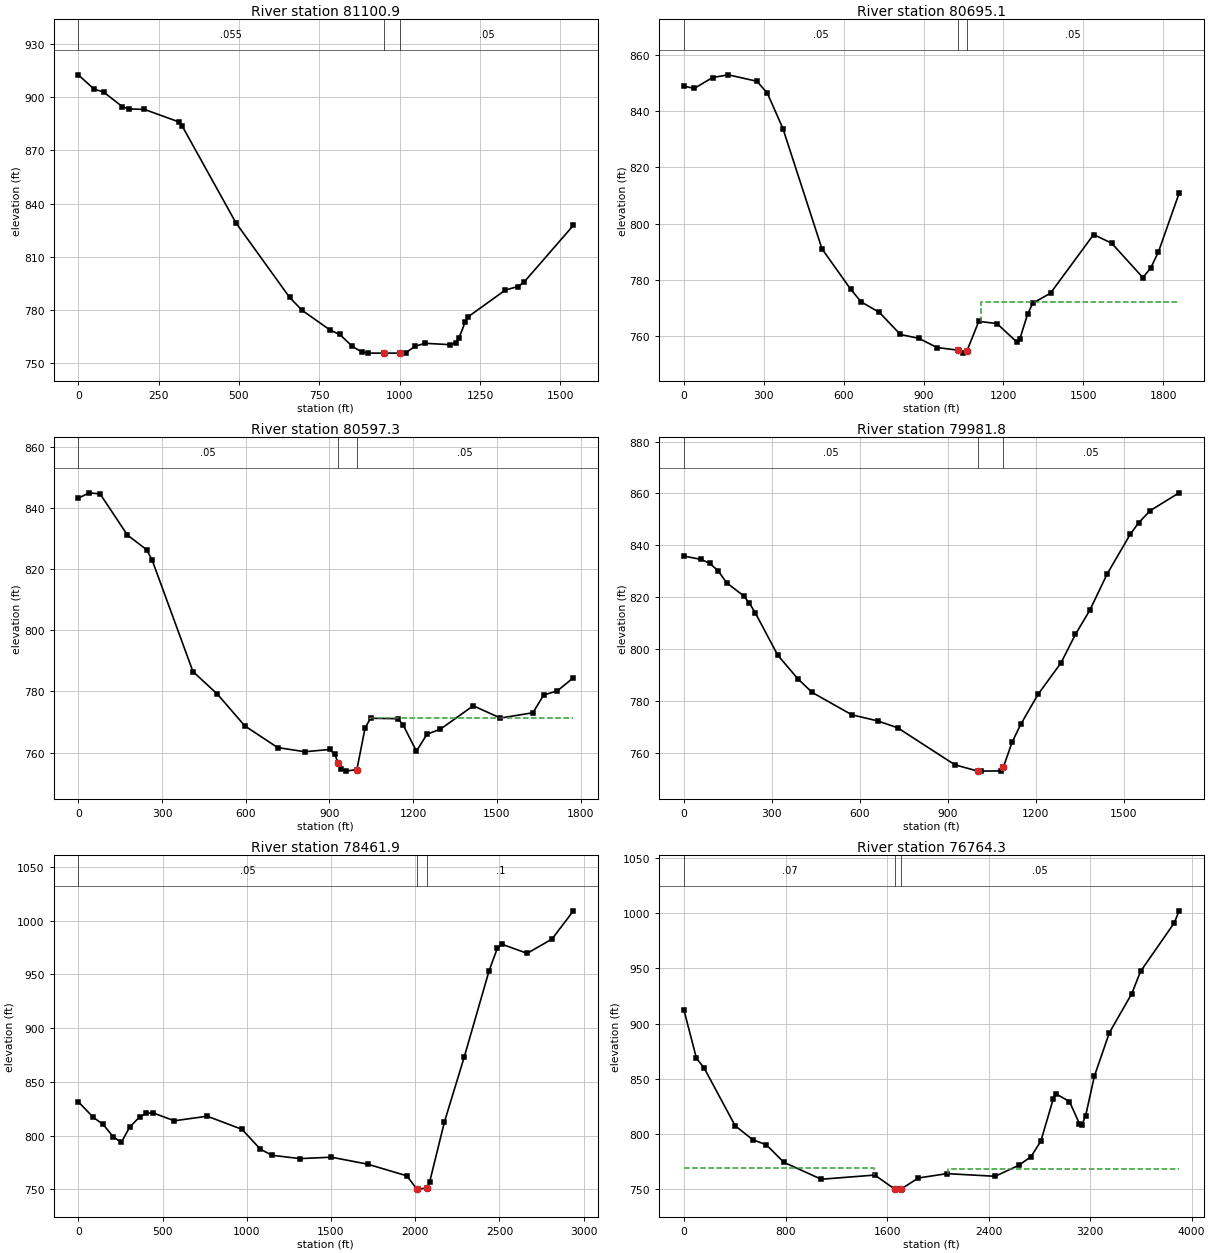
Type RM Length L Ch R = 1 ,81100.9 ,405.9,405.8,404.7
XS GIS Cut Line= 4
      1559259.96      274028.962     1559355.446      274649.622
     1559529.057      275096.671     1559741.731      275474.275
#Sta/Elev= 30
       0  912.68    49.1  904.59    78.5  902.98   137.4  894.68     157  893.42
     206  893.16     314  886.03   323.8  883.62   490.6  829.12   657.3  787.13
   696.5  779.75   784.6   768.5   813.9  766.13   853.1  759.37   882.4  756.26
     902   755.6   950.9   755.6   999.9   755.6  1019.4  755.92  1048.8  759.47
  1078.2  761.16  1155.7  760.38    1175  761.32  1184.6  764.09  1203.8  773.06
  1213.5  776.15    1329   791.2  1367.6  793.17  1386.8  795.59  1540.9  827.75
#Mann= 3 , 0 , 0
       0    .055       0   950.9    .045       0   999.9     .05       0
Bank Sta=950.9,999.9
XS Rating Curve= 0 ,0
Exp/Cntr=0.3,0.1

Type RM Length L Ch R = 1 ,80695.1 ,99.5,97.8,96.2
XS GIS Cut Line= 6
     1559008.224      274180.872     1559042.946      274805.872
      1559108.05       275083.65     1559286.743      275482.901
     1559301.732       275623.53     1559289.347      275993.317
#Sta/Elev= 30
       0  848.82    39.1   848.1   107.6  851.95   166.3   852.9   273.9  850.61
     313   846.4   371.7  833.78   518.4  791.05     626  776.72   665.3  772.22
   734.2  768.45   812.9  760.62   881.8  759.26   950.5  755.99    1029  755.04
  1048.6  753.99 1062.09754.5782  1107.5  765.28  1175.5   764.5  1252.5  757.78
  1262.2  759.17  1291.1  767.89  1310.3  771.71  1377.1  775.32    1539  796.14
  1607.1  793.03    1724  780.84  1753.2  784.19  1782.4  789.94  1860.3  810.84
#Mann= 3 , 0 , 0
       0     .05       0    1029    .045       0 1062.09     .05       0
#XS Ineff= 2 , 0
                         1116.03          772.31
Permanent Ineff=
       F       F
Bank Sta=1029,1062.09
XS Rating Curve= 0 ,0
Exp/Cntr=0.3,0.1

Type RM Length L Ch R = 1 ,80597.3 ,607.6,615.5,623.3
XS GIS Cut Line= 6
     1558935.307      274300.664     1558970.029      274925.664
     1559007.139      275118.155     1559208.684      275516.721
     1559200.692      275751.037     1559187.785      276021.963
#Sta/Elev= 30
       0  843.29    39.1  845.05    78.2  844.68     176  831.23   244.5  826.44
   264.1  823.15   410.8  786.52   498.8  779.08   596.6  768.73   714.2  761.62
   812.2  760.25   900.4  760.99     920  759.38   929.8  756.68   939.6  754.55
   959.2   753.9   998.3  754.43  1027.7  768.05  1047.3  771.22    1145  771.07
    1164  769.03  1211.6  760.44  1249.6  765.98  1297.9  767.66  1415.2   775.3
  1512.8  771.28    1629  773.02  1667.8  778.84  1716.2  780.15  1774.3  784.51
#Mann= 3 , 0 , 0
       0     .05       0   929.8    .045       0   998.3     .05       0
#XS Ineff= 2 , 0
                         1045.42          771.26
Permanent Ineff=
       F       F
Bank Sta=929.8,998.3
XS Rating Curve= 0 ,0
Exp/Cntr=0.3,0.1

Type RM Length L Ch R = 1 ,79981.8 ,1493.4,1519.9,1545.2
XS GIS Cut Line= 4
     1558494.552      274296.974     1558416.427      274874.231
     1558481.531      275416.766     1558503.232      275976.662
#Sta/Elev= 30
       0  835.83    58.2  834.54    87.4  833.06   116.5  830.15   145.6  825.51
   203.9  820.47   223.3  817.63   242.7  814.02   320.4  797.51   388.4  788.52
   436.9  783.27   572.8  774.61   660.6  772.27   728.9  769.61     924  755.35
  1002.1  752.91  1011.9   752.9  1080.2  752.99  1089.9  754.55  1119.2  763.99
  1148.6  770.89  1207.6  782.46  1286.2  794.65  1335.4  805.63  1384.5  814.94
  1443.5   828.9  1522.2  844.18  1551.6  848.75    1591  853.38  1689.3  860.22
#Mann= 3 , 0 , 0
       0     .05       0  1002.1    .045       0  1089.9     .05       0
Bank Sta=1002.1,1089.9
XS Rating Curve= 0 ,0
Exp/Cntr=0.3,0.1

Type RM Length L Ch R = 1 ,78461.9 ,1706.3,1697.6,1688
XS GIS Cut Line= 4
     1558630.493      273824.047     1557435.524      274961.037
     1556988.475      275234.474     1556558.788      275868.155
#Sta/Elev= 30
       0  831.45    88.4  816.96   147.3  810.37   206.2  799.03   255.3  793.54
   304.4   807.7   363.3  817.14   402.6  820.51   441.8  821.19   569.4  813.71
   765.8  817.97     972  805.72    1080  787.39  1148.7  781.64  1315.6  778.51
  1502.2  779.83  1717.4  773.34  1950.3  762.47  2008.5  750.32  2018.2   750.1
 2070.61751.1834  2086.2  757.17  2173.5  812.72  2291.3  873.28  2438.5  953.41
  2487.6  974.38    2517  977.92  2664.3  969.57  2811.5  982.83  2939.1 1009.15
#Mann= 3 , 0 , 0
       0     .05       0  2008.5    .045       0 2070.61      .1       0
Bank Sta=2008.5,2070.61
XS Rating Curve= 0 ,0
Exp/Cntr=0.3,0.1

Type RM Length L Ch R = 1 ,76764.3 ,1383.8,1371.8,1357
XS GIS Cut Line= 5
     1558255.493       272094.88     1557667.295      273151.141
     1557203.753      273796.974     1556761.045      274541.766
     1556198.545      275406.349
#Sta/Elev= 30
       0  911.95    98.3  868.38   157.3  860.03     403  807.47   540.6   794.9
   648.7  790.24   786.3  774.42  1081.2  759.05  1503.4  762.82  1660.5  750.14
  1670.3   750.1  1709.5   750.1  1846.9  760.19  2072.1  764.12  2451.8  761.73
  2636.8  771.57  2734.1  779.39    2812  793.54  2909.7  831.75  2929.3  836.44
  3037.4  829.41    3116  809.36  3135.6  808.33  3165.1  816.67  3233.9  852.39
  3351.7   891.6  3528.6  927.09  3597.3  947.14  3862.6     991  3901.8 1002.02
#Mann= 3 , 0 , 0
       0     .07       0  1660.5    .045       0  1709.5     .05       0
#XS Ineff= 2 , 0
         1498.33  769.52 2083.26           767.9
Permanent Ineff=
       F       F
Bank Sta=1660.5,1709.5
XS Rating Curve= 0 ,0
Exp/Cntr=0.3,0.1

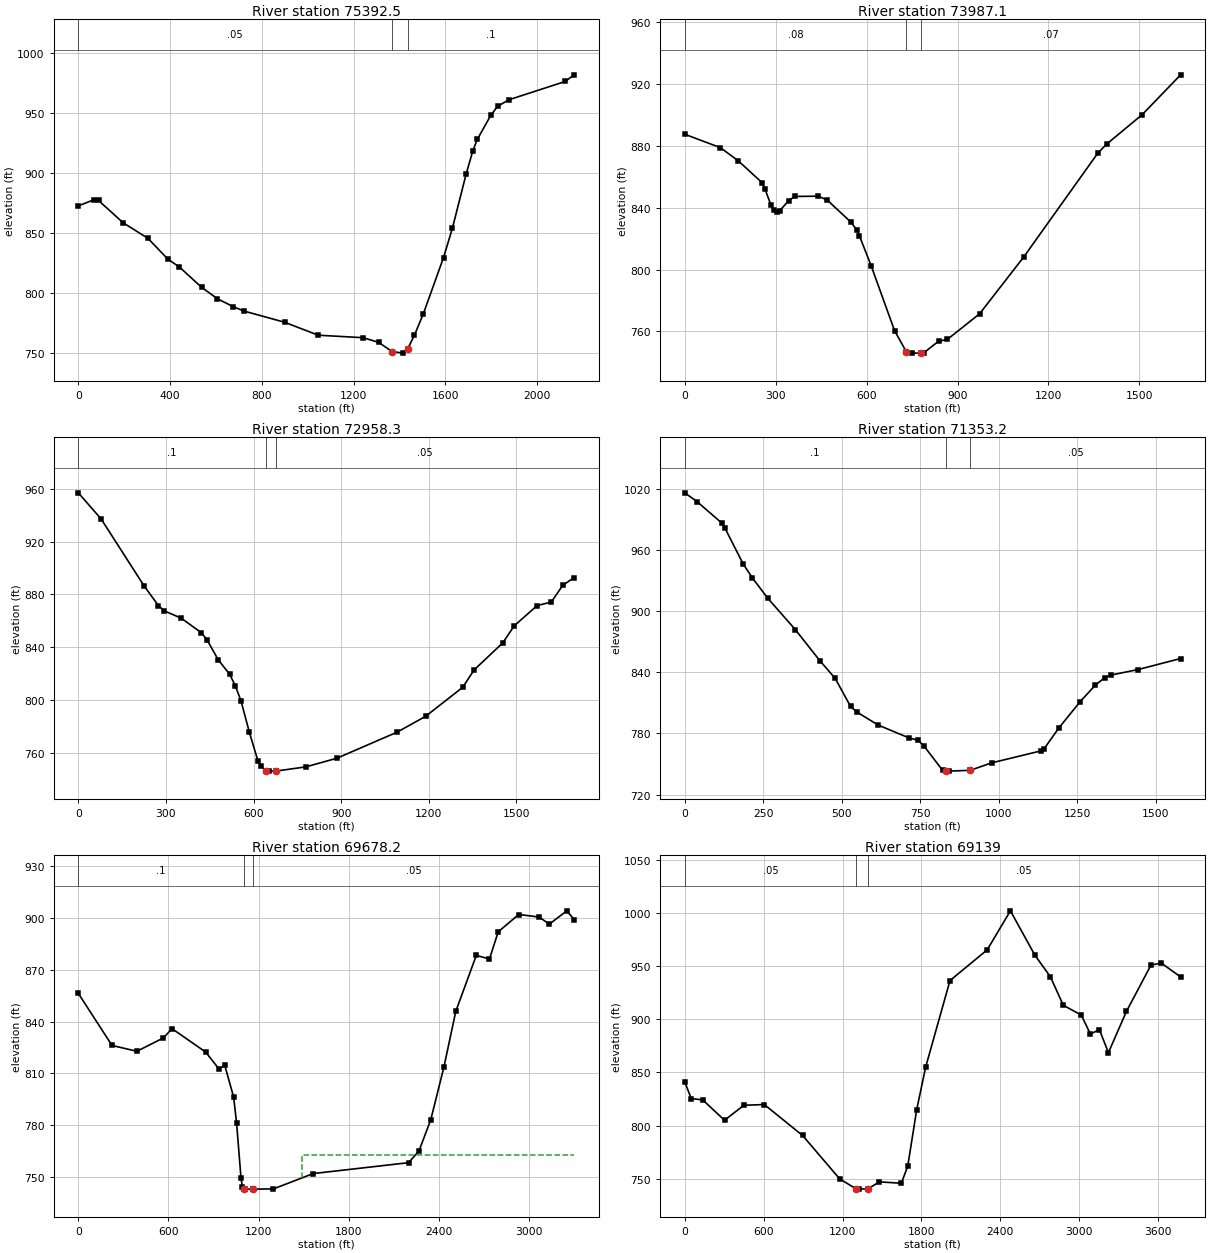
Type RM Length L Ch R = 1 ,75392.5 ,1388.6,1405.4,1422
XS GIS Cut Line= 4
     1556477.191      272926.749     1556388.649       273890.29
     1556362.607       274484.04     1556206.357      275062.165
#Sta/Elev= 30
       0  872.44    68.4  877.61      88  876.95   195.5  858.36     303  845.47
     391  827.96   439.8  821.67   537.6  804.59     606  795.13   674.4  788.58
   723.3   784.8   899.2  775.55  1045.5  764.77  1240.4  762.71  1308.6  758.86
  1367.1  751.15  1415.8  749.85  1435.3  753.41  1464.5  764.68  1503.5  782.57
  1591.4  829.36  1630.6  854.12  1689.6  898.65    1719  918.18  1738.6  927.77
  1797.5  947.88    1827  955.35  1876.1  960.79  2121.5  976.03  2160.8  981.58
#Mann= 3 , 0 , 0
       0     .05       0  1367.1    .045       0  1435.3      .1       0
Bank Sta=1367.1,1435.3
XS Rating Curve= 0 ,0
Exp/Cntr=0.3,0.1

Type RM Length L Ch R = 1 ,73987.1 ,1046.2,1028.8,1011.2
XS GIS Cut Line= 4
     1555956.357      272718.415     1555638.649       273077.79
     1555263.649      273468.415     1555003.232      274025.707
#Sta/Elev= 30
       0  887.46   117.5  878.81   176.2  870.34   254.5  856.26   264.3  852.26
   283.9  841.92   293.7  838.51   303.5  837.19   313.3  838.08   342.6  844.45
   362.2  847.27   440.5  847.44   469.9  844.94   547.4  830.82   566.7   825.9
   576.4  821.77     615  802.48   692.4  760.44   731.1  746.88   750.4     746
   779.4  746.05   789.1  746.29   837.4  753.67   866.5  754.87   972.8  771.41
  1118.8  808.22  1362.9  875.24  1392.2  881.11  1509.4  900.13  1636.3  925.88
#Mann= 3 , 0 , 0
       0     .08       0   731.1    .045       0   779.4     .07       0
Bank Sta=731.1,779.4
XS Rating Curve= 0 ,0
Exp/Cntr=0.3,0.1

Type RM Length L Ch R = 1 ,72958.3 ,1619.3,1605.1,1590.4
XS GIS Cut Line= 4
     1554498.024      272249.665     1554524.066      272650.707
     1554529.274      273124.665     1554654.274      273937.165
#Sta/Elev= 30
       0  956.93    78.4  937.01   225.4   886.3   274.5  871.42   294.1  867.52
   352.9  861.84   421.2  850.92   440.6  845.53   479.3  830.32     518  819.49
   537.3  810.77   556.7  799.52   585.7  775.42   614.7     754   624.4   749.9
  641.44746.4515   653.4     746  677.65746.0704   779.1  749.22   885.7  755.79
  1091.2   775.5    1189   787.5  1316.3  809.53  1355.4  822.75  1453.3  843.17
  1492.4  856.06  1570.7  871.41  1619.6  874.19  1658.8  886.79  1697.9  892.74
#Mann= 3 , 0 , 0
       0      .1       0  641.44    .045       0  677.65     .05       0
Bank Sta=641.44,677.65
XS Rating Curve= 0 ,0
Exp/Cntr=0.3,0.1

Type RM Length L Ch R = 1 ,71353.2 ,1670.4,1675,1678.7
XS GIS Cut Line= 4
     1552721.982      273082.999     1553044.899      273572.582
     1553346.982      273968.415     1553675.107      274338.207
#Sta/Elev= 30
       0 1016.39    39.1 1007.73   117.3  986.83   127.1  982.16   185.7  946.59
     215  932.88   263.9  912.93   351.9  882.03   430.1  851.46     479  834.05
   527.8  806.56   547.4  801.12   615.8  788.26   713.4  775.69   742.7  773.37
   762.2  767.42   820.8  743.84   830.6  743.05   840.3     743   908.7  743.78
     977  751.12  1132.9   762.8  1142.6  764.31    1191  785.36  1258.9  811.24
  1307.4  827.51  1336.5  834.69  1355.8   837.3  1443.1  842.77  1578.8  853.63
#Mann= 3 , 0 , 0
       0      .1       0   830.6    .045       0   908.7     .05       0
Bank Sta=830.6,908.7
XS Rating Curve= 0 ,0
Exp/Cntr=0.3,0.1

Type RM Length L Ch R = 1 ,69678.2 ,513.4,539.3,565.6
XS GIS Cut Line= 6
     1552216.774      273707.999     1551831.357      274374.665
     1551763.649      274525.707     1552065.732       275109.04
     1552393.857      276051.749     1552713.826      276685.158
#Sta/Elev= 30
       0  856.39   224.2  826.23   389.9  822.85   565.4  830.55   623.8  835.94
     848  822.37   935.6  812.65   974.8  814.66  1033.6  796.35  1053.2  781.48
  1082.6  749.62  1092.5  743.98  1102.3  743.03  1112.1     743  1161.1     743
  1298.4  743.12  1563.1  752.01  2199.2  758.33  2267.7   765.2    2346  783.23
  2434.1     814  2512.4  845.99    2649  878.41  2736.5  876.31  2794.8  892.05
  2930.9  902.09    3067  900.64    3135  896.51  3251.7  904.22  3300.3  899.14
#Mann= 3 , 0 , 0
       0      .1       0  1102.3    .045       0  1161.1     .05       0
#XS Ineff= 2 , 0
                         1486.62          763.04
Permanent Ineff=
       F       F
Bank Sta=1102.3,1161.1
XS Rating Curve= 0 ,0
Exp/Cntr=0.3,0.1

Type RM Length L Ch R = 1 ,69139   ,1420.4,1444,1466.6
XS GIS Cut Line= 6
     1552080.146      273659.116     1551715.563      274304.949
     1551600.979      274549.741     1551132.229      275138.283
     1551033.271      275554.949     1550639.174      277084.463
#Sta/Elev= 30
       0  840.84    48.8  825.39   136.6  824.05   302.5  804.92   448.9  819.04
     605  819.69   896.1  790.63    1178  749.87  1305.1  740.32  1324.6   740.2
    1393  740.48    1481  747.03  1647.1  745.72  1695.9  761.68  1764.3  814.95
  1832.4  854.96  2017.4  936.26  2300.5  965.14  2477.1 1001.81  2663.5  960.07
  2781.2  939.83  2879.3  913.06  3016.6  903.77  3085.3     886    3154  890.12
  3222.7   868.5    3360  907.32  3546.4   950.8  3624.9  952.71    3772  939.67
#Mann= 3 , 0 , 0
       0     .05       0  1305.1    .045       0    1393     .05       0
Bank Sta=1305.1,1393
XS Rating Curve= 0 ,0
Exp/Cntr=0.3,0.1

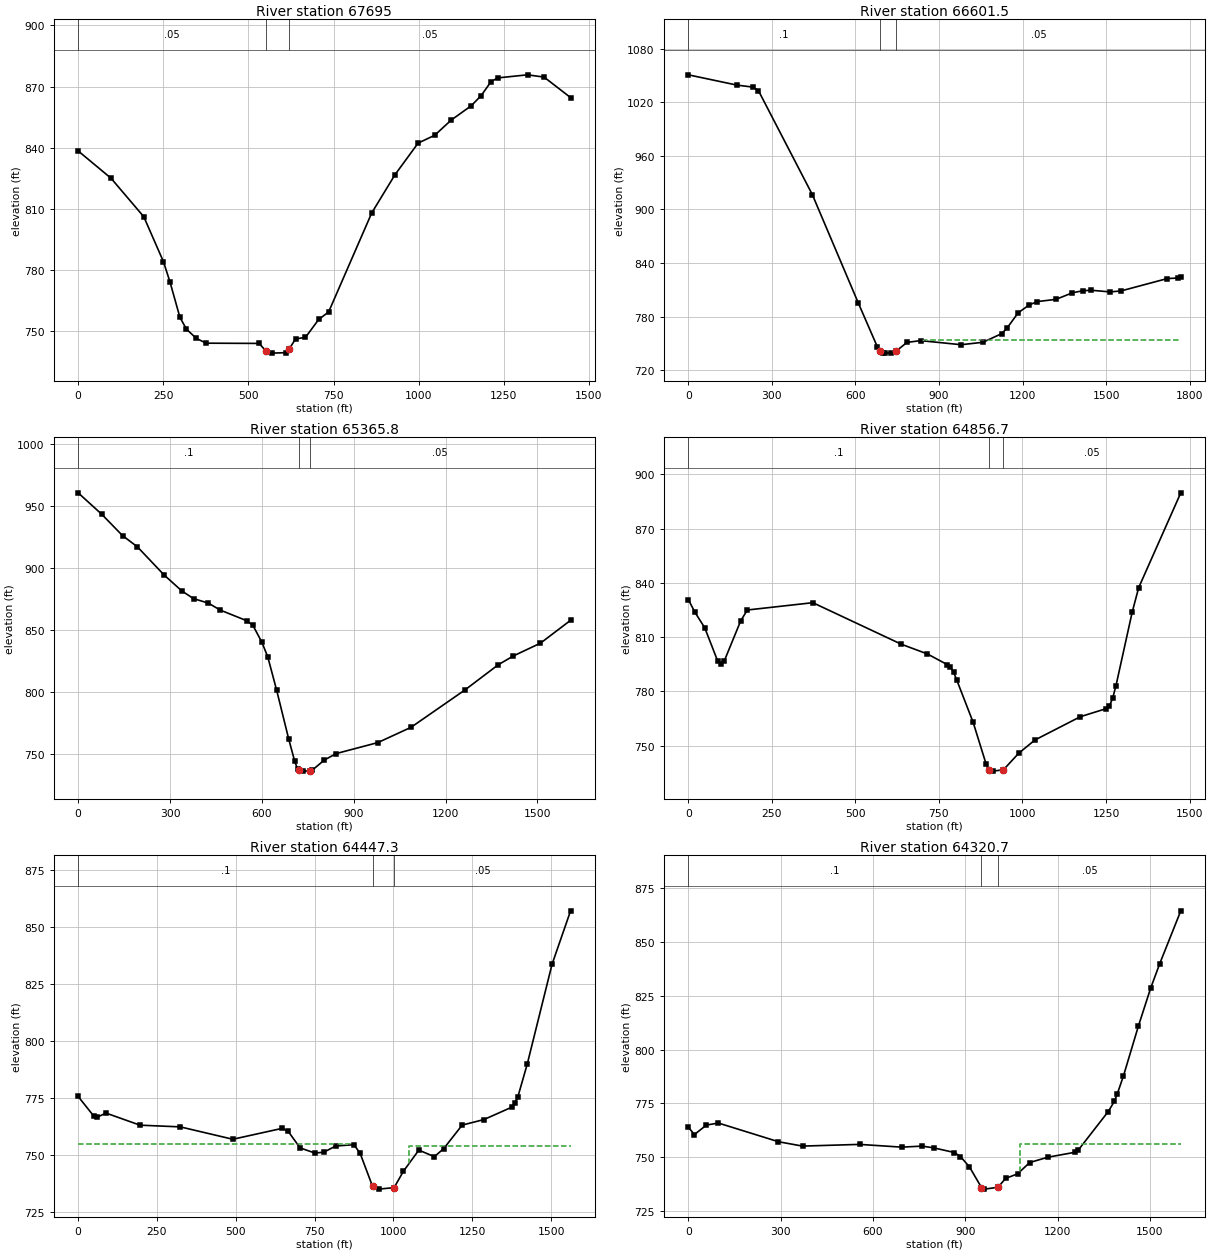
Type RM Length L Ch R = 1 ,67695   ,1109.9,1093.4,1074
XS GIS Cut Line= 4
     1552029.274       273609.04     1551654.274      273582.999
     1551258.441      273536.124     1550643.857      273806.957
#Sta/Elev= 30
       0  838.43    96.4  825.06   192.8  806.15   250.6  784.08   269.9  774.06
   298.8  756.84   318.1  751.04     347  746.53   375.9  744.18   531.4  744.06
   550.9  740.45   570.3   739.3   609.2  739.53     619  741.12   638.4  746.27
   667.6  747.04   706.4   755.8   735.6   759.5   862.1  808.02   930.2  826.71
   998.4  842.28    1047   846.1  1095.7  853.58  1154.1  860.54  1183.3  865.51
  1212.5  872.38    1232  874.23  1319.6  875.74  1368.2  874.63  1446.1  864.58
#Mann= 3 , 0 , 0
       0     .05       0   550.9    .045       0     619     .05       0
Bank Sta=550.9,619
XS Rating Curve= 0 ,0
Exp/Cntr=0.3,0.1

Type RM Length L Ch R = 1 ,66601.5 ,1257.5,1235.8,1214.3
XS GIS Cut Line= 4
     1552081.357      272197.582     1551690.732      272411.124
     1551331.357      272692.374     1550685.524      273270.499
#Sta/Elev= 30
       0 1050.57   174.2 1039.08   232.3  1036.8   251.6 1032.87   445.2  916.49
   610.2  795.25   678.2   746.5   687.9  741.34   697.6  739.31   707.3  739.15
   726.8  739.33   746.2  741.45     785  751.13   833.6  753.15   979.4  748.57
  1057.4  751.26  1125.5     761    1145  767.41    1184  784.18  1222.9  792.87
  1252.1  796.79  1320.3  799.34  1378.8  806.64  1417.7  809.02  1446.9   809.5
  1515.1  807.64  1554.1  808.79  1719.6  822.58  1758.6  823.19  1768.3  824.48
#Mann= 3 , 0 , 0
       0      .1       0   687.9    .045       0   746.2     .05       0
#XS Ineff= 2 , 0
                          842.11          753.34
Permanent Ineff=
       F       F
Bank Sta=687.9,746.2
XS Rating Curve= 0 ,0
Exp/Cntr=0.3,0.1

Type RM Length L Ch R = 1 ,65365.8 ,510,509,507.8
XS GIS Cut Line= 4
     1550409.482      271655.915     1550310.524       272109.04
     1550336.566      272603.832     1550399.066      273249.665
#Sta/Elev= 30
       0  960.71    77.3  943.32   144.9  926.14   193.2  917.14   280.2  894.45
   338.2  881.53   376.8  875.24   425.2  871.62   463.8  866.01   551.2  857.33
   570.7  853.62   599.8  840.09   619.2  828.21   648.4  801.07   687.3  762.09
   706.7  744.26   716.4  737.63   722.8  736.52   735.8   735.9  757.02736.1301
     765  736.78   803.8  744.84   842.7  750.08   978.9  758.97  1087.1   771.3
    1264  801.63  1372.2  821.88  1421.3  828.94  1509.8  839.28  1608.1  857.73
#Mann= 3 , 0 , 0
       0      .1       0   722.8    .045       0  757.02     .05       0
Bank Sta=722.8,757.02
XS Rating Curve= 0 ,0
Exp/Cntr=0.3,0.1

Type RM Length L Ch R = 1 ,64856.7 ,420.4,409.4,398.3
XS GIS Cut Line= 4
     1549705.146      271618.751     1549826.674      272403.474
     1549854.451      272674.307     1549975.979      273063.196
#Sta/Elev= 30
       0  830.69    19.6  823.72      49  815.14    88.2  796.53      98  795.27
   107.8  796.98   156.8  819.07   176.5  824.98   372.5  829.02   637.2  806.07
   715.6  800.67   774.5  794.82   784.3  793.39   794.1  790.47   803.8  786.01
   852.4  762.83   891.3  739.71     901  736.56   910.8  735.91  942.92736.6297
   988.5  745.76  1037.2  753.12    1173  765.98  1250.6  770.46  1260.4  772.04
    1270  776.27  1279.8  783.17  1328.2  823.67  1347.7  837.31  1473.8  889.75
#Mann= 3 , 0 , 0
       0      .1       0     901    .045       0  942.92     .05       0
Bank Sta=901,942.92
XS Rating Curve= 0 ,0
Exp/Cntr=0.3,0.1

Type RM Length L Ch R = 1 ,64447.3 ,126.5,126.5,126.6
XS GIS Cut Line= 5
     1549399.066      271650.707     1549352.191       272296.54
     1549367.816       272484.04     1549482.399      272666.332
     1549878.232      272989.249
#Sta/Elev= 30
       0  775.79    49.1  767.28    58.9  766.63    88.3  768.52   196.2  763.22
   323.8  762.48   490.6  757.05   647.5  761.84   666.4  760.46     704  753.26
     751     751   779.2  751.39   816.9  754.09   874.8  754.67   894.4  750.85
   933.6  736.46   953.1   735.2  1002.1  735.85  1031.4  742.98  1080.5   752.3
  1129.6  749.42  1159.1   752.9    1218  763.26  1286.8  765.67  1375.2   771.1
    1385  772.98  1394.8  775.75  1424.3  789.96  1502.9  833.67  1561.8  857.14
#Mann= 3 , 0 , 0
       0      .1       0   933.6    .045       0  1002.1     .05       0
#XS Ineff= 2 , 0
             864     755 1048.01           753.9
Permanent Ineff=
       F       F
Bank Sta=933.6,1002.1
XS Rating Curve= 0 ,0
Exp/Cntr=0.3,0.1

Type RM Length L Ch R = 1 ,64320.7 ,690.8,723.2,753.6
XS GIS Cut Line= 5
     1549317.993      271654.342     1549252.889      272344.446
     1549258.441      272525.707     1549373.024      272707.999
     1549768.857      273030.915
#Sta/Elev= 30
       0  763.92    19.5  760.49    58.6  764.92    97.6  765.85   292.9  757.17
     371  755.14   556.5  755.93   693.2  754.66     760  755.13   798.2   754.3
     865  752.15   884.3   750.3   913.7  745.49   952.8  735.87   962.6  735.14
 1006.58 735.998  1031.1  740.12  1070.2  742.24  1109.5   747.5  1168.4  749.97
  1256.8  752.27  1266.7  753.16  1364.9  771.21  1384.5  775.87  1394.4  779.47
    1414  787.62  1463.1  811.02  1502.4  828.42  1531.9  839.82  1600.7  864.49
#Mann= 3 , 0 , 0
       0      .1       0   952.8    .045       0 1006.58     .05       0
#XS Ineff= 2 , 0
                         1077.59           756.1
Permanent Ineff=
       F       F
Bank Sta=952.8,1006.58
XS Rating Curve= 0 ,0
Exp/Cntr=0.3,0.1