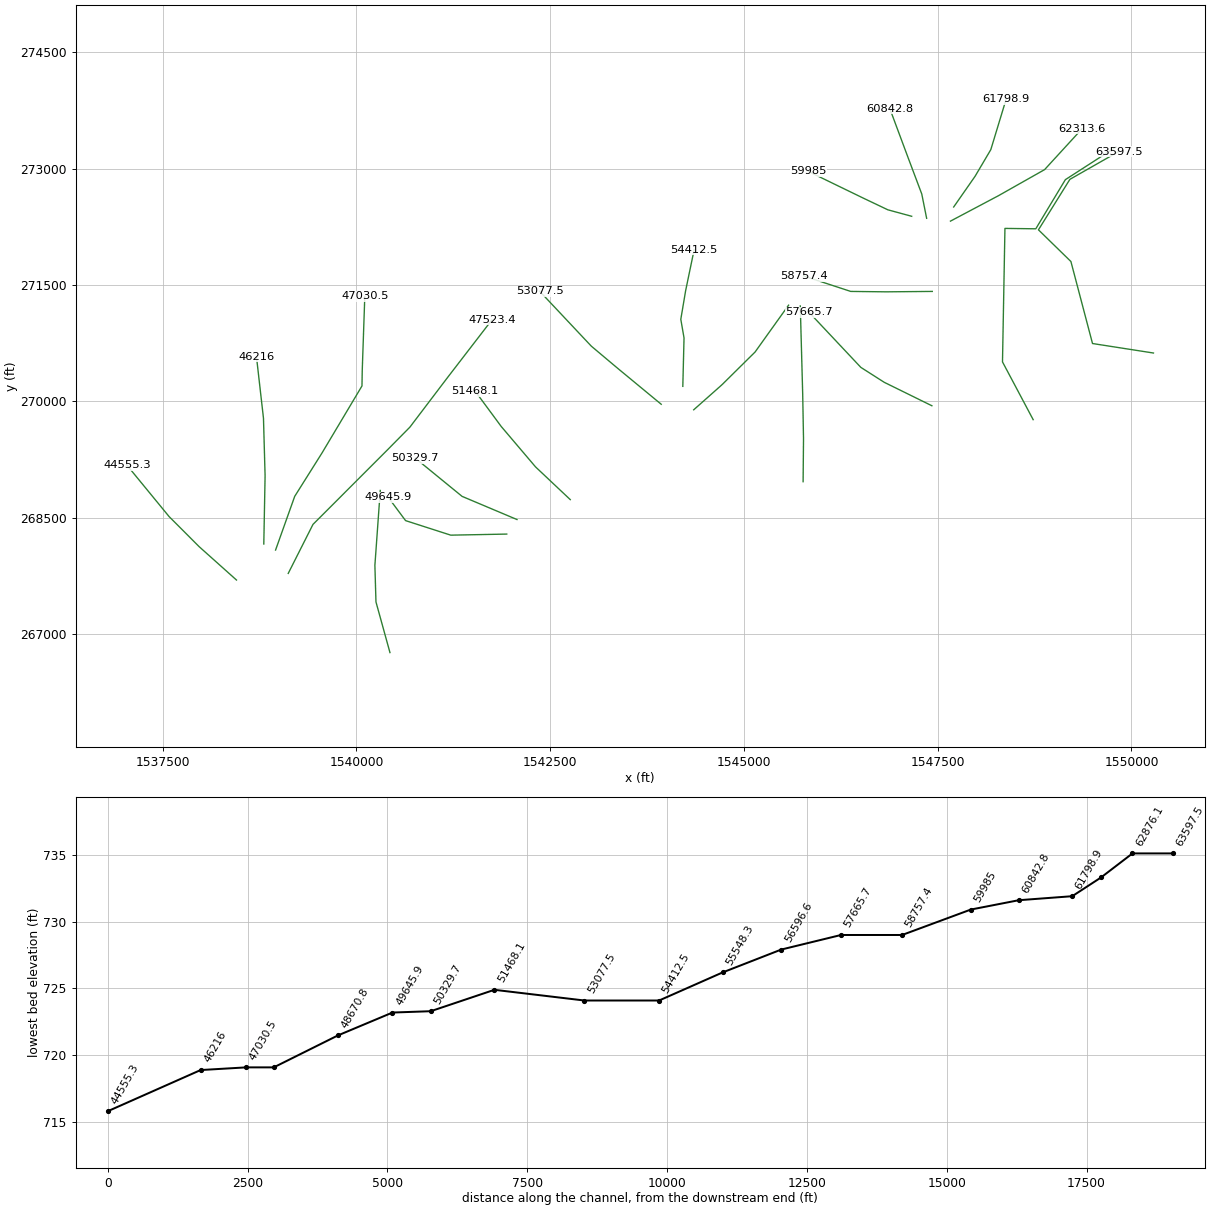
HEC-RAS study NFHGHSRV1.prj: NFHGHSRV1

--- NFHGHSRV1.g01 (geometry) --- (continued)

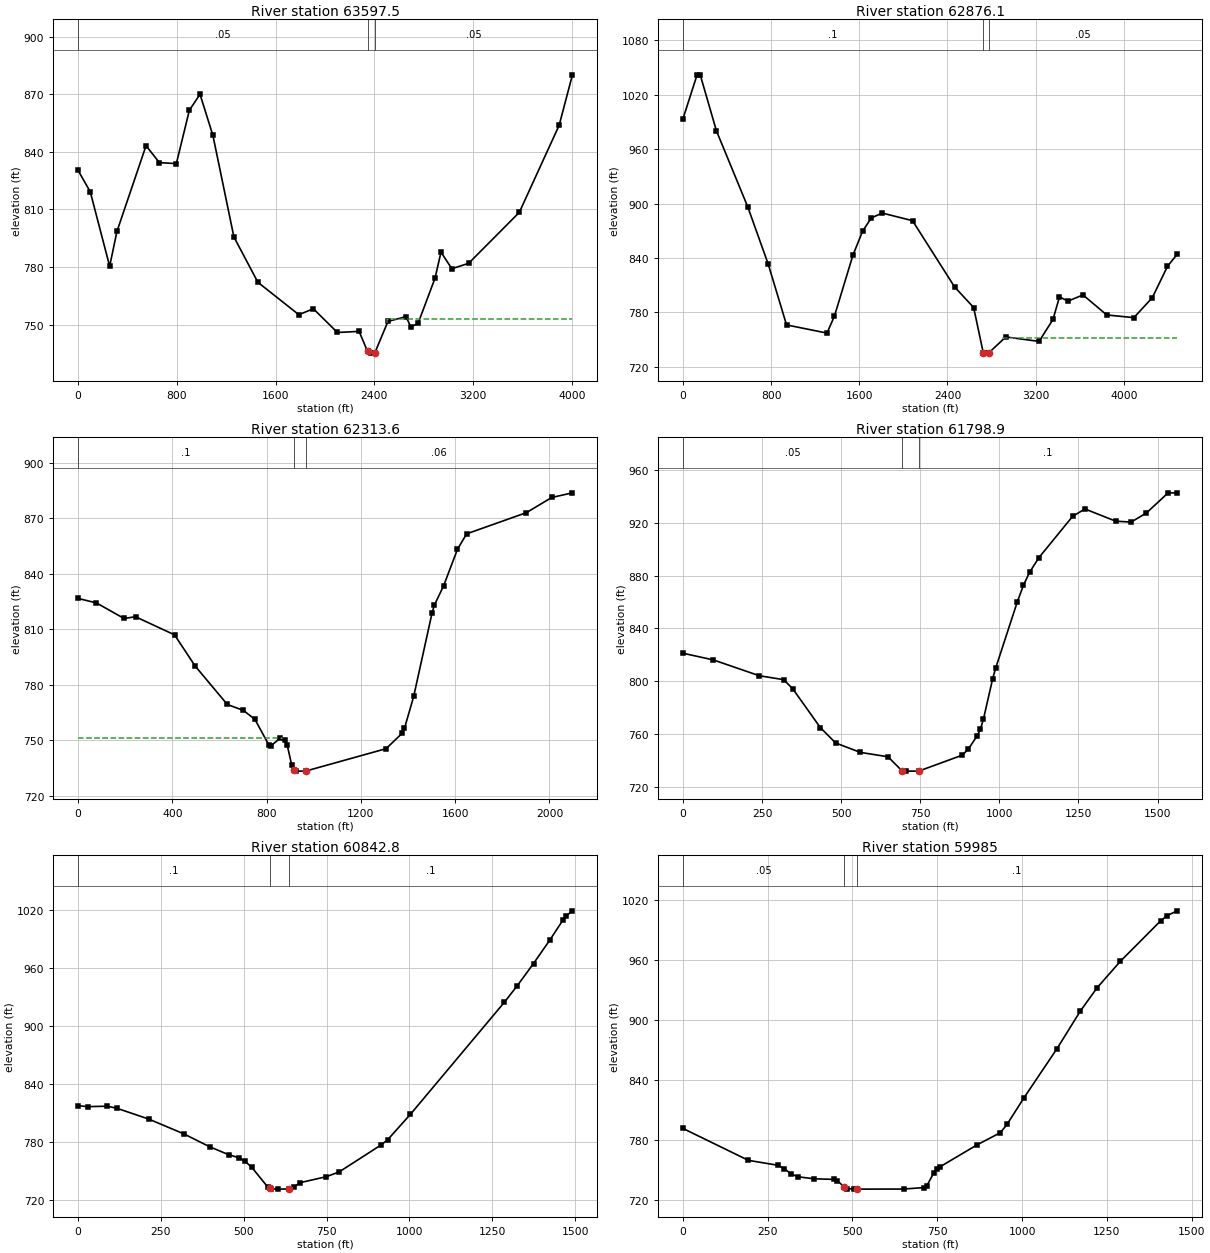
Type RM Length L Ch R = 1 ,63597.5 ,775.2,721.4,667.5
XS GIS Cut Line= 6
     1550284.139      270624.828     1549497.681      270747.224
     1549219.035      271804.515     1548800.107      272213.207
     1549205.869      272864.086      1549835.21      273222.158
#Sta/Elev= 30
       0  830.29    98.3  819.18   255.5  780.39   314.4  798.49   550.3  843.21
   658.4  834.39   795.9  833.87   901.4  861.68   987.6  870.01  1092.2  848.52
  1262.1  795.67  1456.6  772.02  1788.4  755.13  1905.9  758.23    2101  745.86
  2276.6  746.42  2344.9  736.08  2374.1   735.1  2403.4   735.1  2510.7  751.65
  2657.2  754.11  2696.3  748.71  2754.9  750.66  2891.6  774.09  2940.4  787.72
  3028.1  779.08  3164.4  781.91  3574.9  808.45  3897.8  853.85  4005.4  880.14
#Mann= 3 , 0 , 0
       0     .05       0  2344.9    .045       0  2403.4     .05       0
#XS Ineff= 2 , 0
                         2504.11          752.75
Permanent Ineff=
       F       F
Bank Sta=2344.9,2403.4
XS Rating Curve= 0 ,0
Exp/Cntr=0.3,0.1

Type RM Length L Ch R = 1 ,62876.1 ,550.4,562.5,572.2
XS GIS Cut Line= 6
     1548732.056      269765.453     1548336.222      270510.244
     1548367.816      272231.436      1548765.91       272226.39
     1549147.275      272859.745     1549800.487      273280.752
#Sta/Elev= 30
       0  993.39   127.5 1041.63   156.9 1042.01     304  980.25   588.4  896.35
   774.8  832.93   940.1  766.21  1307.2   757.2  1375.2  776.11  1542.4  843.05
  1630.9   869.8  1709.6  884.19  1807.9  889.57  2083.1  881.18  2464.6  808.15
  2637.9  785.37  2725.3  735.36    2735   735.1  2773.9  735.25  2929.3  752.95
  3231.3  748.03    3358  772.29  3416.5   797.1  3494.2  792.49  3630.1  799.26
  3845.6  777.17  4091.5  774.24  4258.7   796.2  4396.4  830.78    4485  844.25
#Mann= 3 , 0 , 0
       0      .1       0  2725.3    .045       0  2773.9     .05       0
#XS Ineff= 2 , 0
                         2906.02          751.95
Permanent Ineff=
       F       F
Bank Sta=2725.3,2773.9
XS Rating Curve= 0 ,0
Exp/Cntr=0.3,0.1

Type RM Length L Ch R = 1 ,62313.6 ,502.6,514.7,528.5
XS GIS Cut Line= 4
     1547664.691      272325.186     1548284.482      272653.311
     1548879.625      272989.411     1549361.396      273514.585
#Sta/Elev= 30
       0   826.7    77.9  824.26   194.8  815.86   243.5   816.8   409.1     807
   496.8  790.09   633.1  769.34   701.3  766.14   750.1   761.3   808.7  747.59
   818.5     747   857.5  751.19     877  749.96   886.8   747.6   906.3  736.59
   916.1  733.71   925.9   733.3   964.9   733.3  1306.7  745.44    1375  753.78
  1384.8  756.45  1423.8  773.68  1501.9  818.87  1511.7  823.09  1550.8  833.51
  1609.3   853.2  1648.4  861.63  1902.2   873.1  2009.6   881.3  2097.5  883.82
#Mann= 3 , 0 , 0
       0      .1       0   916.1    .045       0   964.9     .06       0
#XS Ineff= 2 , 0
          865.81  751.13
Permanent Ineff=
       F       F
Bank Sta=916.1,964.9
XS Rating Curve= 0 ,0
Exp/Cntr=0.3,0.1

Type RM Length L Ch R = 1 ,61798.9 ,935.8,956.1,976.2
XS GIS Cut Line= 4
     1547706.357      272507.478     1547982.399      272903.311
     1548185.524      273247.061     1548383.441      273898.103
#Sta/Elev= 30
       0  821.16    96.5  816.07   241.3  804.12   318.5  801.14   347.5   794.1
   434.3  764.89   482.6  753.23   560.5   746.1   648.1  742.77  692.35732.1539
   706.6   731.9   745.5  731.93   881.9  743.91   901.3   748.3   930.5  758.82
   940.2  763.62   949.9  771.38   979.1  801.99   988.8  810.16  1056.8     860
  1076.3  872.65  1095.7  882.45  1124.9  893.46  1231.8  924.81  1270.7  930.37
  1367.9  921.13  1416.5  920.43  1465.1  927.38  1533.2  942.51  1562.3  942.59
#Mann= 3 , 0 , 0
       0     .05       0  692.35    .045       0   745.5      .1       0
Bank Sta=692.35,745.5
XS Rating Curve= 0 ,0
Exp/Cntr=0.3,0.1

Type RM Length L Ch R = 1 ,60842.8 ,838.7,857.7,876.3
XS GIS Cut Line= 4
     1547357.399      272361.645     1547294.899      272674.145
     1547112.607       273158.52     1546883.441      273773.103
#Sta/Elev= 30
       0  817.72      29  816.71    86.9  817.17   115.9  815.17   212.5  803.97
   318.7   788.7   396.8  775.35   455.4     767   484.7  764.08   504.2  760.19
   523.8  754.24   572.6  733.69  578.17732.6851   582.3  731.94   601.9   731.6
  635.25 731.767   650.7  733.72   670.2  738.26   748.4  744.39   787.4  749.22
   914.6  777.22   934.1  782.45  1002.7  808.64  1286.6  924.39  1325.7  941.54
  1374.7  964.42  1423.6  988.47  1462.8 1008.85  1472.6 1013.33  1492.2  1018.8
#Mann= 3 , 0 , 0
       0      .1       0  578.17    .045       0  635.25      .1       0
Bank Sta=578.17,635.25
XS Rating Curve= 0 ,0
Exp/Cntr=0.3,0.1

Type RM Length L Ch R = 1 ,59985   ,1216.6,1227.6,1237.4
XS GIS Cut Line= 4
     1547164.691      272387.686     1546857.399       272471.02
     1546539.691      272622.061     1545831.357      272965.811
#Sta/Elev= 30
       0  791.56     193  759.66   279.8  754.76   299.1  751.31   318.4  746.26
   337.9   743.3   386.8  741.22   445.4  740.63   455.2  739.41   474.7   733.3
   484.5  731.47     504   730.9   513.8   730.9   650.6  730.99   709.5   732.4
   719.4  734.32   739.1  746.78   748.9  750.88   758.8  753.35     867   775.1
   935.9   787.3   955.6  795.55  1004.8  821.74  1103.2  871.39  1172.1     909
  1221.3  932.16  1290.2  958.72  1408.3   998.9    1428 1004.29  1457.5 1009.02
#Mann= 3 , 0 , 0
       0     .05       0   474.7    .045       0   513.8      .1       0
Bank Sta=474.7,513.8
XS Rating Curve= 0 ,0
Exp/Cntr=0.3,0.1

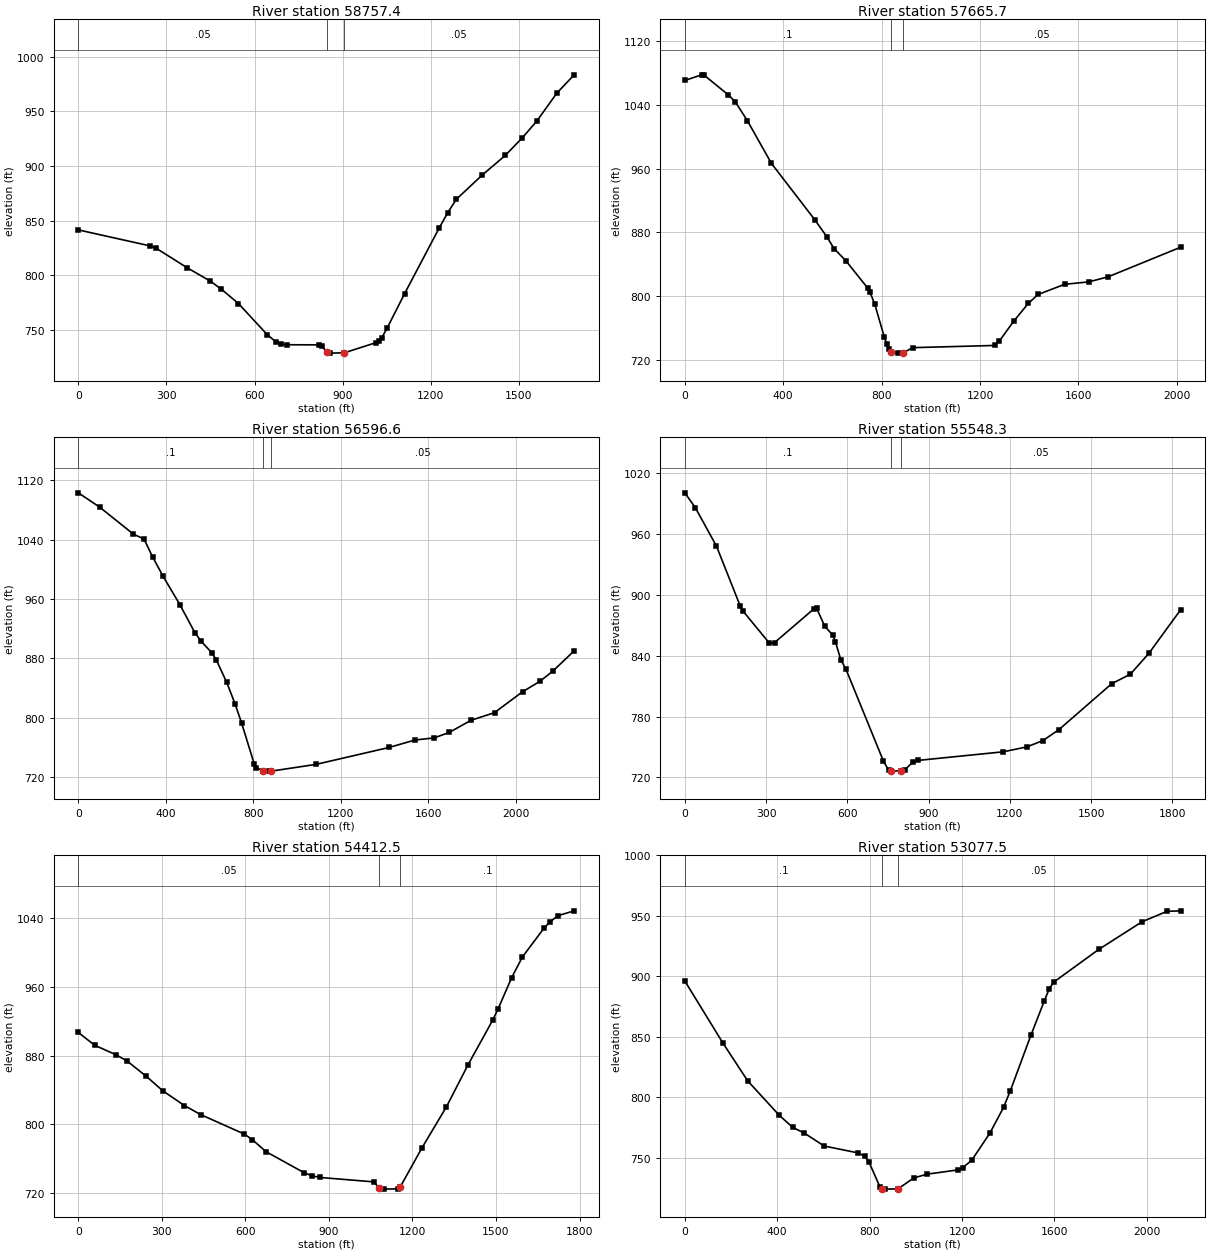
Type RM Length L Ch R = 1 ,58757.4 ,1103.3,1091.7,1077.8
XS GIS Cut Line= 4
     1547430.316      271418.936     1546836.566      271413.728
     1546378.232      271418.936     1545774.066      271616.853
#Sta/Elev= 30
       0  841.63   243.4  827.07   262.8  825.26   369.9  807.12   447.8  795.07
   486.7  787.52   545.1  774.33   642.5  746.02   671.8  739.44   691.3  737.33
   710.8  736.67   818.1  736.55   827.8  735.29   847.3  730.11   857.1     729
   905.8  729.32  1013.1  738.58  1022.9  739.91  1032.6  742.85  1052.1  752.35
  1110.8  783.42  1228.2  843.27  1257.5  857.39  1286.9  869.64  1374.9  891.79
  1453.2  909.65  1511.8  925.94  1560.7   941.1  1629.2  966.73  1687.9  983.39
#Mann= 3 , 0 , 0
       0     .05       0   847.3    .045       0   905.8     .05       0
Bank Sta=847.3,905.8
XS Rating Curve= 0 ,0
Exp/Cntr=0.3,0.1

Type RM Length L Ch R = 1 ,57665.7 ,1091.3,1069.1,1047.1
XS GIS Cut Line= 4
     1547425.107      269944.978     1546810.524      270247.061
     1546508.441       270439.77     1545841.774      271148.103
#Sta/Elev= 30
       0 1070.15    68.5 1077.24    78.3 1076.84   176.1 1052.35   205.4 1043.45
   254.4 1019.86   352.2  966.42   528.3  895.95   577.2  874.76   606.6  859.88
   655.5  844.34   742.9  810.65   752.6  805.39     772  790.53   810.7  749.49
   820.4  740.89   830.1  734.31   839.8  730.41   868.8     729   888.2  729.59
   926.9  735.85  1259.3  738.59  1278.9  744.18  1337.9  769.21  1396.8  791.28
  1436.2  802.37  1544.2   815.1  1642.5  818.16  1721.1  824.49  2015.8  861.51
#Mann= 3 , 0 , 0
       0      .1       0   839.8    .045       0   888.2     .05       0
Bank Sta=839.8,888.2
XS Rating Curve= 0 ,0
Exp/Cntr=0.3,0.1

Type RM Length L Ch R = 1 ,56596.6 ,1066.4,1048.2,1029.9
XS GIS Cut Line= 4
     1545763.649      268965.811     1545768.857      269517.895
     1545758.441      270090.811     1545727.191      271231.436
#Sta/Elev= 30
       0 1103.19    96.9    1084   251.8 1047.45   300.3 1040.88     339 1017.04
   387.4  990.66   464.9  951.98   532.7  914.61   561.8  902.83   610.4  887.39
   629.8  878.36   678.4  847.45   717.2  817.96   746.4  792.63   804.6  737.03
   814.3  732.52   843.5  728.27   872.6  727.91   882.3  727.91  1086.3     737
  1420.2  759.81  1538.3  769.84  1626.8  772.74  1695.6  780.14    1794  796.34
  1902.2  806.78  2030.1   834.9  2108.8  848.81  2167.8  862.53  2266.2  890.08
#Mann= 3 , 0 , 0
       0      .1       0   843.5    .045       0   882.3     .05       0
Bank Sta=843.5,882.3
XS Rating Curve= 0 ,0
Exp/Cntr=0.3,0.1

Type RM Length L Ch R = 1 ,55548.3 ,1121,1135.9,1150.4
XS GIS Cut Line= 4
     1544352.191      269892.895     1544716.774      270215.811
     1545143.857      270637.686     1545576.149      271241.853
#Sta/Elev= 30
       0 1000.59      39  985.88   116.9  948.04   204.6     889   214.3  884.18
   311.7  852.54   331.2   852.9   477.3  886.38     487  886.61   516.6     869
   546.1  860.38   555.9  853.86   575.6  836.19   595.3   826.4   733.1  736.15
   752.7  726.96  761.76726.2645   762.6   726.2  796.21726.5153   811.8  727.46
   841.3   734.9     861  736.77  1175.3  745.24  1263.3  750.14  1321.9  756.34
  1380.6  767.02  1576.1  812.43  1644.5  821.72  1712.9  842.28  1830.2  885.28
#Mann= 3 , 0 , 0
       0      .1       0  761.76    .045       0  796.21     .05       0
Bank Sta=761.76,796.21
XS Rating Curve= 0 ,0
Exp/Cntr=0.3,0.1

Type RM Length L Ch R = 1 ,54412.5 ,1312,1335,1358.1
XS GIS Cut Line= 5
     1544211.566      270194.978     1544227.191      270819.978
     1544185.524      271059.561     1544248.024      271429.353
     1544357.399      271955.395
#Sta/Elev= 30
       0  906.96    58.6     892   136.8   880.7   175.8  873.42   244.2  855.74
   302.8  838.99     381  821.62   439.6  811.05   595.9  788.38   625.2  781.78
   673.8  767.86     810   743.4   839.2  739.59   868.4  737.72  1060.7  732.58
  1079.9  725.52  1099.2   724.1  1147.2  724.44  1156.9  727.11  1233.8  772.08
  1321.6  819.92  1399.7  869.29  1487.6  920.95  1507.2  934.15    1556   970.8
  1595.1  995.17  1673.2    1029  1692.8 1035.59  1722.1 1043.18  1780.7  1048.9
#Mann= 3 , 0 , 0
       0     .05       0  1079.9    .045       0  1156.9      .1       0
Bank Sta=1079.9,1156.9
XS Rating Curve= 0 ,0
Exp/Cntr=0.3,0.1

Type RM Length L Ch R = 1 ,53077.5 ,1613.1,1609.4,1605.5
XS GIS Cut Line= 4
      1543932.92      269964.075     1543377.364      270422.408
     1543030.142      270714.075     1542363.475      271422.408
#Sta/Elev= 30
       0   896.1   165.5  844.63   272.5  813.49   408.8   785.1   467.2  775.09
   515.8  770.57   603.4  759.71   749.2  754.06   778.1  751.33   797.4  746.46
   845.6  725.56   855.3  724.24   864.9   724.1   922.8   724.3   990.4  733.25
  1048.3  736.46  1183.5  739.99  1203.2  741.76  1242.5  748.06  1321.1  770.49
    1380   791.7  1409.5  805.49  1497.9  851.05  1556.9  879.92  1576.5  889.06
  1596.2  895.03  1792.7  922.23  1979.4  944.99  2087.4   953.6  2146.4  954.03
#Mann= 3 , 0 , 0
       0      .1       0   855.3    .045       0   922.8     .05       0
Bank Sta=855.3,922.8
XS Rating Curve= 0 ,0
Exp/Cntr=0.3,0.1

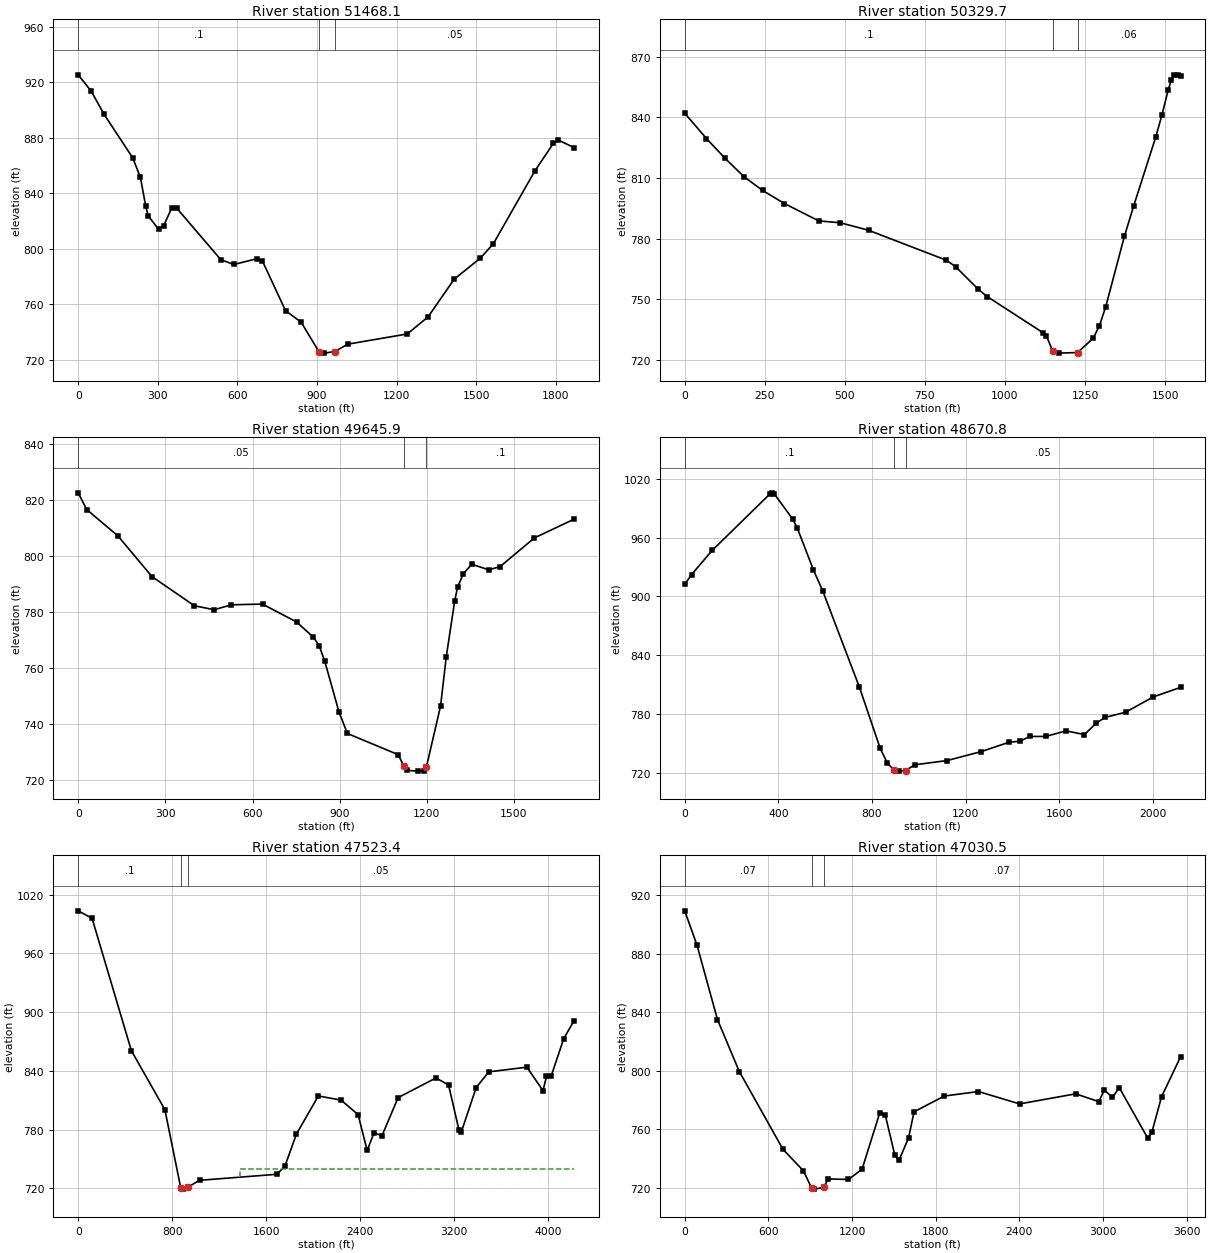
Type RM Length L Ch R = 1 ,51468.1 ,1134.1,1138.3,1142.4
XS GIS Cut Line= 4
     1542759.255      268734.745     1542311.338       269156.62
      1541868.63      269677.454     1541530.088      270135.787
#Sta/Elev= 30
       0  925.45    48.8  913.76    97.7  896.92   205.1  865.73   234.4  851.49
   253.9  831.24   263.7  823.78   302.8  814.21   322.3   816.8   351.6  829.21
   371.1  829.39   537.2  792.28     586  788.77   673.9  792.96   693.4  791.58
   781.3  755.45   839.9  747.23   908.3  725.52   927.8   724.9   966.9  726.05
  1015.7  731.36  1240.3  738.73  1318.5   751.1  1416.8  778.22    1515  793.28
  1564.1  803.67  1721.3   856.4  1790.1  875.98  1809.7  878.42  1868.7  872.91
#Mann= 3 , 0 , 0
       0      .1       0   908.3    .045       0   966.9     .05       0
Bank Sta=908.3,966.9
XS Rating Curve= 0 ,0
Exp/Cntr=0.3,0.1

Type RM Length L Ch R = 1 ,50329.7 ,675.5,683.9,692.3
XS GIS Cut Line= 3
     1542071.809      268477.964     1541363.475      268776.575
     1540759.309      269269.631
#Sta/Elev= 30
       0  841.99    68.1  829.43   126.5  819.61   184.9  810.61   243.3  803.77
   311.4  797.31   418.4  788.72   486.5  787.77   574.1  784.08   817.4  769.24
   846.7  765.95   914.9  755.16   944.2  751.31  1119.6  733.32  1129.4  731.85
  1148.9  724.37  1168.4   723.3  1226.8  723.59  1275.6  730.69  1295.1  736.88
  1314.6  746.22  1373.1  781.16  1402.3  796.31  1470.5     830    1490  841.03
  1509.5  853.36  1519.3  858.28    1529  860.68  1538.8  860.97  1548.5  860.22
#Mann= 3 , 0 , 0
       0      .1       0  1148.9    .045       0  1226.8     .06       0
Bank Sta=1148.9,1226.8
XS Rating Curve= 0 ,0
Exp/Cntr=0.3,0.1

Type RM Length L Ch R = 1 ,49645.9 ,1003.2,975.1,947.3
XS GIS Cut Line= 4
     1541939.864      268290.464     1541217.642      268276.575
     1540634.309      268464.075     1540412.087      268762.686
#Sta/Elev= 30
       0   822.6    29.3  816.62   136.7  807.22   253.8  792.69   400.2  782.25
   468.6  780.85   527.1  782.61   634.5  782.86   751.5  776.48   809.9  771.02
   829.3  768.06   848.8  762.44   897.4  744.44   926.6  736.65  1101.7  729.07
  1121.1  724.93  1130.8  723.48  1168.4   723.2  1189.2  723.33  1198.9  724.78
  1247.6  746.55    1267  764.02  1296.2  784.08  1305.9  788.84  1325.4  793.64
  1354.7  797.09  1413.4   795.1  1452.6  796.27  1570.2  806.48  1707.3   813.2
#Mann= 3 , 0 , 0
       0     .05       0  1121.1    .045       0  1198.9      .1       0
Bank Sta=1121.1,1198.9
XS Rating Curve= 0 ,0
Exp/Cntr=0.3,0.1

Type RM Length L Ch R = 1 ,48670.8 ,1181.1,1147.5,1147.5
XS GIS Cut Line= 4
      1540432.92      266762.686     1540252.364      267415.464
     1540238.475      267887.686      1540307.92      268852.964
#Sta/Elev= 30
       0  912.16    29.4  922.26   117.8  946.99   363.2 1004.38     373 1005.71
   382.8 1004.54   461.3  978.82     481  969.62   549.7  926.93     589   905.8
   746.2  807.15   834.8  744.69   864.3  730.28   893.8   722.2   913.5  721.49
     943  722.06   982.4  727.97  1120.2  732.28    1267   741.5  1384.3  750.95
  1433.2  752.14  1472.3  756.88  1540.7  756.91  1628.7  762.57  1706.9  758.82
  1755.8  770.22  1794.9  776.33  1882.9  781.69  2000.2  797.23  2117.5  807.03
#Mann= 3 , 0 , 0
       0      .1       0   893.8    .045       0     943     .05       0
Bank Sta=893.8,943
XS Rating Curve= 0 ,0
Exp/Cntr=0.3,0.1

Type RM Length L Ch R = 1 ,47523.4 ,487.8,492.8,501.2
XS GIS Cut Line= 6
      1539120.42       267783.52     1539439.864      268415.464
     1540398.198      269373.797     1540689.787        269668.9
     1541174.021      270306.402     1541748.838      271052.454
#Sta/Elev= 30
       0 1003.51     118  995.84   452.4  860.56   737.6  800.28  873.59719.7558
   894.7   719.1     934  721.14  1032.2  728.11  1690.2  734.27  1758.9   742.5
  1857.1  775.34  2043.7  814.34    2237  810.04  2381.8  795.27    2459  758.64
  2517.3  776.53  2585.6  773.78  2722.3  812.64  3044.5   832.7  3151.9  825.52
  3239.8  779.74  3259.3   777.1  3386.7  822.88  3494.6  838.98  3818.4  843.73
  3955.7  819.74  3985.2   834.3  4024.4  834.38  4132.3  873.03  4220.6  891.37
#Mann= 3 , 0 , 0
       0      .1       0  873.59    .045       0     934     .05       0
#XS Ineff= 2 , 0
                          1372.9          739.46
Permanent Ineff=
       F       F
Bank Sta=873.59,934
XS Rating Curve= 0 ,0
Exp/Cntr=0.3,0.1

Type RM Length L Ch R = 1 ,47030.5 ,801.3,814.6,827.5
XS GIS Cut Line= 6
     1538956.936      268084.445     1539203.753      268776.575
      1539557.92      269339.075     1540071.809      270200.186
     1540075.497      270406.739     1540108.213      271354.537
#Sta/Elev= 30
       0  909.27    88.2  885.88   235.1  834.98   391.9  799.46   705.4  746.24
   852.1   731.6   910.8  719.71   930.3   719.1   998.8   720.3  1028.1  726.09
  1174.7  725.68  1272.4  732.72  1399.5   771.3  1438.9  769.69  1507.7  742.16
  1537.2  738.77    1606  754.15  1645.3  771.92  1861.6  782.71  2107.4  785.78
  2402.3  777.33  2804.4  784.21  2970.7   778.9  3009.8  786.87  3068.4  781.73
  3117.3  788.42  3322.6  753.77    3352  758.26  3420.4  782.19  3557.3  809.62
#Mann= 3 , 0 , 0
       0     .07       0   910.8    .045       0   998.8     .07       0
Bank Sta=910.8,998.8
XS Rating Curve= 0 ,0
Exp/Cntr=0.3,0.1

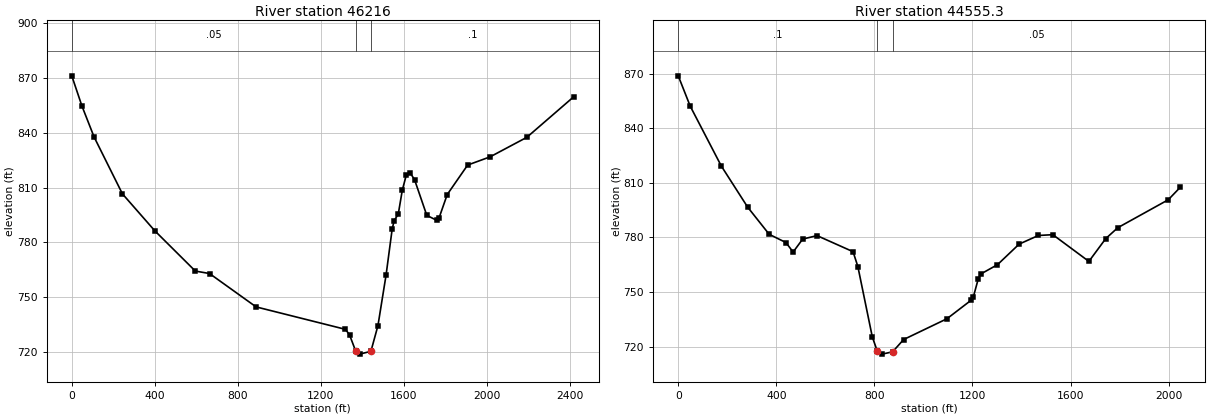
Type RM Length L Ch R = 1 ,46216   ,1643.4,1660.7,1678
XS GIS Cut Line= 4
     1538805.026       268162.57     1538821.809      269040.464
     1538800.975       269783.52     1538710.698      270575.186
#Sta/Elev= 30
       0  871.17    48.8  854.71   107.3  837.76   243.9   806.6     400  786.37
   595.1  764.35   663.4     763   887.8  744.74  1318.2  732.46  1337.8  729.47
  1367.1  720.65  1386.7   718.9 1440.78720.4365  1474.7  734.52  1513.8  762.17
  1543.2  787.33  1552.9     792  1572.5  795.48  1592.1  808.69  1611.6  817.02
  1631.2  817.83  1650.9  814.38  1709.9  794.84  1759.1  792.02    1769  793.42
  1808.3  806.21  1906.7  822.35  2014.9  826.84    2192  837.54  2418.2  859.77
#Mann= 3 , 0 , 0
       0     .05       0  1367.1    .045       0 1440.78      .1       0
Bank Sta=1367.1,1440.78
XS Rating Curve= 0 ,0
Exp/Cntr=0.3,0.1

Type RM Length L Ch R = 1 ,44555.3 ,1589.4,1590.4,1591.4
XS GIS Cut Line= 4
     1538452.596      267698.161     1537971.982       268127.27
     1537583.093      268516.158     1537041.427      269175.881
#Sta/Elev= 30
       0  868.85    48.8  852.18   175.7  819.25   283.1  796.66     371   781.7
   439.3  777.18   468.6  771.95   507.6  779.08   566.2  780.98     713  772.15
   732.7  763.97   791.6  725.28   811.3   717.7   830.9  715.82   874.2717.0641
   919.3  723.84  1096.1  735.28  1194.3  745.42  1204.1  747.47  1223.7  757.16
  1233.5  759.84  1302.2  765.01  1390.5  776.32    1469  781.06  1527.9   781.5
    1675  766.81  1743.7  779.34  1792.8  785.33  1998.8  800.71  2047.9  807.59
#Mann= 3 , 0 , 0
       0      .1       0   811.3    .045       0   874.2     .05       0
Bank Sta=811.3,874.2
XS Rating Curve= 0 ,0
Exp/Cntr=0.3,0.1