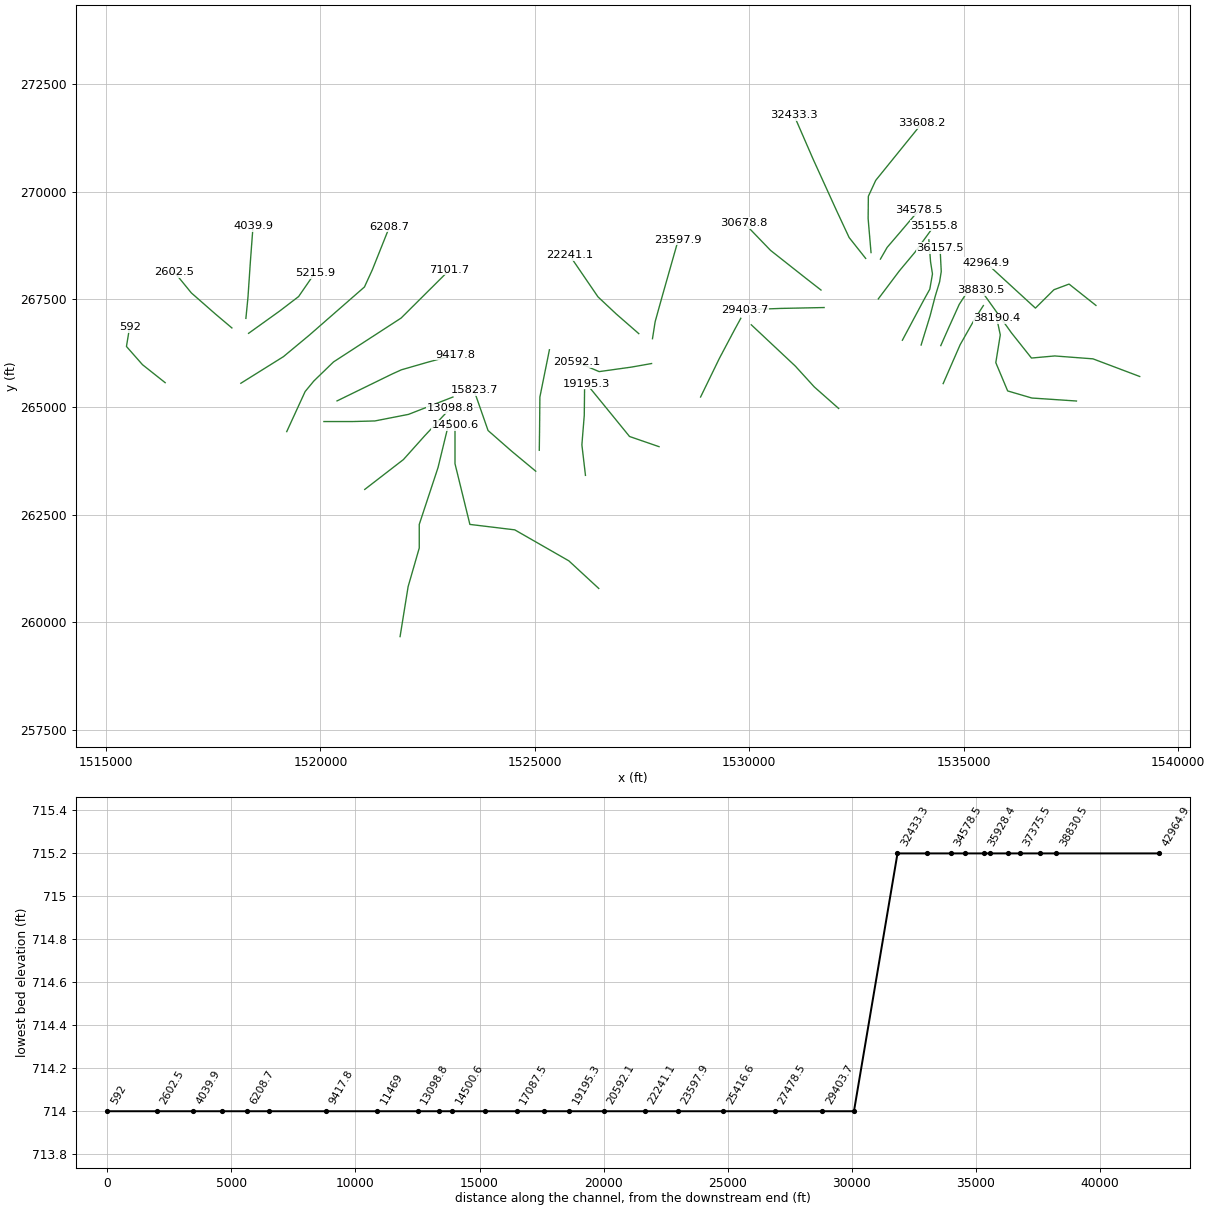
HEC-RAS study NFHGHSRV1.prj: NFHGHSRV1

--- NFHGHSRV1.g01 (geometry) --- (continued)

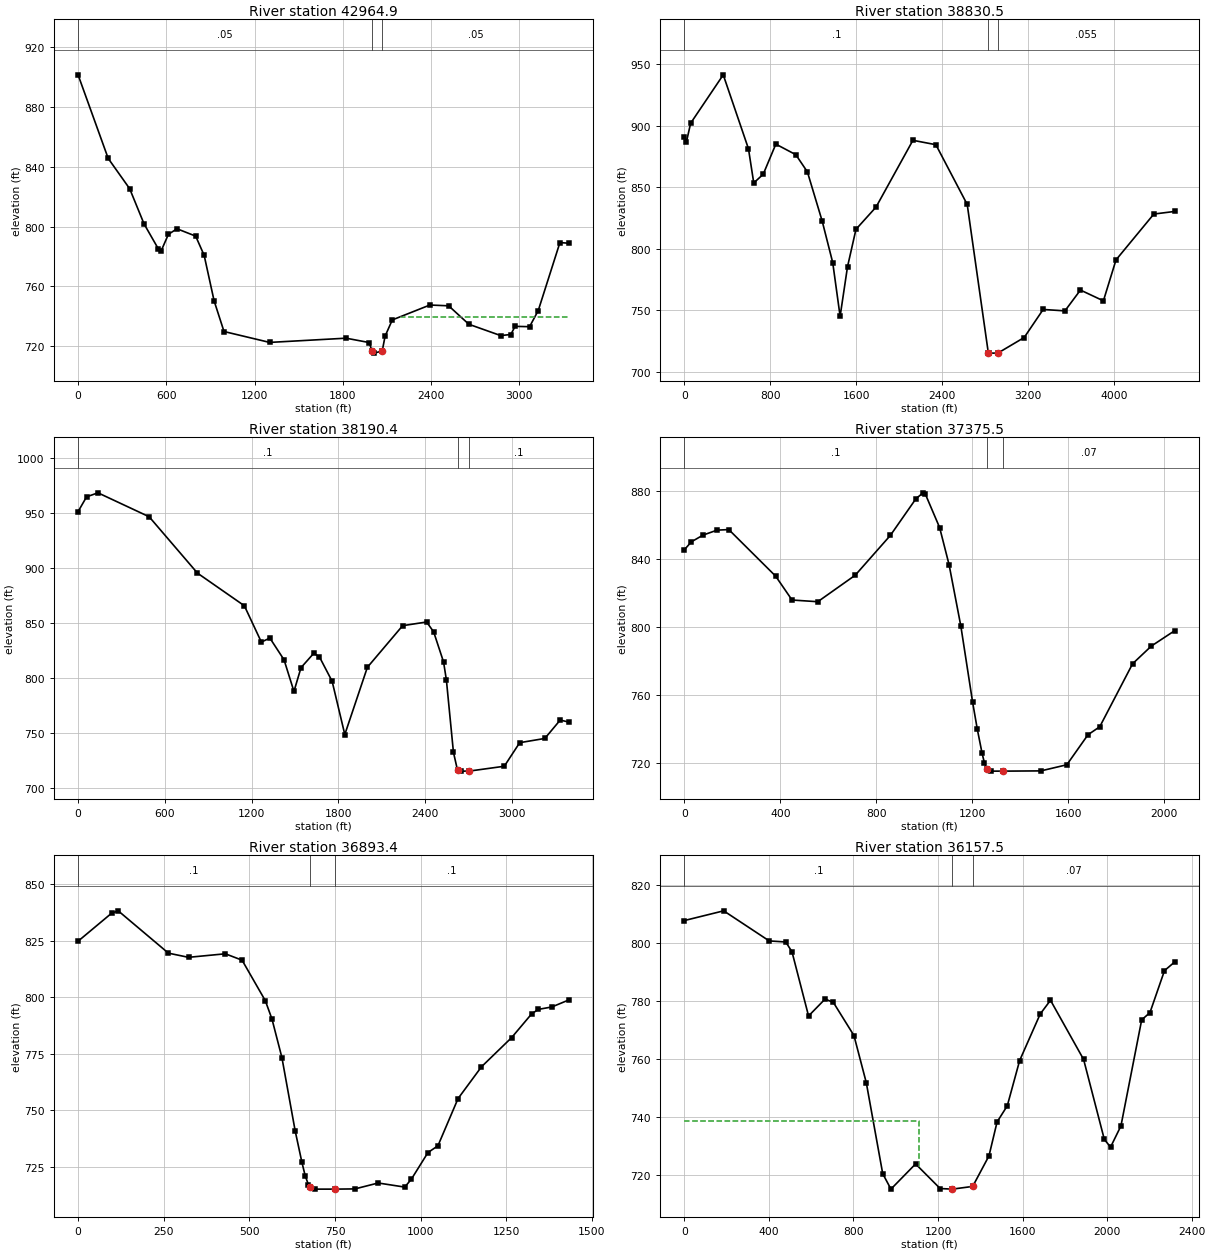
Type RM Length L Ch R = 1 ,42964.9 ,4137.4,4134.4,4130.6
XS GIS Cut Line= 5
     1538082.171      267359.745     1537454.899      267855.427
     1537103.005      267724.329     1536670.713      267297.245
      1535524.88       268344.12
#Sta/Elev= 30
       0  901.66   204.8  845.66     351  825.33   448.5   801.8     546     785
   565.5  783.87   614.2   794.8   672.7  798.52   799.5  793.59   857.2  780.72
   924.7  750.29   992.1  729.68  1302.4  722.38    1822  725.21  1979.2  722.29
  1998.8  716.54  2008.6   715.2  2067.6   716.5  2087.2  726.56  2136.3  737.45
  2391.7  747.43  2519.4   746.9  2656.9  734.53    2873  726.96  2941.8  727.68
  2971.3  733.14  3069.5  732.91  3128.5  743.73  3275.8  789.28  3334.7  788.84
#Mann= 3 , 0 , 0
       0     .05       0  1998.8    .045       0  2067.6     .05       0
#XS Ineff= 2 , 0
                         2187.32          739.52
Permanent Ineff=
       F       F
Bank Sta=1998.8,2067.6
XS Rating Curve= 0 ,0
Exp/Cntr=0.3,0.1

Type RM Length L Ch R = 1 ,38830.5 ,659.4,640.1,621
XS GIS Cut Line= 6
     1539102.769      265709.445     1538012.492      266119.168
      1537120.42      266186.297     1536578.753      266137.686
     1536113.475       266721.02     1535405.088      267708.704
#Sta/Elev= 30
       0   891.3    19.6  887.01    58.7  902.11   362.1  941.46     597  881.31
     646  853.58   734.1  860.62   851.5  885.12  1037.5  876.54  1145.2  862.57
  1282.7  822.62    1381   788.8  1449.8  745.11  1518.6  785.44  1597.3  815.86
  1784.1  833.94  2127.3  888.23    2341  884.65  2632.6  836.07    2829   715.4
  2838.8   715.2  2917.3   715.2  3162.8  727.89  3339.5  750.71  3541.9  749.55
  3686.3  766.48    3900  757.71  4017.3     791  4369.4  828.27  4564.9  830.41
#Mann= 3 , 0 , 0
       0      .1       0    2829    .045       0  2917.3    .055       0
Bank Sta=2829,2917.3
XS Rating Curve= 0 ,0
Exp/Cntr=0.3,0.1

Type RM Length L Ch R = 1 ,38190.4 ,822.8,814.9,806.6
XS GIS Cut Line= 6
     1537627.672      265139.784     1536587.741      265209.228
     1536023.505      265374.159     1535747.463      266030.409
      1535851.63      266676.242     1535769.165      267063.395
#Sta/Elev= 30
       0  951.15      59  964.58   137.7  968.21   491.6  946.45   825.9  895.19
    1150  865.54  1267.6  832.51  1326.4  836.18  1424.4  816.42  1492.9  787.68
  1541.9  809.31  1630.1  822.34  1669.1  819.06  1756.9  796.91  1844.6  748.48
  2000.7  809.59  2244.5  847.43  2410.4  850.78  2459.2  841.76  2527.6   814.4
  2547.1  798.08  2595.9   732.3 2623.97716.0678  2644.7   715.2  2703.3   715.2
  2947.4  719.63  3054.1  741.06  3227.9  744.91  3334.1  761.61  3392.1  759.87
#Mann= 3 , 0 , 0
       0      .1       0 2623.97    .045       0  2703.3      .1       0
Bank Sta=2623.97,2703.3
XS Rating Curve= 0 ,0
Exp/Cntr=0.3,0.1

Type RM Length L Ch R = 1 ,37375.5 ,478.3,482.1,485.7
XS GIS Cut Line= 4
     1534520.033      265544.298     1534915.866      266447.076
     1535256.144      267044.298     1535457.533      267356.798
#Sta/Elev= 30
       0  845.62    29.3  850.31    78.1  854.28   136.6   857.2   185.4  857.52
   380.6   830.1     449  816.02   556.3  815.02   712.5  830.64   858.9  854.09
   966.2  875.83   995.6  879.18  1005.4  878.22  1064.3  858.72  1103.6   836.9
  1152.7   800.7  1201.8   755.8  1221.4  739.88    1241  725.94  1250.9   720.1
  1260.7  716.32  1280.3   715.2  1329.4   715.2  1486.5  715.34  1594.6  718.95
  1682.9  736.65  1731.8  741.34  1868.8  778.48    1947   788.9  2044.9  798.01
#Mann= 3 , 0 , 0
       0      .1       0  1260.7    .045       0  1329.4     .07       0
Bank Sta=1260.7,1329.4
XS Rating Curve= 0 ,0
Exp/Cntr=0.3,0.1

Type RM Length L Ch R = 1 ,36893.4 ,732.6,735.9,739.2
XS GIS Cut Line= 4
     1534464.477      266426.242     1534658.922      266863.742
     1534895.033      267384.576     1535103.366       267704.02
#Sta/Elev= 30
       0  824.72    97.7  837.06   117.2  838.14   263.8  819.44   322.4   817.6
   429.9  819.16   478.8  816.34   546.6  798.46     566  790.38   595.1  773.31
   633.8  740.94   653.2  727.24   662.9   721.2   672.6  717.12  678.35716.0767
     692   715.2   750.2   715.2   808.3   715.3   876.2  717.91   953.7   716.1
   973.1  719.61  1021.5  731.36  1050.6  734.35  1109.3   755.2  1177.7  769.24
  1265.8  782.15  1324.4  792.66    1344  794.61  1383.1  795.67    1432  798.73
#Mann= 3 , 0 , 0
       0      .1       0  678.35    .045       0   750.2      .1       0
Bank Sta=678.35,750.2
XS Rating Curve= 0 ,0
Exp/Cntr=0.3,0.1

Type RM Length L Ch R = 1 ,36157.5 ,224.5,229.1,233.8
XS GIS Cut Line= 6
     1534006.144      266440.131     1534214.477      267113.742
     1534332.533      267565.131     1534436.699      267905.409
     1534475.588      268145.687     1534447.811      268694.298
#Sta/Elev= 30
       0  807.68   186.1  811.03   401.5  800.67   479.8   800.3   509.2  796.93
   587.6  774.83   665.9  780.66   705.1  779.47   802.3  768.09   860.6  751.88
   938.4  720.52   977.3   715.2  1093.9  723.88  1210.1   715.4  1267.8   715.2
    1364  716.13    1441  726.65  1479.4  738.35  1527.5  743.87    1586  759.46
  1683.3   775.5    1732  780.23  1888.6  759.86  1986.7   732.3  2016.2  729.68
  2065.2  736.96  2163.3  773.48  2202.5  775.99  2271.2  790.44  2320.2  793.47
#Mann= 3 , 0 , 0
       0      .1       0  1267.8    .045       0    1364     .07       0
#XS Ineff= 2 , 0
         1112.04  738.79 1555.18          747.11
Permanent Ineff=
       F       F
Bank Sta=1267.8,1364
XS Rating Curve= 0 ,0
Exp/Cntr=0.3,0.1

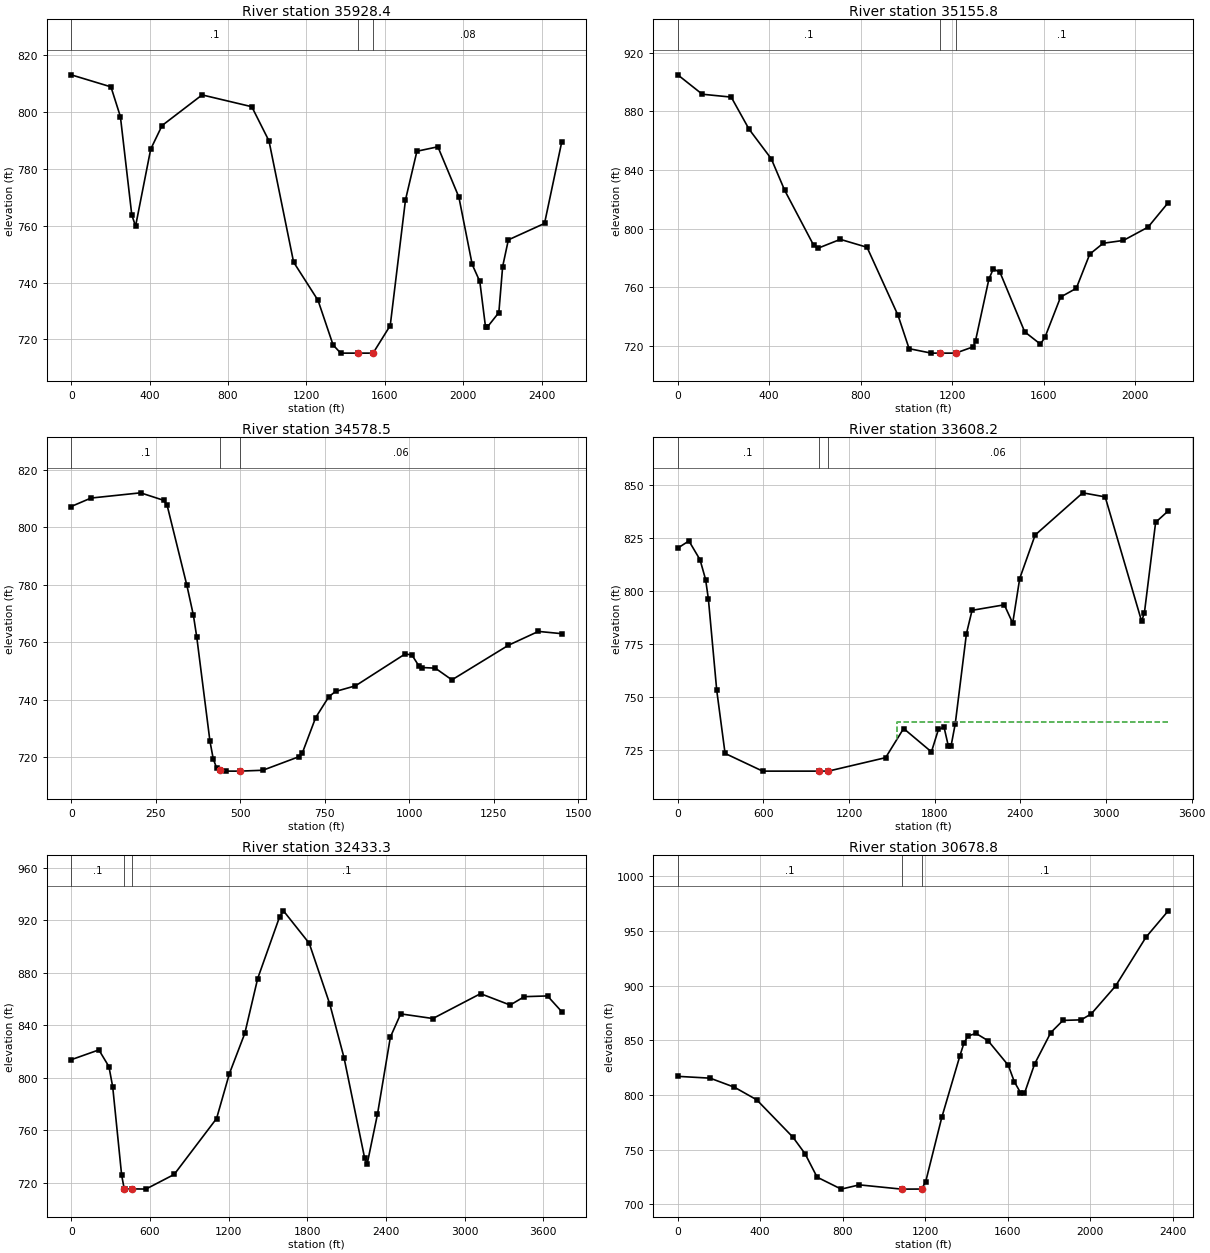
Type RM Length L Ch R = 1 ,35928.4 ,788,772.6,757.1
XS GIS Cut Line= 6
     1533569.338      266551.937     1534072.811      267492.909
     1534208.227      267735.965     1534270.727      268090.131
     1534225.588      268378.326     1534187.394      268881.798
#Sta/Elev= 30
       0  813.04   202.8  808.81     251  798.34     309  763.83   328.3   759.8
   405.5   786.9   463.5  795.21   667.8  805.98   921.1  801.83  1008.8  789.81
  1134.4  747.19  1259.1  733.74  1335.8  718.08  1374.6   715.2  1462.1   715.2
  1539.8   715.2  1627.3   724.9  1705.1  769.07  1763.4  786.18  1870.4  787.74
  1977.3  770.08  2045.3  746.38  2084.2  740.39  2113.3  724.41    2123  724.39
  2181.3  729.46  2200.7  745.64  2229.8  755.02  2414.3   760.8  2501.7  789.32
#Mann= 3 , 0 , 0
       0      .1       0  1462.1    .045       0  1539.8     .08       0
#XS Ineff= 2 , 0
                         1700.67          761.95
Permanent Ineff=
       F       F
Bank Sta=1462.1,1539.8
XS Rating Curve= 0 ,0
Exp/Cntr=0.3,0.1

Type RM Length L Ch R = 1 ,35155.8 ,577.1,577.3,577.6
XS GIS Cut Line= 4
     1533006.838       267510.27     1533499.894      268163.048
     1533861.005      268593.603     1534312.394      269211.659
#Sta/Elev= 30
       0  904.86   107.1  891.64   233.7  889.68   311.6  867.85     409  847.63
   467.5  826.18   594.1  788.78   613.6  786.72   710.9  792.73   827.8  787.33
   963.4  740.92  1011.8  718.24  1108.7   715.2  1147.5   715.2  1215.3   715.2
  1292.8  719.54  1302.5   723.8  1360.6  765.49    1380  772.65  1409.4  770.22
  1517.4  729.72  1586.1  721.33  1605.7  725.88  1674.4   753.4    1743  759.36
  1801.9  782.65  1860.8  790.08  1949.1     792    2057  801.06  2145.3  817.79
#Mann= 3 , 0 , 0
       0      .1       0  1147.5    .045       0  1215.3      .1       0
#XS Ineff= 2 , 0
                          1379.6          769.96
Permanent Ineff=
       F       F
Bank Sta=1147.5,1215.3
XS Rating Curve= 0 ,0
Exp/Cntr=0.3,0.1

Type RM Length L Ch R = 1 ,34578.5 ,954.3,970.3,986.3
XS GIS Cut Line= 4
     1533057.186      268435.617     1533213.436      268706.451
     1533499.894      269039.784     1533953.019      269571.034
#Sta/Elev= 30
       0   807.3    58.6  810.24   205.2  812.06   273.6  809.45   283.4  807.86
     342   779.9   361.5  769.38   371.3  761.87   410.3  725.65   420.1  719.42
   429.9  716.39   439.6  715.56   459.2   715.2   498.2   715.2   566.6   715.5
     674  720.24   683.8   721.6   722.9  733.82     762  741.11   781.7  742.93
   840.7  744.89   988.2  756.03  1007.9  755.56  1027.6  751.92  1037.4  751.26
  1076.7  751.04  1125.9  746.96  1293.1  759.02  1381.6  763.83  1450.4  763.04
#Mann= 3 , 0 , 0
       0      .1       0   439.6    .045       0   498.2     .06       0
Bank Sta=439.6,498.2
XS Rating Curve= 0 ,0
Exp/Cntr=0.3,0.1

Type RM Length L Ch R = 1 ,33608.2 ,1160,1175,1189.9
XS GIS Cut Line= 5
     1532838.436      268586.659     1532770.727      269373.117
     1532775.936      269893.951     1532947.811      270263.742
     1534031.144      271597.076
#Sta/Elev= 30
       0  820.21      78  823.59   155.9  814.73   194.9  805.42   214.4  796.25
   272.9  753.22   331.3  723.54   594.5   715.2   985.9   715.2  1054.7   715.2
  1455.9  721.54  1582.1  735.27  1776.9  724.27    1826  734.84  1865.3  735.89
  1894.7  727.24  1914.4  727.02  1943.8   737.5  2022.3  779.98  2061.6  790.92
  2287.4  793.51  2346.3  784.89  2395.4   805.9  2503.4  826.36  2837.1  846.24
  2994.2  844.32  3249.4  785.77  3269.1  789.84  3347.6  832.35    3436  837.74
#Mann= 3 , 0 , 0
       0      .1       0   985.9    .045       0  1054.7     .06       0
#XS Ineff= 2 , 0
                         1533.44          738.52
Permanent Ineff=
       F       F
Bank Sta=985.9,1054.7
XS Rating Curve= 0 ,0
Exp/Cntr=0.3,0.1

Type RM Length L Ch R = 1 ,32433.3 ,1782.3,1754.5,1795.4
XS GIS Cut Line= 6
     1532713.436      268451.242     1532510.311      268706.451
     1532328.019      268935.617     1532020.727      269591.867
     1531489.477      270753.326     1531041.561      271779.367
#Sta/Elev= 30
       0  813.78   211.1  821.26   287.8  808.52   316.6  793.11   384.7   725.9
   404.3  715.45     414   715.2   462.8  715.39   570.2  715.25   785.5   726.4
  1108.6  768.97  1206.5  803.17    1324  833.86  1422.2  875.62  1589.2   922.6
  1618.7   927.2  1815.2  902.49  1972.4  856.05  2080.5   815.4  2237.7  738.94
  2257.3  734.42  2335.9  772.35  2434.2  831.04  2512.8   848.7  2758.3  845.16
  3121.7   864.1  3347.6  855.43  3455.6  861.82  3632.4  862.36  3740.4  850.44
#Mann= 3 , 0 , 0
       0      .1       0   404.3    .045       0   462.8      .1       0
Bank Sta=404.3,462.8
XS Rating Curve= 0 ,0
Exp/Cntr=0.3,0.1

Type RM Length L Ch R = 1 ,30678.8 ,1259.1,1275.1,1291
XS GIS Cut Line= 4
     1531671.769      267716.867     1531322.811      267987.701
     1530494.686      268638.742     1529880.102      269274.159
#Sta/Elev= 30
       0  817.09   157.1  815.42   274.8  807.14   382.8  795.66   558.8  761.42
   617.3  746.37   675.8  724.95   792.9     714   880.6   717.9  1085.5     714
    1183  714.08  1202.5  720.82  1280.5   779.5  1368.3  835.76  1387.8  847.34
  1407.3   853.9  1446.4  856.35    1505  849.67  1603.2  827.19  1632.6  812.09
  1662.1  802.28  1681.8  801.64  1730.9  828.43  1809.4   857.1  1868.4  868.22
  1956.8  868.73  2005.9  874.23  2123.8  899.73  2271.1   944.3  2379.1  968.38
#Mann= 3 , 0 , 0
       0      .1       0  1085.5    .045       0    1183      .1       0
Bank Sta=1085.5,1183
XS Rating Curve= 0 ,0
Exp/Cntr=0.3,0.1

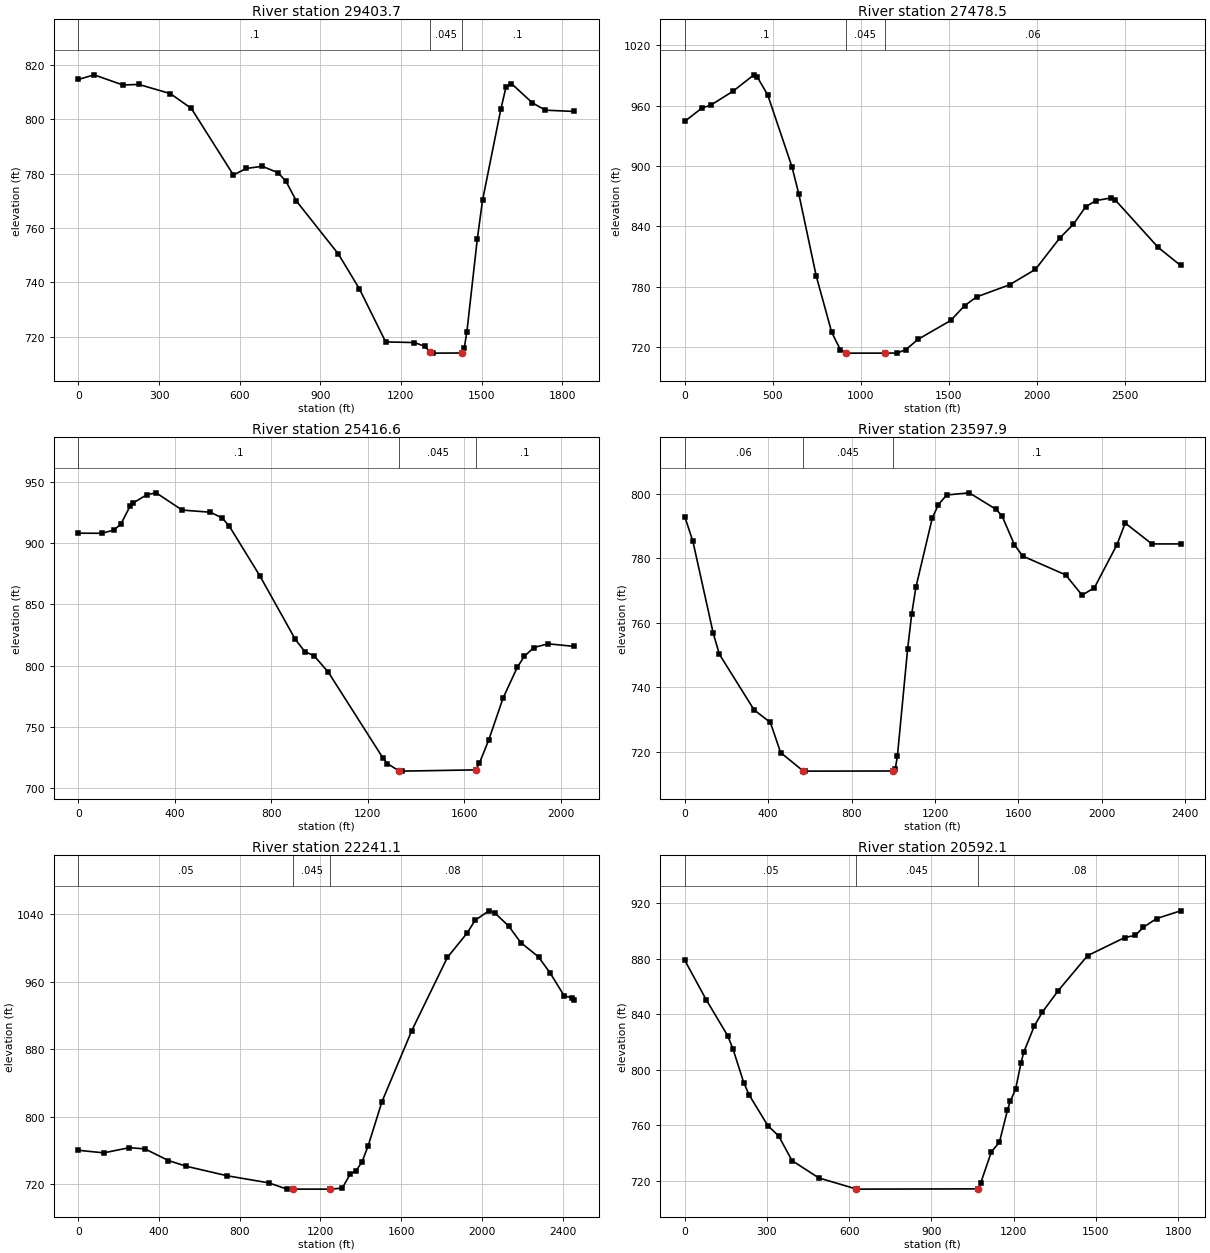
Type RM Length L Ch R = 1 ,29403.7 ,1944.8,1925.2,1905.5
XS GIS Cut Line= 3
     1531744.686      267310.617     1530718.644      267289.784
     1529900.936      267258.534
#Sta/Elev= 30
       0  814.67    58.6  816.38   166.2  812.63   224.8  812.85   342.1  809.48
   420.3  804.03   576.7  779.55   625.5  781.95   684.2  782.72   742.8  780.38
   772.1  777.25   811.2  769.95   967.6  750.42  1045.7   737.6  1143.2  718.13
  1250.3  717.89  1289.3  716.49  1308.8  714.25  1318.5     714 1425.95714.0459
  1435.4  715.78  1445.2  721.73  1484.1  755.98  1503.6  770.25  1571.8  803.83
  1591.3  812.01  1610.8  813.18  1688.7  806.09  1737.4  803.37  1844.6  802.91
#Mann= 3 , 0 , 0
       0      .1       0  1308.8    .045       0 1425.95      .1       0
Bank Sta=1308.8,1425.95
XS Rating Curve= 0 ,0
Exp/Cntr=0.3,0.1

Type RM Length L Ch R = 1 ,27478.5 ,2089.8,2061.9,2038.4
XS GIS Cut Line= 4
     1532083.227      264966.867     1531515.519      265466.867
     1531072.811      265951.242     1530046.769      266909.576
#Sta/Elev= 30
       0  944.48    98.2  957.89   147.4   960.6   275.1   974.6     393  990.81
   412.6  988.49   471.6  970.68   609.1  899.29   648.4  871.98   746.7  790.86
   834.8  734.66   883.8  717.48   913.2     714  1138.5     714    1207  714.12
    1256  717.46  1324.6  727.66  1510.9  746.48  1589.4  761.18  1658.2  769.95
  1844.7  781.94    1992   797.3  2129.4  828.32    2208  842.23  2276.7   859.5
  2335.6  865.74    2424  868.41  2443.6  866.68  2689.1  819.14  2816.7  801.19
#Mann= 3 , 0 , 0
       0      .1       0   913.2    .045       0  1138.5     .06       0
Bank Sta=913.2,1138.5
XS Rating Curve= 0 ,0
Exp/Cntr=0.3,0.1

Type RM Length L Ch R = 1 ,25416.6 ,1813.9,1818.7,1823.5
XS GIS Cut Line= 4
     1528864.477      265232.492     1529301.977      266128.326
     1529650.936      266784.576     1529801.977      267060.617
#Sta/Elev= 30
       0   908.1    97.7  907.98   146.6  910.62   175.9  915.34     215  930.39
   224.8  932.45   283.4  939.42   322.5     941   430.1  926.92   547.4  925.18
   596.2  920.43   625.5  913.84   752.6  873.14   899.2  821.44   938.3  811.53
   977.4     808  1036.1  794.64    1261  725.08  1280.6  720.18  1329.5  714.08
  1339.2     714  1646.7715.0193    1662   720.5  1701.1  739.64  1759.9  773.52
  1818.9  798.65  1848.4   807.7  1887.7  814.82  1946.7  817.84  2054.9  815.74
#Mann= 3 , 0 , 0
       0      .1       0  1329.5    .045       0  1646.7      .1       0
Bank Sta=1329.5,1646.7
XS Rating Curve= 0 ,0
Exp/Cntr=0.3,0.1

Type RM Length L Ch R = 1 ,23597.9 ,1332.1,1356.8,1381.4
XS GIS Cut Line= 4
     1527742.949      266586.659     1527805.449      266982.492
     1527958.227      267531.103     1528344.324      268884.051
#Sta/Elev= 30
       0  793.03    39.1  785.32   136.8  756.74   166.2  750.26   332.3  733.02
   410.6   729.1   459.6  719.76   567.7  714.05   577.5     714   999.7  714.04
  1009.6   714.8  1019.4   718.6  1068.6     752  1088.3  762.87    1108  771.03
  1186.7  792.56  1216.2  796.74  1255.6  799.71  1363.8  800.38  1491.7  795.29
  1521.2  793.21  1580.2  784.31  1619.6  780.77  1826.2   774.9  1904.9  768.61
    1964  770.94  2072.2  784.31  2111.5     791  2239.4  784.52  2377.2  784.52
#Mann= 3 , 0 , 0
       0     .06       0   567.7    .045       0   999.7      .1       0
Bank Sta=567.7,999.7
XS Rating Curve= 0 ,0
Exp/Cntr=0.3,0.1

Type RM Length L Ch R = 1 ,22241.1 ,1628.8,1649,1669.3
XS GIS Cut Line= 4
     1527423.505      266704.715     1526895.727      267163.048
     1526472.116      267558.881     1525805.449      268531.103
#Sta/Elev= 30
       0  760.04   126.2     757   252.4  763.14   330.1   761.7   446.6  747.88
     534  741.17   738.3   729.8   944.7   721.4  1033.1     714  1062.6     714
  1249.3     714  1308.2  715.21  1347.6  732.02    1377  735.87  1406.5  746.64
    1436  765.05  1504.7  817.62  1652.1  901.66  1828.9  988.61  1927.1 1017.63
  1966.4  1032.7  2035.2  1043.9  2064.7  1041.3  2133.4 1025.67  2192.4 1006.34
  2280.8  989.28  2339.7  969.66  2408.5  942.87  2447.8  940.87  2457.6   938.2
#Mann= 3 , 0 , 0
       0     .05       0  1062.6    .045       0  1249.3     .08       0
Bank Sta=1062.6,1249.3
XS Rating Curve= 0 ,0
Exp/Cntr=0.3,0.1

Type RM Length L Ch R = 1 ,20592.1 ,1419.9,1396.8,1373.6
XS GIS Cut Line= 4
     1527722.116       266010.27     1527249.894      265926.937
     1526499.894       265822.77     1525972.116      266044.992
#Sta/Elev= 30
       0   878.8    78.3  850.37   156.6  824.47   176.2  814.78   215.3  790.71
   234.9  781.83   303.4  759.64   342.5  752.34   391.4  734.54   489.4  722.04
  625.78714.1133     627     714  1069.5  714.18  1079.4   718.1  1118.7  740.78
  1148.2  747.78  1177.7  770.94  1187.6  777.21  1207.2  785.89  1226.9  804.79
  1236.7  812.41  1275.5  831.41  1304.7  841.39  1362.9  856.92  1469.7  882.05
  1605.6  895.13  1644.4  896.72  1673.5  902.52    1722  908.81  1809.4  914.36
#Mann= 3 , 0 , 0
       0     .05       0  625.78    .045       0  1069.5     .08       0
Bank Sta=625.78,1069.5
XS Rating Curve= 0 ,0
Exp/Cntr=0.3,0.1

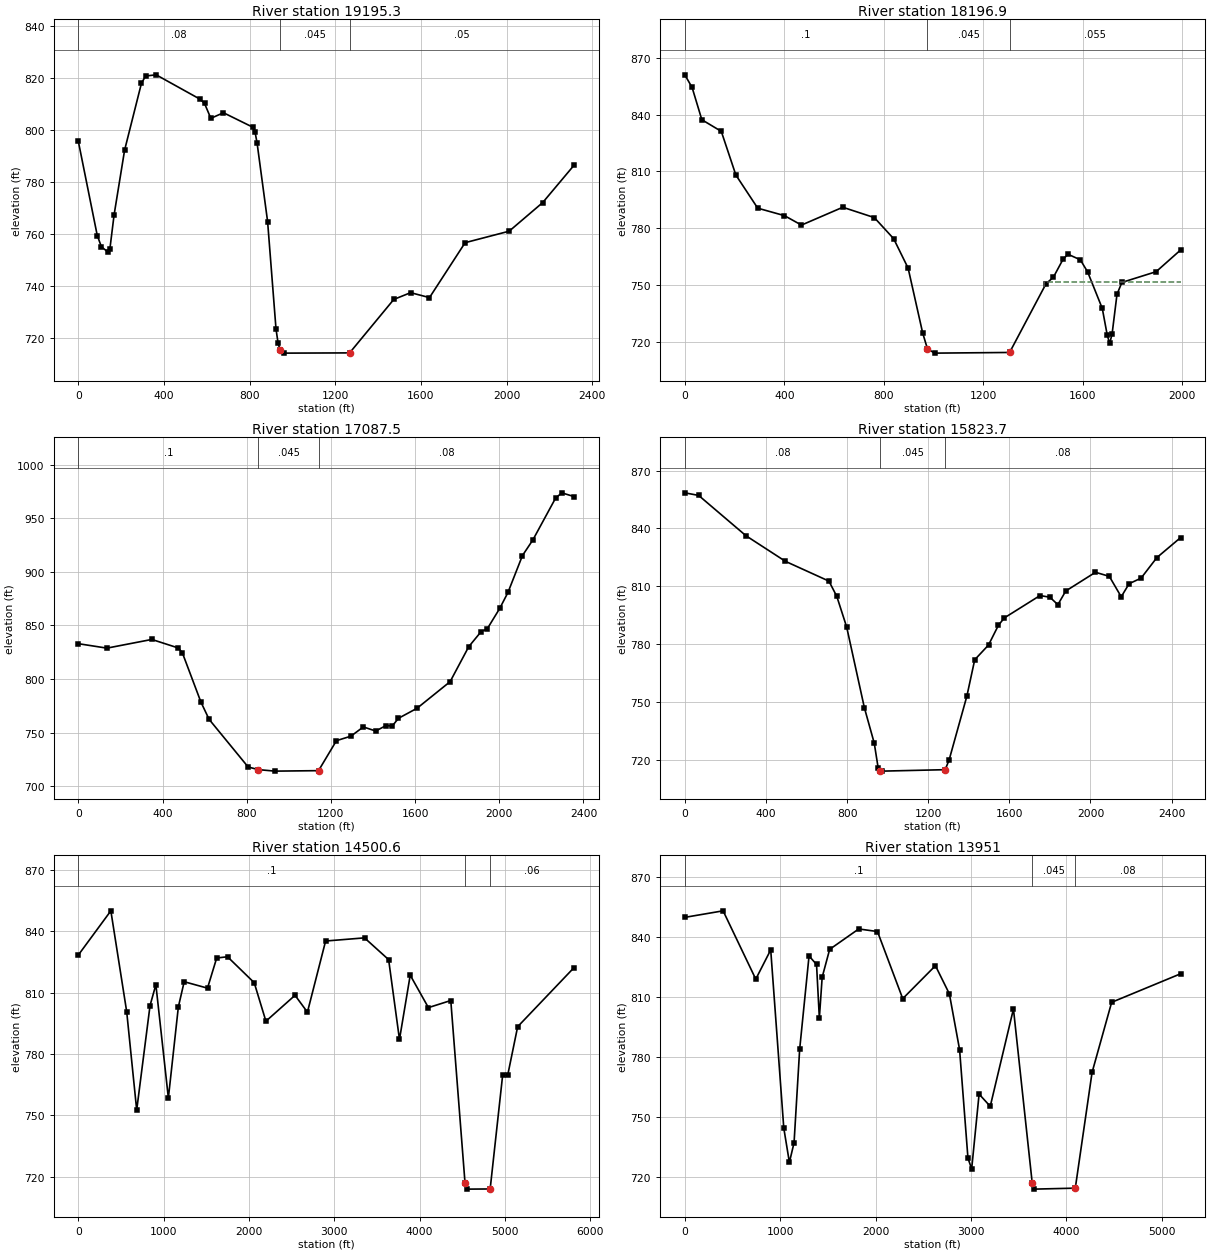
Type RM Length L Ch R = 1 ,19195.3 ,1015.7,998.5,981.2
XS GIS Cut Line= 4
     1527895.727      264079.715     1527208.227      264315.826
     1526698.491      264939.606     1526201.283      265544.992
#Sta/Elev= 30
       0  795.51    88.4  759.27     108   754.9   137.5  752.96   147.4   754.1
     167   767.2   216.1  792.12   294.7  817.84   314.3  820.66   363.5  821.11
   569.7  811.68   589.4  810.11   618.9  804.36   677.8  806.52   815.3  800.94
   825.2  799.21     835  794.83   884.1  764.63   923.4  723.21   933.2  717.79
     943  715.05   962.7     714  1267.2  714.09  1473.5  734.67  1552.1  737.27
  1640.2  735.37  1806.7  756.51  2012.3  760.93    2169  771.94  2315.9  786.36
#Mann= 3 , 0 , 0
       0     .08       0     943    .045       0  1267.2     .05       0
Bank Sta=943,1267.2
XS Rating Curve= 0 ,0
Exp/Cntr=0.3,0.1

Type RM Length L Ch R = 1 ,18196.9 ,1107.9,1109.4,1111
XS GIS Cut Line= 4
     1526180.449      263413.048     1526097.116      264121.381
     1526152.672      264808.881     1526159.616      265399.159
#Sta/Elev= 30
       0  861.06    29.3  854.38    68.4  837.34   146.6  831.19   205.2  808.12
   293.1   790.6   400.6  786.65     469  781.66   635.1  791.08   761.8  785.62
   839.5  774.49   897.8   758.9   956.1  724.74   975.5  716.22  1004.7     714
  1305.8  714.35  1452.2  750.67  1481.7  754.09    1521  763.69  1540.7  766.23
  1589.9  763.33  1619.4  756.94  1678.4  737.59  1698.1  723.65    1708   719.1
  1717.8  724.15  1737.5   745.1  1757.2  751.36  1894.9  757.04  1993.3  768.51
#Mann= 3 , 0 , 0
       0      .1       0   975.5    .045       0  1305.8    .055       0
#XS Ineff= 2 , 0
                         1444.82          751.54
Permanent Ineff=
       F       F
Bank Sta=975.5,1305.8
XS Rating Curve= 0 ,0
Exp/Cntr=0.3,0.1

Type RM Length L Ch R = 1 ,17087.5 ,1244.3,1263.8,1283.1
XS GIS Cut Line= 4
     1525104.061      263996.381     1525111.005       264510.27
     1525117.949      265232.492     1525340.172      266329.715
#Sta/Elev= 30
       0  832.94   135.8  828.79   349.1   836.9   475.2  828.93   494.5  824.32
   582.3  778.51   621.3  762.33   806.7  717.88   855.5   715.4   933.6     714
 1141.32714.4457  1226.4  742.45  1295.1  746.61    1354  755.25    1413  751.43
  1462.1  756.56  1491.5  756.11    1521   763.3  1609.4  772.68  1766.5  797.52
  1854.9  830.14  1913.8   844.2  1943.2  846.91  2002.2  865.88  2041.4  880.82
  2110.2  915.24  2159.3  929.68  2267.3  968.71  2296.8  973.74  2355.7  970.21
#Mann= 3 , 0 , 0
       0      .1       0   855.5    .045       0 1141.32     .08       0
Bank Sta=855.5,1141.32
XS Rating Curve= 0 ,0
Exp/Cntr=0.3,0.1

Type RM Length L Ch R = 1 ,15823.7 ,1337.9,1323.1,1308.3
XS GIS Cut Line= 4
     1525020.727       263510.27     1524458.227      263975.548
     1523909.616      264454.715     1523583.227       265385.27
#Sta/Elev= 30
       0  858.42    68.1  857.08   301.7  836.14   496.4  822.85   710.5  812.61
   749.4  804.66     798  788.77   885.4  746.86     934  728.51   953.4  715.57
   963.1  714.11   972.8     714  1283.6  714.75    1303  719.77  1390.4  752.83
  1429.3  771.79  1497.4  779.45  1546.3  789.72  1575.6  793.53  1751.3  805.12
  1800.1  804.24  1839.2  800.38  1878.2  807.47  2024.7  817.19    2093  815.07
  2151.6  804.47  2190.7  811.28  2249.3  814.13  2327.4  824.81  2444.5   835.2
#Mann= 3 , 0 , 0
       0     .08       0   963.1    .045       0  1283.6     .08       0
Bank Sta=963.1,1283.6
XS Rating Curve= 0 ,0
Exp/Cntr=0.3,0.1

Type RM Length L Ch R = 1 ,14500.6 ,564.1,549.7,535.7
XS GIS Cut Line= 6
     1526490.157      260786.829     1525792.602      261428.546
     1524531.824       262147.94     1523486.005      262274.159
     1523138.783      263683.881     1523138.783      264579.715
#Sta/Elev= 30
       0  828.45   381.1  850.06   566.7  800.78     684  752.64   840.4  803.75
   908.8  813.98  1055.2  758.54  1172.3   803.1  1240.6   815.4  1513.8  812.26
  1621.4     827  1748.5   827.6  2061.4  814.92  2198.4  796.09  2539.6  808.76
  2684.9  800.52    2898   835.3  3353.8  836.84  3636.6   826.2  3763.7  787.17
  3889.6   818.6  4102.7  802.74    4365  806.21  4531.9  716.99  4551.6     714
  4826.5  714.08  4973.3  769.89  5031.7  769.62  5148.6   793.4  5810.7  822.35
#Mann= 3 , 0 , 0
       0      .1       0  4531.9    .045       0  4826.5     .06       0
Bank Sta=4531.9,4826.5
XS Rating Curve= 0 ,0
Exp/Cntr=0.3,0.1

Type RM Length L Ch R = 1 ,13951   ,858.9,852.2,845.3
XS GIS Cut Line= 6
     1521858.213      259668.773     1522045.713      260828.495
     1522305.449      261725.548     1522305.449      262274.159
     1522742.949      263593.603     1523013.783      264704.715
#Sta/Elev= 30
       0  849.96   401.4  853.23     744  819.05   900.7   833.7  1037.7  744.57
  1096.5   727.4  1145.4   737.2  1204.3  784.02  1302.6  830.65  1381.2   826.4
  1410.7  799.58  1440.2  819.99  1518.8  833.96  1823.6  844.16  2020.2  842.87
    2285  809.29  2627.9  825.78  2774.1  811.68  2881.2  783.78  2968.9  729.48
  3007.8  724.12  3085.7  761.53  3202.6  755.42    3446  804.14  3642.5  717.14
  3662.1     714  4094.4  714.49  4270.3  772.38  4475.6  807.46  5198.9  821.74
#Mann= 3 , 0 , 0
       0      .1       0  3642.5    .045       0  4094.4     .08       0
#XS Ineff= 2 , 0
         3531.77  756.57
Permanent Ineff=
       F       F
Bank Sta=3642.5,4094.4
XS Rating Curve= 0 ,0
Exp/Cntr=0.3,0.1

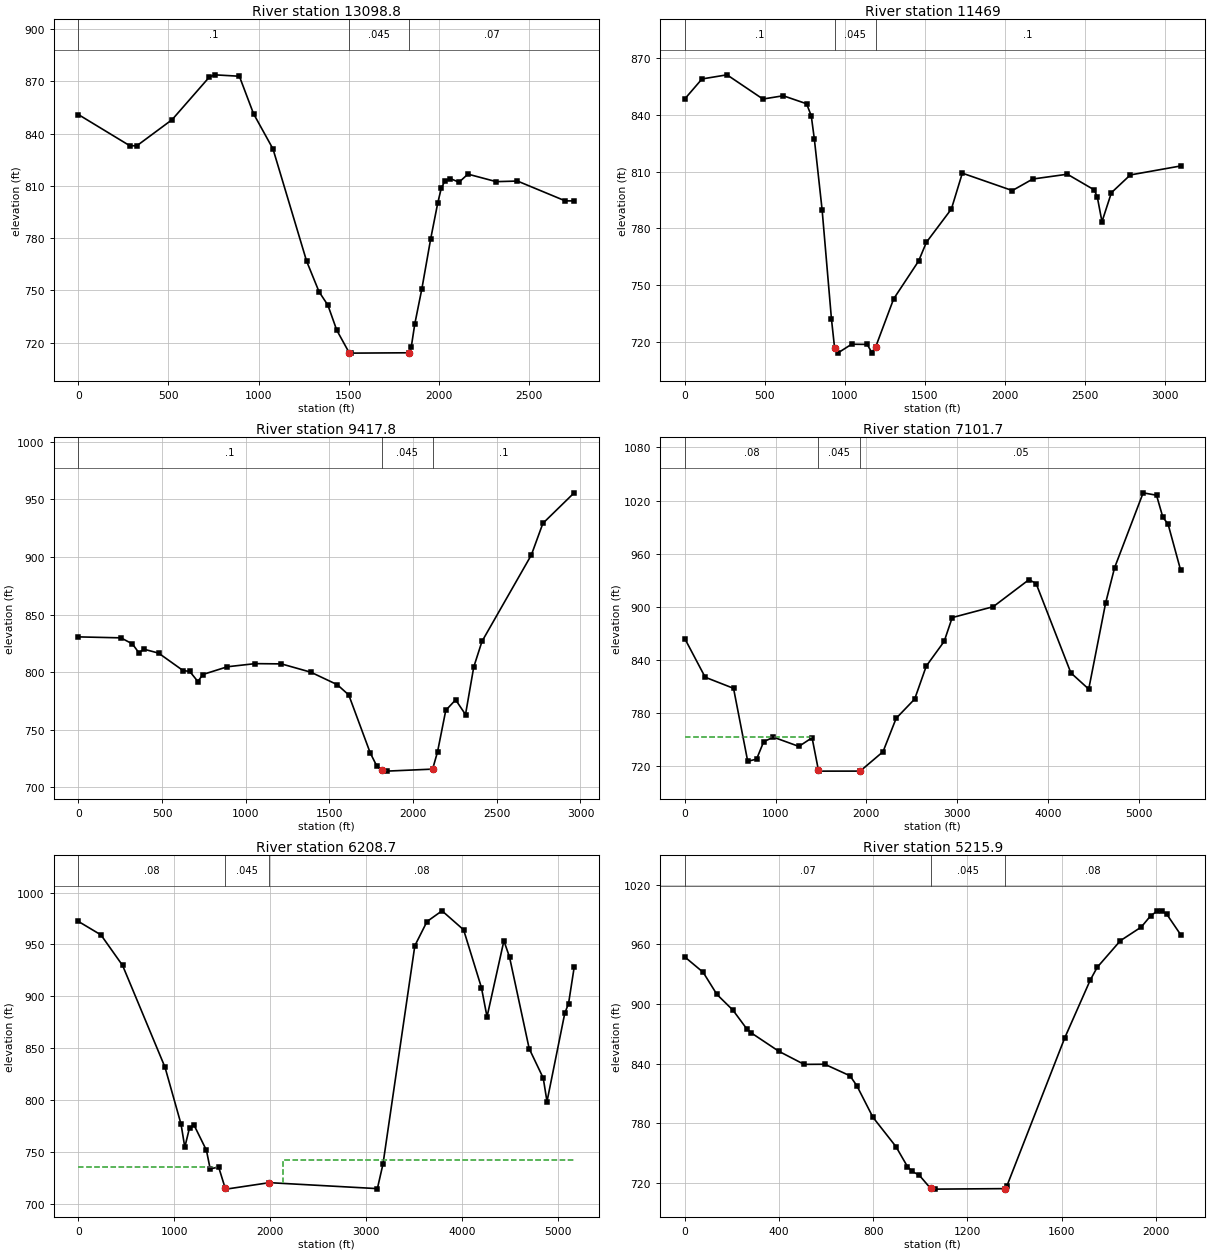
Type RM Length L Ch R = 1 ,13098.8 ,1648.3,1629.7,1610.6
XS GIS Cut Line= 4
     1521034.616      263086.659     1521937.394      263781.103
     1522430.449      264329.715     1523027.672      264968.603
#Sta/Elev= 30
       0  850.92   284.7  833.07     324  832.94   520.4  847.98   726.6  872.37
     756   873.7   893.5  872.89   972.1  851.39  1080.1  831.17  1266.8  766.73
  1335.7  749.21  1384.8  741.49    1434  727.15  1502.9  714.22  1512.7     714
  1837.2   714.2  1847.1  717.31  1866.8  730.69  1906.1  750.88  1955.2  779.63
  1994.5  800.26  2014.2  808.75  2033.8  812.68  2063.3   814.2  2112.4  812.07
  2161.6  816.72  2318.8   812.4  2436.7  812.74    2702  801.36  2751.2  801.35
#Mann= 3 , 0 , 0
       0      .1       0  1502.9    .045       0  1837.2     .07       0
Bank Sta=1502.9,1837.2
XS Rating Curve= 0 ,0
Exp/Cntr=0.3,0.1

Type RM Length L Ch R = 1 ,11469   ,2045.1,2051.2,2056.1
XS GIS Cut Line= 5
     1520083.227      264663.048     1520756.838      264663.048
     1521270.727      264676.937     1522055.449      264829.715
     1523090.172      265232.492
#Sta/Elev= 30
       0  848.41   107.4  858.96   263.6  861.14   488.1  848.34     615  850.07
   760.9  845.84     790  839.47   809.4  827.13   857.9  789.72   916.1  732.12
   935.5  716.96   954.9     714  1042.2  718.71  1139.2  718.61  1168.3  714.33
 1192.86717.3878  1304.7  742.68  1460.7  762.69  1509.4  772.61  1665.4  790.19
  1733.7  809.15  2046.1  799.95  2173.8  806.05    2390  808.59  2557.1  800.34
  2576.7  796.67  2606.2  783.48  2665.2  798.83  2783.1  808.21  3097.5  812.95
#Mann= 3 , 0 , 0
       0      .1       0   935.5    .045       0 1192.86      .1       0
Bank Sta=935.5,1192.86
XS Rating Curve= 0 ,0
Exp/Cntr=0.3,0.1

Type RM Length L Ch R = 1 ,9417.8  ,2306.2,2316.1,2326.9
XS GIS Cut Line= 5
     1520388.783      265142.215     1521673.505      265767.215
     1521888.783      265864.437     1522492.949      266038.048
     1523138.783      266211.659
#Sta/Elev= 30
       0  830.58   254.4  829.74   322.9  824.49   362.1  816.72   391.4   819.9
   479.5  816.48   626.3  801.27   665.4  800.63   714.3   791.8   743.7   797.9
   890.5  804.64  1056.8  807.35  1213.4  807.12  1389.5  799.89  1546.8  789.09
  1615.7  780.15  1743.5  729.97  1782.8  718.52  1812.2  714.61  1841.7     714
  2116.7  715.74  2146.2  730.85  2195.3  766.81  2254.2  775.91  2313.2  763.14
  2362.4  804.41  2411.5  826.63  2706.6  901.72  2775.4  929.18  2962.3  955.68
#Mann= 3 , 0 , 0
       0      .1       0  1812.2    .045       0  2116.7      .1       0
Bank Sta=1812.2,2116.7
XS Rating Curve= 0 ,0
Exp/Cntr=0.3,0.1

Type RM Length L Ch R = 1 ,7101.7  ,892.6,893,893.3
XS GIS Cut Line= 6
     1519215.852       264429.19     1519644.671      265359.745
     1519847.796      265604.537      1520306.13      266047.245
     1521881.838      267065.826     1523012.047      268185.617
#Sta/Elev= 30
       0  863.87   224.4  820.19   536.7  807.64   692.8  725.12   790.4  727.58
   868.5  747.26   975.8  752.41    1256  741.95  1401.5  751.76  1470.2   715.6
    1480     714  1930.9714.0197  2182.6  735.95  2327.4  773.75  2531.2  795.52
  2659.1  832.84  2855.8  860.68  2944.4  887.64  3396.6  899.98  3789.7  930.52
  3868.3  926.14  4251.2  825.09  4447.6  806.75  4634.2  904.39  4732.4  944.06
  5046.9 1028.73  5194.2    1026    5263 1001.35    5322   993.1  5459.5  941.26
#Mann= 3 , 0 , 0
       0     .08       0  1470.2    .045       0  1930.9     .05       0
#XS Ineff= 2 , 0
         1392.38  752.45
Permanent Ineff=
       F       F
Bank Sta=1470.2,1930.9
XS Rating Curve= 0 ,0
Exp/Cntr=0.3,0.1

Type RM Length L Ch R = 1 ,6208.7  ,994.6,992.8,990.8
XS GIS Cut Line= 6
     1518145.727      265551.937     1519138.783      266169.992
     1519742.949      266669.992     1521027.672      267788.048
     1521211.987      268188.051     1521611.685      269186.134
#Sta/Elev= 30
       0  972.27   235.9  959.26     462  929.73   904.3  831.54  1071.4   776.7
  1110.7  754.44  1159.8  773.12  1208.9  775.42  1336.3  751.48  1375.5  733.49
  1463.8  735.32  1532.4  714.75  1542.2     714  1993.1  720.24  3119.6  714.48
  3178.2  738.16  3510.5  948.79  3637.5  972.15  3794.1  982.47  4019.2  964.18
    4205  908.49  4263.6  880.24  4439.6  953.55  4498.2  937.92  4703.5  849.53
  4850.1  821.11  4889.2  798.49  5074.9  883.72    5114  892.98  5172.6  927.93
#Mann= 3 , 0 , 0
       0     .08       0  1532.4    .045       0  1993.1     .08       0
#XS Ineff= 2 , 0
         1440.21  735.81 2131.09          742.18
Permanent Ineff=
       F       F
Bank Sta=1532.4,1993.1
XS Rating Curve= 0 ,0
Exp/Cntr=0.3,0.1

Type RM Length L Ch R = 1 ,5215.9  ,1156.5,1176,1195.5
XS GIS Cut Line= 4
     1518326.283      266711.659     1519055.449      267232.492
     1519492.949      267565.826     1519867.949      268107.492
#Sta/Elev= 30
       0  947.33    77.9   931.9   136.4  909.65   204.5  893.83     263  875.08
   282.5  870.94   399.3  852.51   506.5  839.37   594.1   839.5   701.3  827.91
   730.5  817.85   798.7   786.2   896.1  756.83   945.2  736.67   964.8  731.79
   994.3  728.25  1043.4  714.76    1063     714  1357.7   714.5  1367.5  717.23
  1613.2  866.14  1721.4  924.17  1750.9  936.95  1849.2  963.67  1937.7  977.37
  1977.1  988.54  2006.6  993.68  2026.2   993.6  2045.9  990.32  2104.9  969.76
#Mann= 3 , 0 , 0
       0     .07       0  1043.4    .045       0  1357.7     .08       0
Bank Sta=1043.4,1357.7
XS Rating Curve= 0 ,0
Exp/Cntr=0.3,0.1

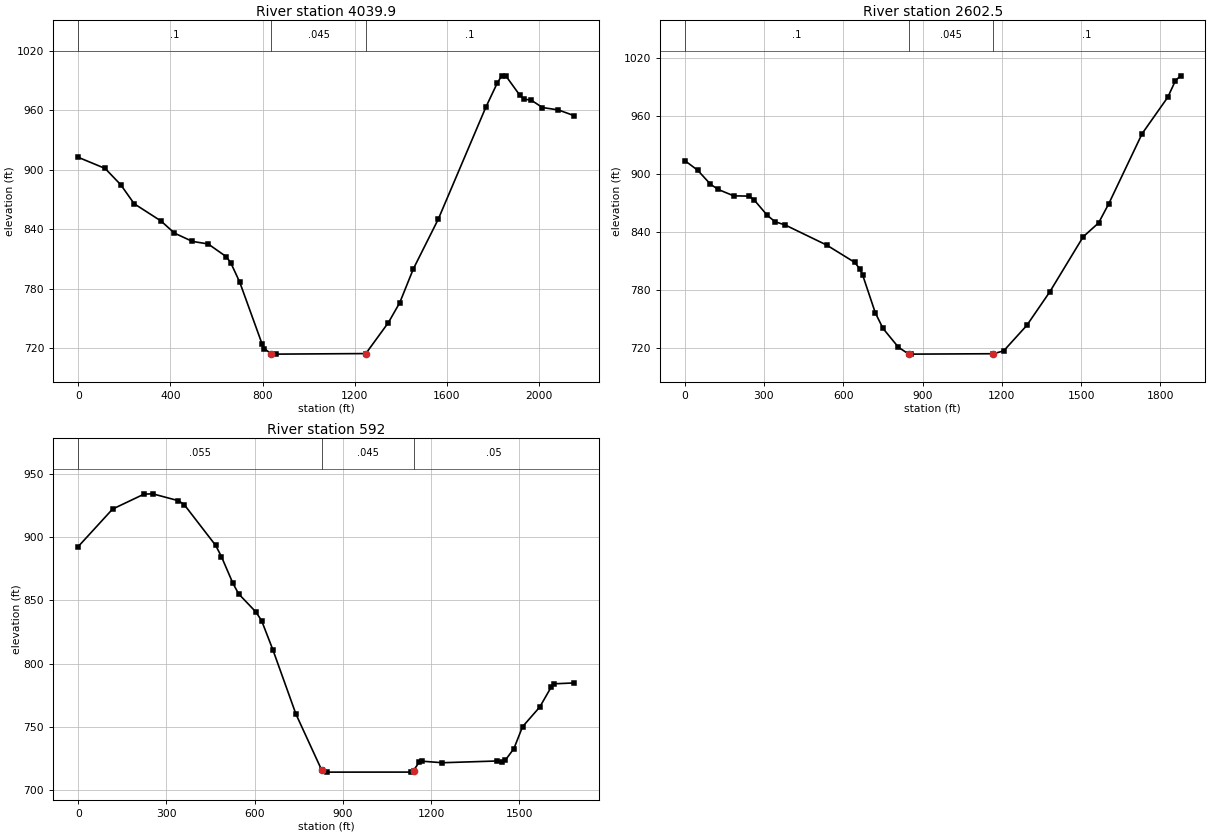
Type RM Length L Ch R = 1 ,4039.9  ,1416.5,1437.4,1458.3
XS GIS Cut Line= 4
     1518263.783      267058.881     1518312.394      267551.937
     1518367.949      268371.381     1518430.449      269204.715
#Sta/Elev= 30
       0  912.64   116.6  901.42   184.6  884.93   242.9  865.76   359.4  848.34
   417.7  836.11   495.4  827.76   563.9  825.18   642.1  812.42   661.7  806.36
   700.8  786.74   798.6  723.85   808.3  719.43   837.7  714.29   857.2     714
  1248.3  714.57  1346.3  745.86  1395.4  765.88  1454.4  799.99  1562.6  850.17
    1769  963.12  1818.2  987.34  1837.8  994.86  1857.5  994.31  1916.5  975.28
  1936.2  971.27  1965.6  970.37  2014.8  962.86  2083.6  960.46  2152.4  954.65
#Mann= 3 , 0 , 0
       0      .1       0   837.7    .045       0  1248.3      .1       0
Bank Sta=837.7,1248.3
XS Rating Curve= 0 ,0
Exp/Cntr=0.3,0.1

Type RM Length L Ch R = 1 ,2602.5  ,2015.5,2010.5,2005.5
XS GIS Cut Line= 4
     1517937.394      266836.659     1517541.561      267169.992
     1516992.949      267649.159      1516593.21      268137.006
#Sta/Elev= 30
       0  914.23    48.8  904.27    97.6  889.71   126.9  884.28   185.5  877.69
   244.1   877.4   263.6  873.23   312.4  857.58   341.7  850.96   380.8  847.49
   536.9  826.84   643.8  808.82   663.2  801.87   672.9  796.25   721.4  756.65
   750.6  740.52   808.8  721.14   847.7  714.04   857.4     714  1168.2  714.41
    1207  717.36  1294.4  743.66  1381.7  778.47  1507.9  835.36  1566.1  849.65
  1604.9  869.63    1731  942.02  1828.1  979.71  1857.2  996.92  1876.6  1001.8
#Mann= 3 , 0 , 0
       0      .1       0   847.7    .045       0  1168.2      .1       0
Bank Sta=847.7,1168.2
XS Rating Curve= 0 ,0
Exp/Cntr=0.3,0.1

Type RM Length L Ch R = 1 ,592     ,592.3,592,586.8
XS GIS Cut Line= 4
     1516381.838      265565.826     1515854.061      265982.492
     1515479.061      266406.103     1515551.977      266849.029
#Sta/Elev= 30
       0   892.7   116.9  922.42   224.1  934.28   253.4   934.5   341.1  929.04
   360.6  925.95   467.8  893.57   487.3  884.69   526.2  863.64   545.7  855.24
   604.2  840.95   623.7  834.11   662.7  810.63   740.7  759.95   828.5  715.48
     848     714  1130.9  714.03  1140.6   715.2  1160.1  722.01  1169.9  722.67
  1238.2  721.44  1423.6  722.82  1443.1  721.82  1452.9  723.47  1482.1   732.6
  1511.4  749.95    1570  765.55    1609   781.4  1618.8  783.97  1687.1  784.67
#Mann= 3 , 0 , 0
       0    .055       0   828.5    .045       0  1140.6     .05       0
Bank Sta=828.5,1140.6
XS Rating Curve= 0 ,0
Exp/Cntr=0.3,0.1

Chan Stop Cuts=-1
Use User Specified Reach Order=0
Composite Channel Slope=5